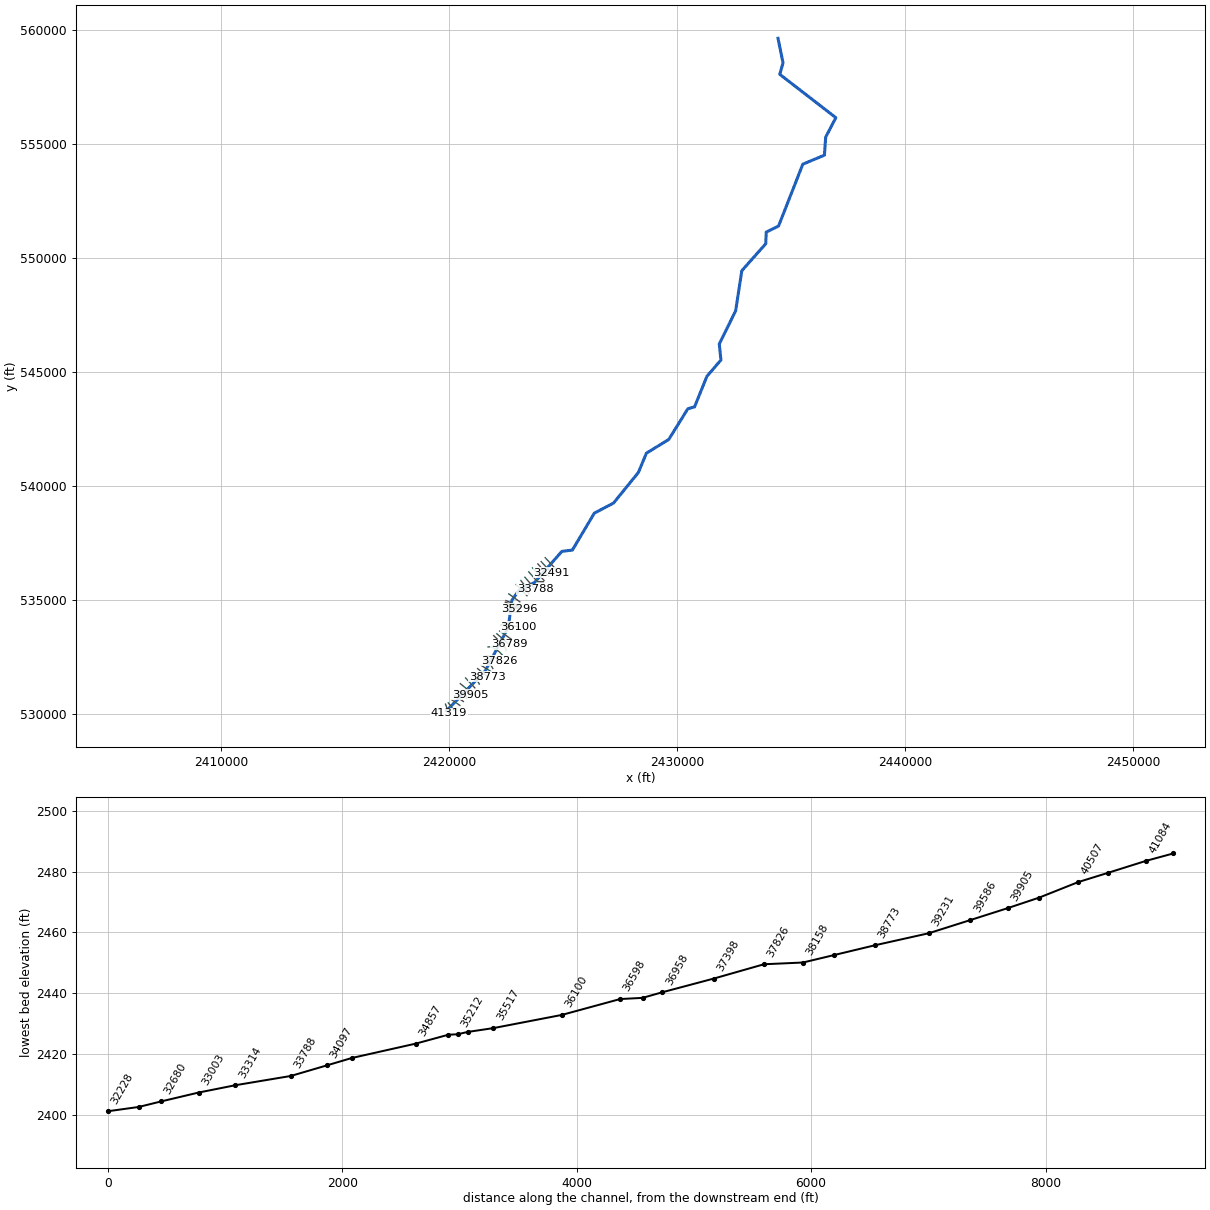
--- WHITHORNCK.prj (project) ---

Proj Title=WHITHORNCK
Current Plan=p01
Default Exp/Contr=0,0
English Units
Geom File=g01
Flow File=f01
Plan File=p01
BEGIN DESCRIPTION:
Stream Name: Whitethorn Creek
Flood Zone: Zone A
Pendleton County, WV
WVDHSEM Flood Warning & Analysis Mapping
HEC-RAS Version: 5.0.7
Model Notes:
Coincident peak with Blackthorn Creek; DS KWSEL boundary from Thorn Creek
END DESCRIPTION:
DSS Export Rating Curves= 0
DSS Export Rating Curve Sorted= 0
DSS Export Volume Flow Curves= 0
DXF OffsetX= 0
DXF OffsetY= 0
DXF ScaleX= 0
DXF ScaleY= 0

--- WHITHORNCK.p01 (plan) ---

Plan Title=Floodplain
Program Version=5.07
Short Identifier=Floodplain
Geom File=g01
Flow File=f01
Subcritical Flow
K Sum by GR= 0
Std Step Tol= 0.01
Critical Tol= 0.01
Num of Std Step Trials= 20
Max Error Tol= 0.3
Flow Tol Ratio= 0.001
Split Flow NTrial= 30
Split Flow Tol= 0.02
Split Flow Ratio= 0.02
Log Output Level= 0
Friction Slope Method= 1
Unsteady Friction Slope Method= 2
Unsteady Bridges Friction Slope Method= 1
Parabolic Critical Depth
Global Vel Dist= 0 , 0 , 0
Global Log Level= 0
CheckData=True
Encroach Param=-1 ,0,0, 0
Mapping Interval=1HOUR
Computation Time Step Use Courant=        0
Computation Time Step Use Time Series=    0
Computation Time Step Count To Double=0
Computation Time Step Max Doubling=0
Computation Time Step Max Halving=0
Computation Time Step Residence Courant=0
Run HTab= 0
Run UNet= 0
Run Sediment= 0
Run PostProcess= 0
Run WQNet= 0
Run RASMapper= 0
UNET Theta= 0
UNET Theta Warmup= 0
UNET ZTol= 0
UNET ZSATol= 0
UNET MxIter= 0
UNET Max Iter WO Improvement= 0
UNET MaxInSteps= 0
UNET DtIC= 0
UNET DtMin= 0
UNET MaxCRTS= 0
UNET WFStab= 0
UNET SFStab= 0
UNET WFX= 1
UNET SFX= 1
UNET 1D Methodology=Finite Difference
UNET DSS MLevel= 1
UNET Pardiso=0
UNET DZMax Abort= 0
UNET Use Existing IB Tables= 0
UNET Froude Reduction=False
UNET Froude Limit= 0
UNET Froude Power= 0
UNET D1 Cores= 0
UNET D2 Coriolis=0
UNET D2 Cores= 0
UNET D2 Theta= 1
UNET D2 Theta Warmup= 1
UNET D2 Z Tol= 0.01
UNET D2 Volume Tol= 0.01
UNET D2 Max Iterations= 20
UNET D2 Equation= 0
UNET D2 RampUpFraction=0.1
UNET D2 TimeSlices= 1
UNET D2 BCVolumeCheck=0
UNET D1D2 MaxIter= 0
UNET D1D2 ZTol=0.01
UNET D1D2 QTol=0.1
UNET D1D2 MinQTol=1
Write IC File= 0
Write IC File at Fixed DateTime=0
Write IC File at Sim End=0
Echo Input=False
Echo Parameters=False
Echo Output=False
Write Detailed= 0
HDF Write Warmup=0
HDF Write Time Slices=0
HDF Flush=0
HDF Face Node Velocities=0
HDF Compression= 1
HDF Chunk Size= 1
HDF Spatial Parts= 1
HDF Use Max Rows=0
HDF Fixed Rows= 1
Calibration Method= 0
Calibration Iterations= 20
Calibration Max Change=0.05
Calibration Tolerance=0.2
Calibration Maximum=1.5
Calibration Minimum=0.5
Calibration Optimization Method= 1
WQ AD Non Conservative
WQ ULTIMATE=-1
WQ Max Comp Step=1HOUR
WQ Output Interval=15MIN
WQ Output Selected Increments= 0
WQ Output face flow=0
WQ Output face velocity=0
WQ Output face area=0
WQ Output face dispersion=0
WQ Output cell volume=0
WQ Output cell surface area=0
WQ Output cell continuity=0
WQ Output cumulative cell continuity=0
WQ Output face conc=0
WQ Output face dconc_dx=0
WQ Output face courant=0
WQ Output face peclet=0
WQ Output face adv mass=0
WQ Output face disp mass=0
WQ Output cell mass=0
WQ Output cell source sink temp=0
WQ Output nsm pathways=0
WQ Output nsm derived pathways=0
WQ Output MaxMinRange=-1
WQ Daily Max Min Mean=-1
WQ Daily Range=0
WQ Daily Time=0
WQ Create Restart=0
WQ Fixed Restart=0
WQ System Summary=0
WQ Write To DSS=0
WQ Use Fixed Temperature=0
Sorting and Armoring Iterations= 10
XS Update Threshold= 0.02
Bed Roughness Predictor= 0
Hydraulics Update Threshold= 0.02
Energy Slope Method= 1
Volume Change Method= 1
Sediment Retention Method= 0
XS Weighting Method= 0
Number of US Weighted Cross Sections= 1
Number of DS Weighted Cross Sections= 1
Upstream XS Weight=0
Main XS Weight=1
Downstream XS Weight=0
Number of DS XS's Weighted with US Boundary= 1
Upstream Boundary Weight= 1
Weight of XSs Associated with US Boundary= 0
Number of US XS's Weighted with DS Boundary= 1
Downstream Boundary Weight= 0.5
Weight of XSs Associated with DS Boundary= 0.5
Percentile Method= 0
Sediment Output Level= 3
Mass or Volume Output= 0
Output Increment Type= 1
Profile and TS Output Increment= 1
XS Output Flag= 0
XS Output Increment= 10
Write Gradation File= 0
Read Gradation Hotstart= 0
Write HDF5 File= 1
Write Binary Output= 1
Write DSS Sediment File= 0
SV Curve= 0
Specific Gage Flag= 0

--- WHITHORNCK.f01 (steady flow) ---

Flow Title=Flows
Program Version=5.07
Number of Profiles= 6
Profile Names=P100yr,P10yr,P25yr,P50yr,P500yr,P101yr
River Rch & RM=WHITHORNCK,Main            ,41319
     472     222     313     390     690     574
River Rch & RM=WHITHORNCK,Main            ,39586
     527     247     349     435     772     641
River Rch & RM=WHITHORNCK,Main            ,39231
     724     337     478     597    1064     881
River Rch & RM=WHITHORNCK,Main            ,36958
     811     377     534     668    1193     987
River Rch & RM=WHITHORNCK,Main            ,33788
    1224     566     804    1008    1808    1490
River Rch & RM=WHITHORNCK,Main            ,31252
    1364     630     896    1123    2018    1661
River Rch & RM=WHITHORNCK,Main            ,26492
    1761     810    1153    1448    2611    2143
River Rch & RM=WHITHORNCK,Main            ,19294
    2014     924    1318    1655    2990    2450
River Rch & RM=WHITHORNCK,Main            ,14787
    2242    1027    1466    1842    3333    2728
River Rch & RM=WHITHORNCK,Main            ,11806
    2570    1175    1678    2110    3826    3127
River Rch & RM=WHITHORNCK,Main            ,5305
    3380    1539    2202    2773    5047    4113
River Rch & RM=WHITHORNCK,Main            ,0
    6178    2788    4006    5058    9285    7519
Boundary for River Rch & Prof#=WHITHORNCK,Main            , 1
Up Type= 0
Dn Type= 1
Dn Known WS=2157.86
Boundary for River Rch & Prof#=WHITHORNCK,Main            , 2
Up Type= 0
Dn Type= 1
Dn Known WS=2155.87
Boundary for River Rch & Prof#=WHITHORNCK,Main            , 3
Up Type= 0
Dn Type= 1
Dn Known WS=2156.65
Boundary for River Rch & Prof#=WHITHORNCK,Main            , 4
Up Type= 0
Dn Type= 1
Dn Known WS=2157.33
Boundary for River Rch & Prof#=WHITHORNCK,Main            , 5
Up Type= 0
Dn Type= 1
Dn Known WS=2159.55
Boundary for River Rch & Prof#=WHITHORNCK,Main            , 6
Up Type= 0
Dn Type= 1
Dn Known WS=2158.55
DSS Import GetInterval= 0
DSS Import GetPeak= 0
DSS Import FillOption= 0

--- WHITHORNCK.g01 (geometry) ---

Geom Title=Geometry
Program Version=5.07

River Reach=WHITHORNCK      ,Main
Reach XY= 30
2419895.44341722530136.4380121982421597.23437166531891.480820164
2422606.16300002 533807.836000012422757.04500002534970.683000013
2423049.11859694 535393.806682022423756.61899999535767.297000021
2424955.16800004537129.127000004     2425415.315537185.774000019
      2426378.72538806.3400000332427220.78300002539248.033999994
2428308.99700001540588.0810000152428662.38499999541435.679000035
     2429643.757542037.5270000252430478.98899999543384.570000023
2430773.79300004543465.388000011     2431315.579544805.330000028
     2431930.873545524.8900000012431859.20899999546228.025000021
2432576.04020524547677.3305324762432847.12525392549439.949730411
2433897.52000001550623.0830000192433919.11880979551134.514347911
2434458.00712699551396.5054921812435523.85699999554113.253000021
2436471.87600002554508.1110000162436526.63100004 555298.37000002
      2436972.28556153.1860000192434511.48500001558055.899000019
2434655.26499999558559.062000006     2434436.132559634.094999999

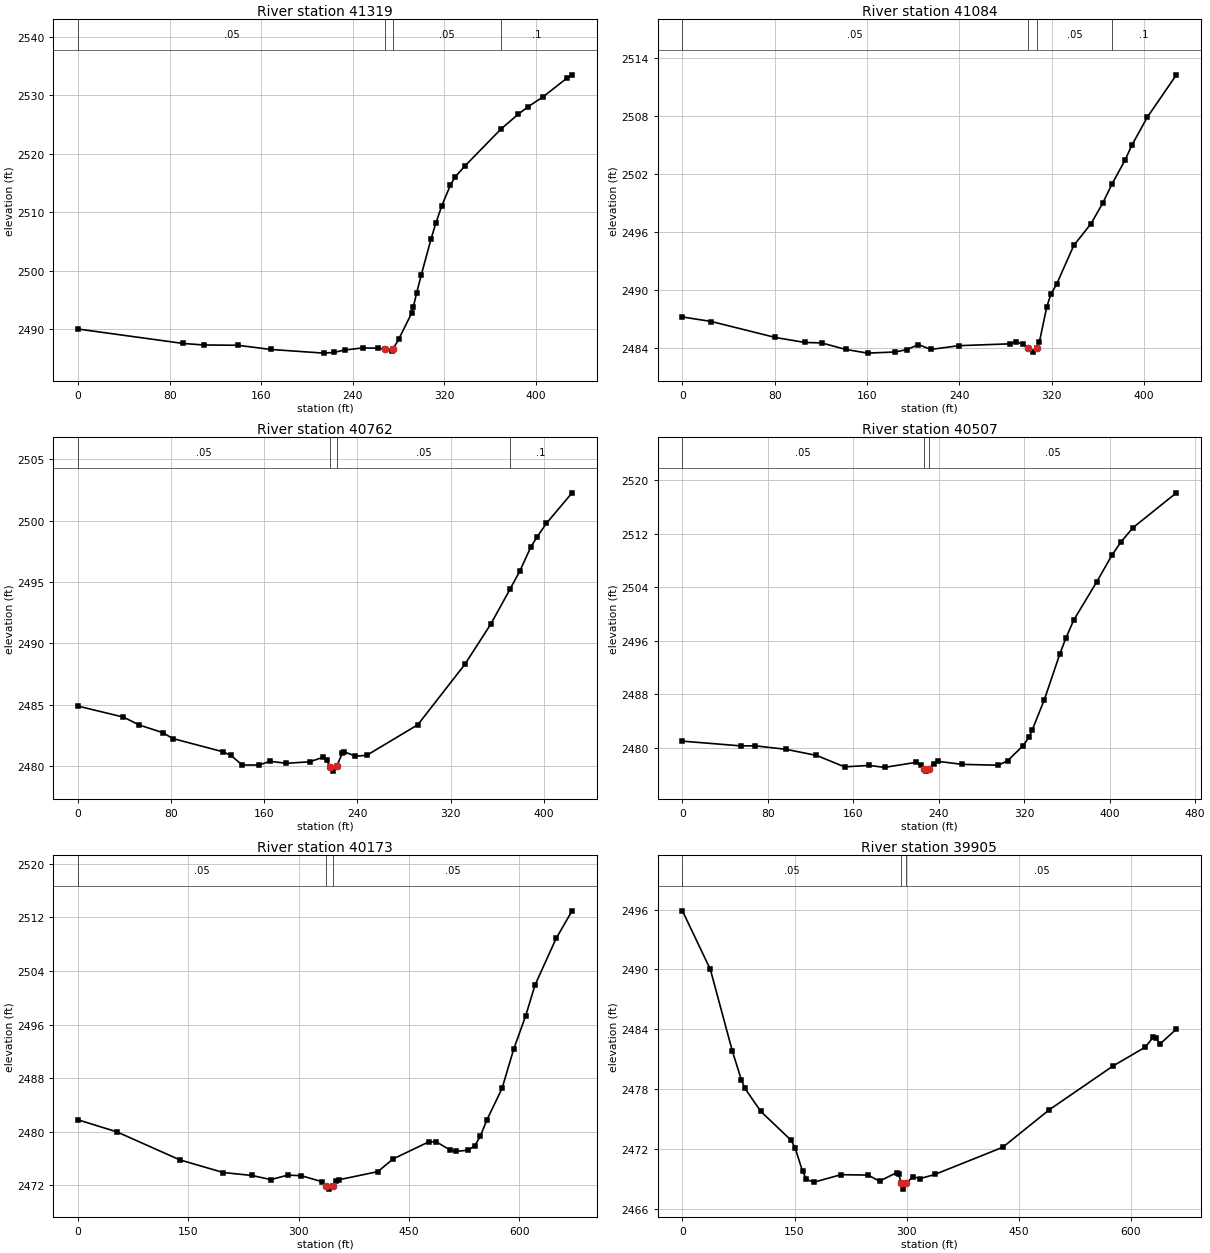
Type RM Length L Ch R = 1 ,41319   ,234.8,234.8,234.8
XS GIS Cut Line= 2
2419848.72188422 530427.985324282419994.30712178530021.445415607
#Sta/Elev= 30
       0 2490.07    91.8 2487.61   109.7 2487.35   139.6  2487.3   168.3 2486.59
   214.7 2485.96   223.5 2486.08   233.5 2486.51   248.7 2486.84   261.9 2486.81
   268.42486.641   274.5 2486.37   275.2  2486.6   280.4  2488.4   291.5 2492.77
   292.9 2493.76     296  2496.3     300 2499.33   308.5 2505.44   312.7 2508.15
   317.9  2511.1   325.4 2514.63   329.7 2516.06   338.2 2517.92  369.432524.168
   384.9 2526.77   393.4 2528.02   406.2 2529.67   427.4 2532.91   431.8 2533.46
#Mann= 4 ,-1 , 0
       0     .05       0   268.4    .045       0   275.2     .05       0
  369.43      .1       0
Bank Sta=268.4,275.2
XS Rating Curve= 0 ,0
Exp/Cntr(USF)=0,0
Exp/Cntr=0.3,0.1

Type RM Length L Ch R = 1 ,41084   ,322.6,322.6,322.6
XS GIS Cut Line= 2
2419972.33199158530485.6700410512420227.79288014530142.308631699
#Sta/Elev= 30
       0 2487.24    25.1 2486.77    80.5 2485.12   106.2  2484.6   120.5 2484.56
   141.5 2483.88   160.5  2483.5   184.6 2483.62   194.6 2483.87   204.5 2484.38
   215.2 2483.88   239.4 2484.27   283.4 2484.46   289.3 2484.65   294.9 2484.44
   299.3 2484.01   303.4 2483.59   307.12484.042   309.2 2484.61   315.7 2488.28
   319.2 2489.58   324.2 2490.63   339.1 2494.64   354.1  2496.9   364.1    2499
  372.242500.991   383.5 2503.46   389.4    2505   402.8  2507.9     428 2512.28
#Mann= 4 ,-1 , 0
       0     .05       0   299.3    .045       0   307.1     .05       0
  372.24      .1       0
Bank Sta=299.3,307.1
XS Rating Curve= 0 ,0
Exp/Cntr(USF)=0,0
Exp/Cntr=0.3,0.1

Type RM Length L Ch R = 1 ,40762   ,254.7,254.7,254.7
XS GIS Cut Line= 2
2420128.90479425530614.7739309672420477.75998615530373.047498783
#Sta/Elev= 30
       0 2484.88    38.8 2483.99    52.6 2483.34    72.7 2482.72    81.3 2482.24
   124.4 2481.16   131.3 2480.86     141 2480.08   155.6 2480.08   164.7 2480.38
     179 2480.22   198.8 2480.34   210.6 2480.71   213.5 2480.48   216.4 2479.94
   219.3 2479.58   222.1 2479.98   226.9 2481.02   228.6 2481.16   238.3  2480.8
     248 2480.87   291.8 2483.36   332.2 2488.28   354.4 2491.55  371.15 2494.43
   379.4 2495.88   388.8 2497.83     394 2498.64   402.4  2499.8   424.4 2502.28
#Mann= 4 ,-1 , 0
       0     .05       0   216.4    .045       0   222.1     .05       0
  371.15      .1       0
Bank Sta=216.4,222.1
XS Rating Curve= 0 ,0
Exp/Cntr(USF)=0,0
Exp/Cntr=0.3,0.1

Type RM Length L Ch R = 1 ,40507   ,333.9,333.9,333.9
XS GIS Cut Line= 2
2420252.51490161530804.3094289292420634.33278881530543.354757822
#Sta/Elev= 30
       0 2481.01    54.6  2480.3    68.2 2480.31    97.2 2479.78   125.5 2478.88
   151.8 2477.17   174.7 2477.38   189.3 2477.09   218.3 2477.83   223.2 2477.49
   225.82476.913     228 2476.53   230.82476.887   235.2 2477.66   238.9    2478
   261.9 2477.54   295.8 2477.41   304.4 2478.08   318.8  2480.3   324.5 2481.59
   327.4 2482.64   338.9 2487.22   353.3 2494.01     359  2496.4   366.4  2499.1
   387.9  2504.8   402.4 2508.86   410.8  2510.8   421.8 2512.89   462.5  2518.1
#Mann= 3 ,-1 , 0
       0     .05       0   225.8    .045       0   230.8     .05       0
Bank Sta=225.8,230.8
XS Rating Curve= 0 ,0
Exp/Cntr(USF)=0,0
Exp/Cntr=0.3,0.1

Type RM Length L Ch R = 1 ,40173   ,268.3,268.3,268.3
XS GIS Cut Line= 4
2420288.22448819531026.8076221882420414.58148683531013.073165814
2420727.72709216530864.741036974 2420777.1711351530672.458647738
#Sta/Elev= 30
       0 2481.76    52.9 2479.96   138.4 2475.78   197.5 2473.89   236.5 2473.45
   262.3 2472.83     285  2473.5   303.6 2473.42   331.7 2472.52   337.5 2471.91
   341.7 2471.41   346.4 2471.88   350.7 2472.59   355.2 2472.82   407.7 2474.02
   428.7 2475.93   476.9 2478.46   486.9  2478.5   505.8 2477.27   514.1 2477.05
   530.6 2477.22   539.5 2477.87   547.1 2479.28   555.9 2481.69   576.8 2486.46
   592.6 2492.31   609.1 2497.35   621.6 2501.89   650.4 2508.87   672.1 2512.99
#Mann= 3 ,-1 , 0
       0     .05       0   337.5    .045       0   346.4     .05       0
Bank Sta=337.5,346.4
XS Rating Curve= 0 ,0
Exp/Cntr(USF)=0,0
Exp/Cntr=0.3,0.1

Type RM Length L Ch R = 1 ,39905   ,318.5,318.5,318.5
XS GIS Cut Line= 3
2420499.73511635531323.471879868 2420832.1089606531054.276534936
2420936.49082904530845.512798051
#Sta/Elev= 30
       0 2495.89    37.4    2490    66.7 2481.84    78.9 2478.91    83.7 2478.06
   104.9 2475.75   145.4 2472.86   150.6 2472.12   160.9 2469.72     166 2468.93
   175.6 2468.64   212.3  2469.4   248.4 2469.36   263.8 2468.75   286.5  2469.6
   289.2 2469.49   292.82468.564   295.5 2467.95   299.8 2468.52   308.2  2469.2
   318.3 2469.01   337.7 2469.42   428.6 2472.15   491.2 2475.93   576.2 2480.31
   619.6 2482.21   629.8 2483.18   634.3  2483.1   638.8  2482.5   661.1 2484.02
#Mann= 3 ,-1 , 0
       0     .05       0   292.8    .045       0   299.8     .05       0
Bank Sta=292.8,299.8
XS Rating Curve= 0 ,0
Exp/Cntr(USF)=0,0
Exp/Cntr=0.3,0.1

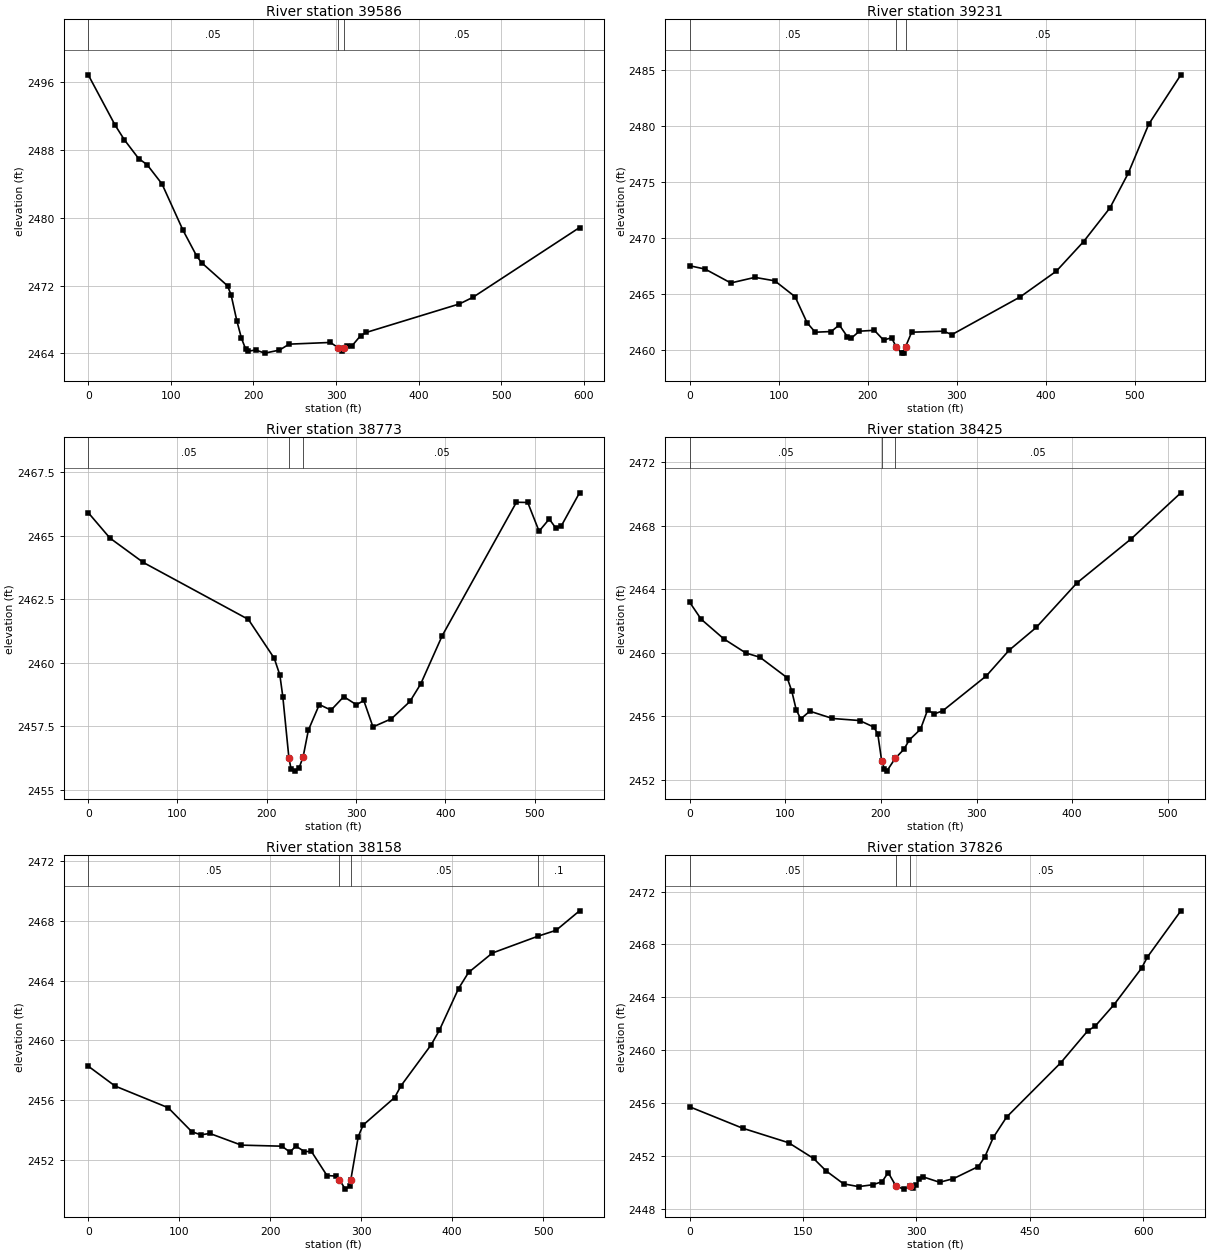
Type RM Length L Ch R = 1 ,39586   ,355,355,355
XS GIS Cut Line= 2
2420730.47398343531573.438985876 2421137.0138921531139.430164456
#Sta/Elev= 30
       0 2496.88    32.7 2490.91    43.9 2489.19      61    2487    71.3 2486.27
    89.3    2484   114.8 2478.52   131.5 2475.45   137.4 2474.69   168.6 2471.98
     173 2470.88   179.9 2467.84   185.5 2465.78   190.5 2464.53     194 2464.26
   202.5  2464.4   213.8 2464.03   231.5 2464.39   243.2 2465.09   293.1 2465.29
   302.42464.682   307.2 2464.26     310 2464.59   312.9 2464.91   319.2 2464.88
   329.8  2466.1   336.8 2466.48   449.4 2469.84   465.7 2470.62   594.7 2478.85
#Mann= 3 ,-1 , 0
       0     .05       0   302.4    .045       0     310     .05       0
Bank Sta=302.4,310
XS Rating Curve= 0 ,0
Exp/Cntr(USF)=0,0
Exp/Cntr=0.3,0.1

Type RM Length L Ch R = 1 ,39231   ,458.8,458.8,458.8
XS GIS Cut Line= 2
2421076.58228406531790.4433965862421332.04317262531301.496749669
#Sta/Elev= 30
       0  2467.5    17.5  2467.2    46.3 2465.96    73.4 2466.46    95.7 2466.15
   118.5 2464.73     132  2462.4   141.1 2461.56   159.1 2461.62   168.1 2462.21
   177.2 2461.16   181.7 2461.03   190.7 2461.65   207.5 2461.73   217.8 2460.86
   226.8 2461.06     232 2460.26     238 2459.69   240.3 2459.72   242.62460.271
   249.4 2461.56   285.4 2461.65   294.5 2461.34   371.2 2464.71   411.8 2467.01
   442.5 2469.66   472.1 2472.67   492.6 2475.76   515.6 2480.14   551.7 2484.56
#Mann= 3 ,-1 , 0
       0     .05       0     232    .045       0   242.6     .05       0
Bank Sta=232,242.6
XS Rating Curve= 0 ,0
Exp/Cntr(USF)=0,0
Exp/Cntr=0.3,0.1

Type RM Length L Ch R = 1 ,38773   ,347.2,347.2,347.2
XS GIS Cut Line= 2
 2421257.8771082531985.4726770972421683.64525579531636.617485196
#Sta/Elev= 30
       0 2465.91    24.3 2464.91    61.7 2463.95   179.4 2461.71   208.4 2460.18
   214.7 2459.52     218 2458.67   224.82456.269   227.3 2455.81   231.1 2455.74
   236.3 2455.87   240.8 2456.31   246.6 2457.35   258.9 2458.36     272 2458.14
   286.3 2458.67   300.5 2458.35   308.7 2458.52     319 2457.48   339.7  2457.8
   360.4 2458.48   372.5 2459.17   396.6 2461.07   479.7 2466.32   492.4 2466.31
   505.1 2465.18   516.5 2465.66   523.9  2465.3   530.2  2465.4   550.4 2466.69
#Mann= 3 ,-1 , 0
       0     .05       0   224.8    .045       0   240.8     .05       0
Bank Sta=224.8,240.8
XS Rating Curve= 0 ,0
Exp/Cntr(USF)=0,0
Exp/Cntr=0.3,0.1

Type RM Length L Ch R = 1 ,38425   ,267.4,267.4,267.4
XS GIS Cut Line= 2
2421414.44991086532128.3110233872421848.45873228531853.621895906
#Sta/Elev= 30
       0 2463.19    12.1 2462.11    35.8 2460.87    58.8 2459.98    73.6 2459.71
     102 2458.42   106.8 2457.59   111.5  2456.4   116.2 2455.82   125.7 2456.31
   149.4 2455.85   177.8 2455.72   192.5 2455.31   196.7  2454.9   200.8 2453.19
   203.7 2452.67   206.2 2452.53   214.9 2453.33     224  2453.9   229.8  2454.5
   241.4 2455.17   248.8 2456.38   255.9 2456.14   264.6 2456.33   310.3 2458.54
     334 2460.15   362.4 2461.59     405  2464.4   461.9 2467.19   513.6 2470.08
#Mann= 3 ,-1 , 0
       0     .05       0   200.8    .045       0   214.9     .05       0
Bank Sta=200.8,214.9
XS Rating Curve= 0 ,0
Exp/Cntr(USF)=0,0
Exp/Cntr=0.3,0.1

Type RM Length L Ch R = 1 ,38158   ,332.2,332.2,332.2
XS GIS Cut Line= 3
 2421540.8069095532356.3029991972421837.47116718532139.298588487
2421925.37168797531990.966459647
#Sta/Elev= 30
       0 2458.28    29.5 2456.95    87.9  2455.5   113.8  2453.9   123.7 2453.69
   133.7 2453.78   168.3    2453   212.9 2452.93   221.8 2452.53   228.1 2452.94
   237.7 2452.57   245.3 2452.58   262.4 2450.97   272.4 2450.93     276  2450.7
   282.5 2450.06   287.2 2450.25   288.5 2450.64   296.8 2453.57   302.1 2454.34
   336.8 2456.18   343.7 2456.96   377.1 2459.72   385.9 2460.67     407 2463.46
     418 2464.54   444.2 2465.84  494.272466.963   514.3 2467.36     540 2468.66
#Mann= 4 ,-1 , 0
       0     .05       0     276    .045       0   288.5     .05       0
  494.27      .1       0
Bank Sta=276,288.5
XS Rating Curve= 0 ,0
Exp/Cntr(USF)=0,0
Exp/Cntr=0.3,0.1

Type RM Length L Ch R = 1 ,37826   ,427.7,427.7,427.7
XS GIS Cut Line= 4
2421598.49162627532537.5978233342421705.62038599532543.091605884
2422027.00666514532463.4317589142422194.56703291532334.327868998
#Sta/Elev= 30
       0 2455.72    70.1  2454.1     131    2453     164 2451.81   180.6 2450.87
   203.7 2449.89   223.5 2449.68   242.2 2449.82   254.6 2450.05   262.8 2450.74
     273 2449.72   283.4 2449.49   291.7 2449.73   296.1 2449.56   299.9 2449.79
     304 2450.29   308.2 2450.43   330.7 2450.01     349 2450.28     382  2451.2
   390.6 2451.93   401.8  2453.4   419.4 2454.94   490.9 2459.04     527 2461.48
   536.3  2461.8   561.6 2463.45   597.9  2466.2   605.6 2467.04   649.9 2470.54
#Mann= 3 ,-1 , 0
       0     .05       0     273    .045       0   291.7     .05       0
Bank Sta=273,291.7
XS Rating Curve= 0 ,0
Exp/Cntr(USF)=0,0
Exp/Cntr=0.3,0.1

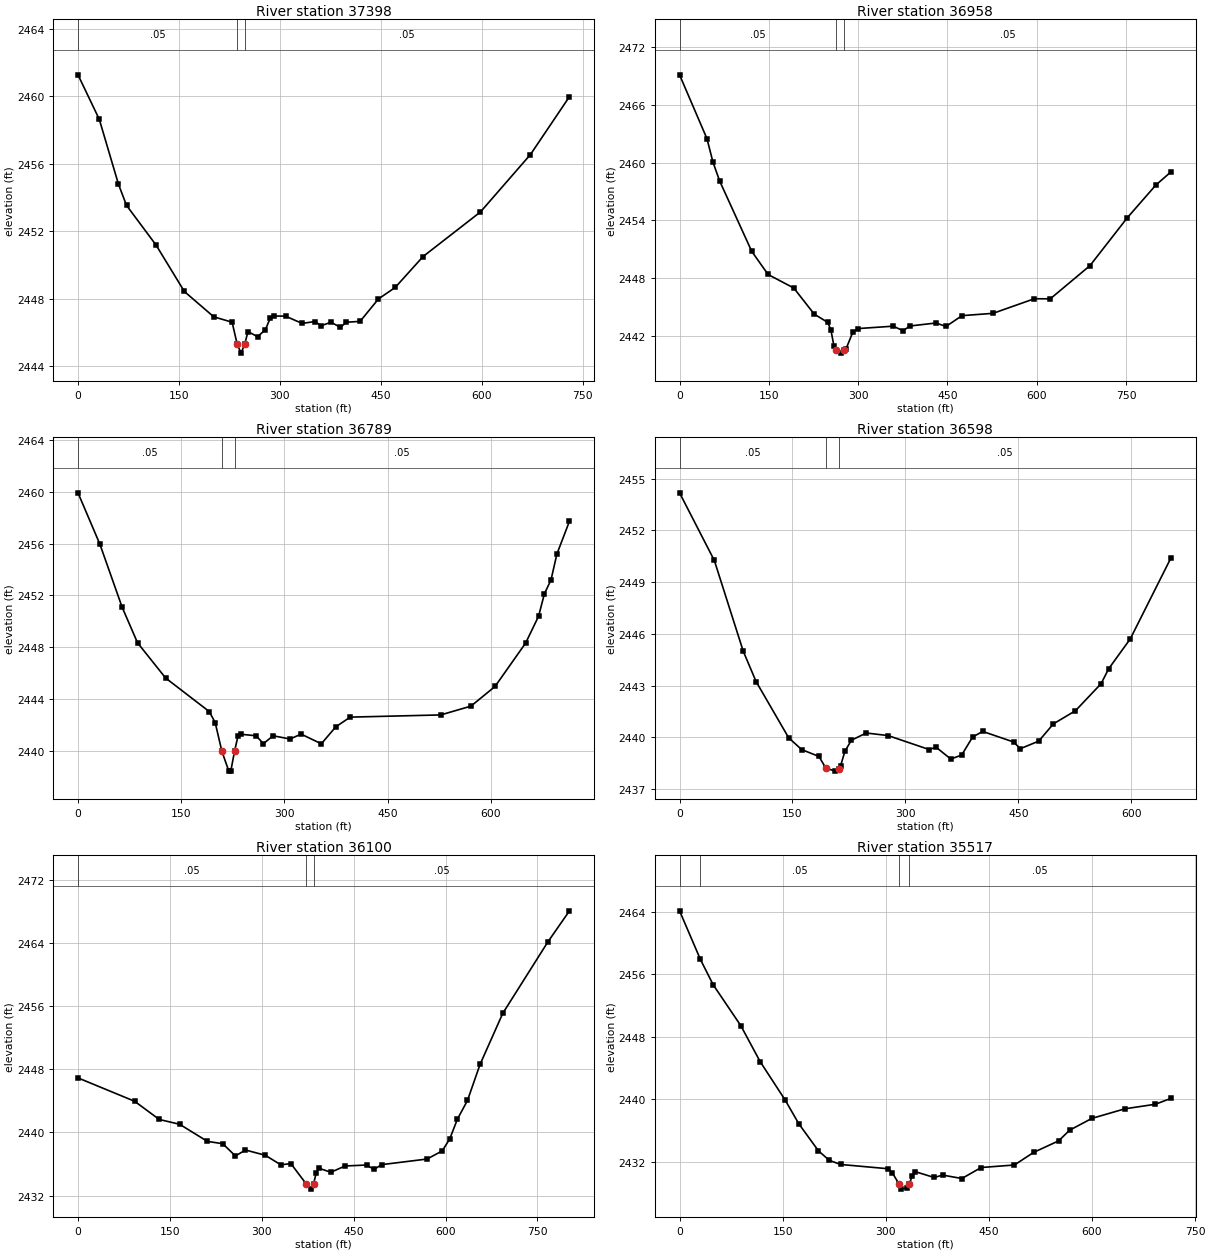
Type RM Length L Ch R = 1 ,37398   ,440.4,440.4,440.4
XS GIS Cut Line= 4
2421716.60795109532935.8970581822421862.19318865532944.137732006
2422197.31392418532732.6271038462422329.16470537 532598.02943138
#Sta/Elev= 30
       0 2461.27    31.7 2458.63    60.1  2454.8    72.1 2453.54   116.2 2451.18
   158.1 2448.44   201.8 2446.94   229.1 2446.62   236.6 2445.32   242.4 2444.79
     248 2445.35   252.7 2446.07   266.9 2445.76   278.6 2446.18   285.8 2446.87
   290.6 2446.99   308.5 2446.98   333.1 2446.55   352.1 2446.66   361.3 2446.41
     376 2446.62   389.9 2446.32     399 2446.62   419.3 2446.67   446.6    2448
   471.5 2448.68   512.9 2450.51   598.2 2453.15   672.5 2456.55   730.5 2459.98
#Mann= 3 ,-1 , 0
       0     .05       0   236.6    .045       0     248     .05       0
Bank Sta=236.6,248
XS Rating Curve= 0 ,0
Exp/Cntr(USF)=0,0
Exp/Cntr=0.3,0.1

Type RM Length L Ch R = 1 ,36958   ,168.5,168.5,168.5
XS GIS Cut Line= 3
2421961.08127455533433.0843789232422395.09009597533018.303796426
2422507.71263823532823.274515915
#Sta/Elev= 30
       0 2469.08    46.1 2462.46    56.1 2460.04    67.5 2458.07   121.2 2450.81
   148.7 2448.41   191.9 2447.01   226.2 2444.31   248.7 2443.46   254.2 2442.68
   259.4 2440.99   262.6  2440.6   270.4 2440.27     276 2440.63   279.6  2440.7
   290.9 2442.42   299.4 2442.81   358.9 2443.06   375.5 2442.59   387.1 2443.08
   430.9 2443.39   447.5 2443.03   474.5 2444.15   526.6 2444.39     596  2445.9
   622.7 2445.89   689.3 2449.32   752.2 2454.29   800.1 2457.67   825.6 2459.04
#Mann= 3 ,-1 , 0
       0     .05       0   262.6    .045       0     276     .05       0
Bank Sta=262.6,276
XS Rating Curve= 0 ,0
Exp/Cntr(USF)=0,0
Exp/Cntr=0.3,0.1

Type RM Length L Ch R = 1 ,36789   ,191,191,191
XS GIS Cut Line= 2
2422099.81697477533513.4019084492422642.71269862533049.621641843
#Sta/Elev= 30
       0 2459.92    31.9 2455.94    64.1 2451.09    86.5 2448.34   127.3 2445.62
   190.7 2443.03   199.3 2442.18     2092439.967   219.1 2438.43     222 2438.44
   227.6 2440.01   232.5 2441.15   236.1 2441.28   258.8 2441.16   269.3 2440.55
   283.5 2441.16   308.2 2440.91   324.1 2441.29   353.5 2440.54   374.5 2441.85
   395.5  2442.6     527 2442.77   570.9 2443.45   605.9 2444.97   650.3 2448.32
   669.1 2450.39   677.6 2452.13   687.2  2453.2   695.7 2455.19     714 2457.73
#Mann= 3 ,-1 , 0
       0     .05       0     209    .045       0   227.6     .05       0
Bank Sta=209,227.6
XS Rating Curve= 0 ,0
Exp/Cntr(USF)=0,0
Exp/Cntr=0.3,0.1

Type RM Length L Ch R = 1 ,36598   ,498.2,498.2,498.2
XS GIS Cut Line= 2
2422225.13573863 533631.627671842422760.77953722533258.050458465
#Sta/Elev= 30
       0 2454.17    46.2 2450.25    84.6 2444.99   101.7 2443.23     145 2439.97
   162.2 2439.29   185.2 2438.89   194.4 2438.21     207 2438.04   211.2 2438.18
   213.9 2438.34   219.7 2439.19   228.3 2439.83     248 2440.25   277.1  2440.1
   331.7 2439.29   340.7 2439.43   360.4 2438.74   374.8 2438.97   389.4 2440.02
   402.8 2440.34   443.7 2439.73   452.8 2439.34   477.2 2439.78   496.7 2440.78
     526 2441.54   560.1 2443.11   570.1 2443.97   598.9 2445.71     653 2450.41
#Mann= 3 ,-1 , 0
       0     .05       0   194.4    .045       0   211.2     .05       0
Bank Sta=194.4,211.2
XS Rating Curve= 0 ,0
Exp/Cntr(USF)=0,0
Exp/Cntr=0.3,0.1

Type RM Length L Ch R = 1 ,36100   ,583.2,583.2,583.2
XS GIS Cut Line= 3
2422276.97377115533894.5621130912422480.24372549533952.246829862
2423054.34400192533812.155374847
#Sta/Elev= 30
       0 2446.89    92.5 2443.93   132.6 2441.63   165.9 2441.02   211.3 2438.85
   236.3 2438.56   256.9 2437.01   273.4 2437.76   305.6  2437.1     331 2435.89
   347.5 2436.04   372.6 2433.46   380.4 2432.81   384.5 2433.45   388.6  2434.8
   392.8 2435.47   412.7 2434.94   435.8 2435.74     471 2435.86   483.3 2435.31
   495.7 2435.91   569.8 2436.62   594.5 2437.65   606.8 2439.17   619.2 2441.66
   635.7 2444.03   656.2 2448.59   693.3 2455.06   766.8 2464.09   802.2 2468.04
#Mann= 3 ,-1 , 0
       0     .05       0   372.6    .045       0   384.5     .05       0
Bank Sta=372.6,384.5
XS Rating Curve= 0 ,0
Exp/Cntr(USF)=0,0
Exp/Cntr=0.3,0.1

Type RM Length L Ch R = 1 ,35517   ,220.6,220.6,220.6
XS GIS Cut Line= 2
2422375.86185704534520.8533237482423087.30669722534449.434150603
#Sta/Elev= 30
       0 2464.13   30.362457.896    48.9 2454.66    89.1 2449.42   117.2 2444.82
   153.5 2439.91   173.5 2436.85   202.1 2433.38   217.8 2432.17   234.2 2431.64
   303.6 2431.09   309.4 2430.58   319.52429.113   322.3 2428.48   330.3 2428.63
   334.3 2429.15   338.4 2430.16   342.4 2430.73   370.5 2429.97   382.6 2430.28
   410.7 2429.84   438.8 2431.25   487.1 2431.57   515.2 2433.19   551.4 2434.66
   567.5 2436.03   599.8 2437.54   647.9 2438.77   692.1 2439.35     715 2440.11
#Mann= 4 ,-1 , 0
       0     .06       0   30.36     .05       0   319.5    .045       0
   334.3     .05       0
Bank Sta=319.5,334.3
XS Rating Curve= 0 ,0
Exp/Cntr(USF)=0,0
Exp/Cntr=0.3,0.1

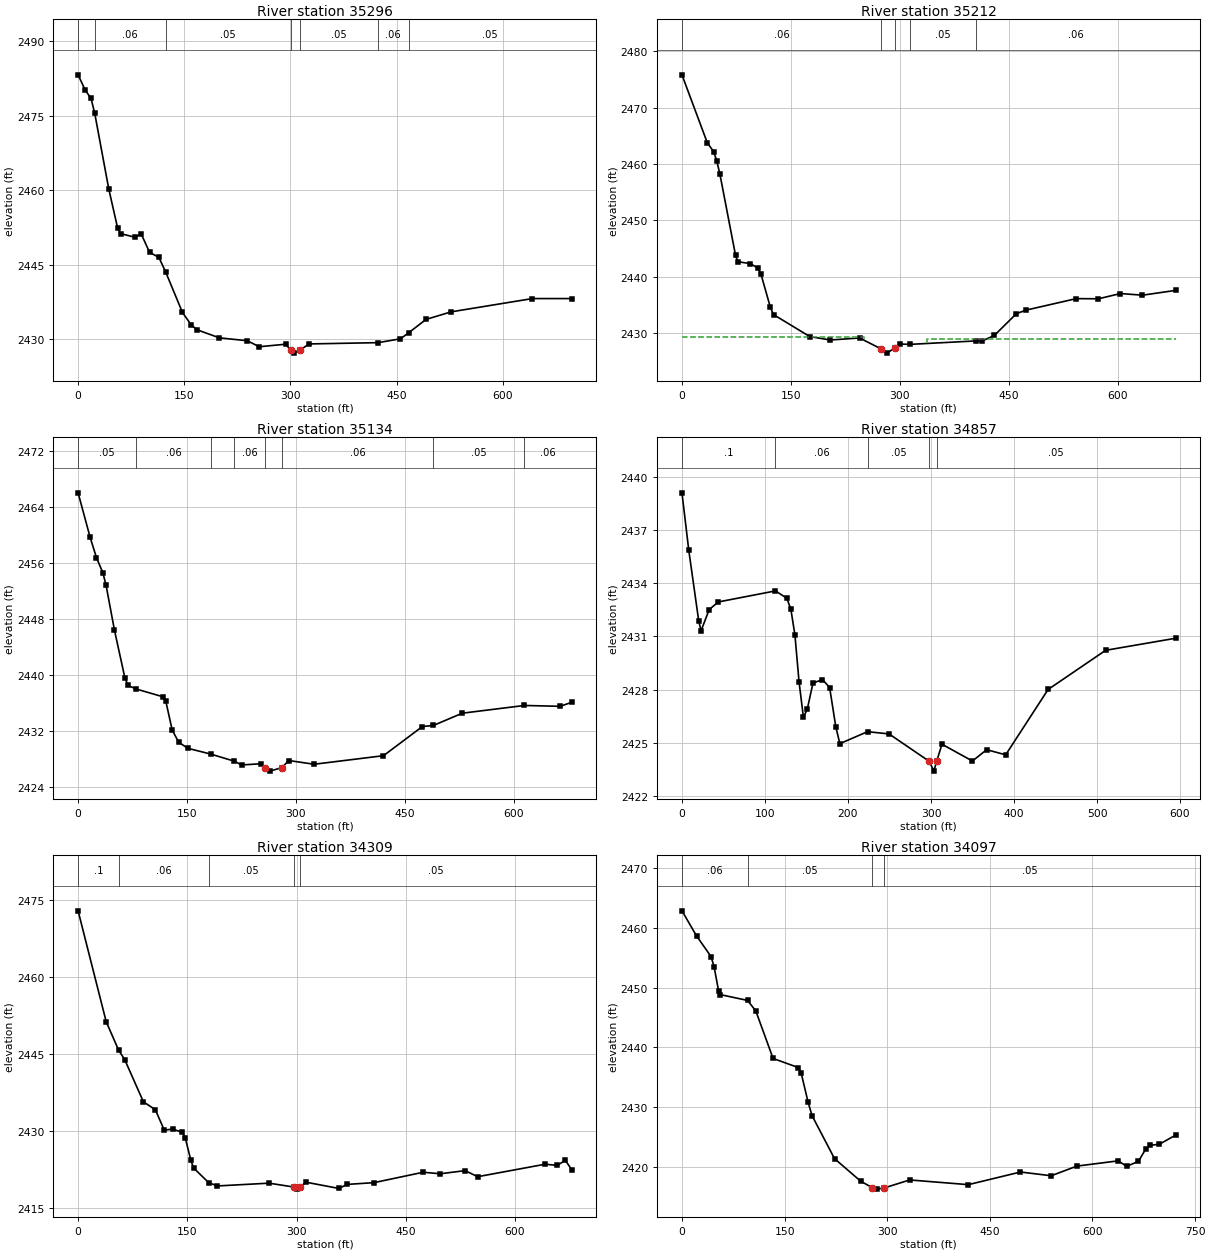
Type RM Length L Ch R = 1 ,35296   ,84.5,84.5,84.5
XS GIS Cut Line= 2
2422426.96007032534792.6126009452423096.86489986  534598.6130123
#Sta/Elev= 30
       0 2483.22      10 2480.16    18.3 2478.46   23.542475.445    43.3 2460.28
    55.8 2452.41      60 2451.26    80.8 2450.52    89.1 2451.23     101 2447.48
   114.1 2446.49  123.592443.593   147.4 2435.41   159.9 2432.88   168.2  2431.9
   199.6 2430.29     239  2429.7     256  2428.5   293.1    2429   300.3 2427.87
   305.6 2427.21   313.7 2427.84   326.4 2429.06  423.742429.318   455.5 2430.09
  466.952431.292   491.7    2434   527.2 2435.52   641.9 2438.19   697.4 2438.19
#Mann= 7 ,-1 , 0
       0     .05       0   23.54     .06       0  123.59     .05       0
   300.3    .045       0   313.7     .05       0  423.74     .06       0
  466.95     .05       0
Bank Sta=300.3,313.7
XS Rating Curve= 0 ,0
Exp/Cntr(USF)=0,0
Exp/Cntr=0.5,0.3

Type RM Length L Ch R = 1 ,35212   ,78,78,78
XS GIS Cut Line= 2
2422472.42872391534901.7373695582423098.38052165534636.503556957
#Sta/Elev= 30
       0 2475.83    34.9 2463.77    43.6  2462.2    47.9 2460.58    52.3 2458.18
    73.8  2443.8    76.9 2442.67      94 2442.34   104.4 2441.56   108.7 2440.52
   121.8 2434.56   126.1 2433.29     176 2429.39   204.3 2428.78   244.7 2429.14
   273.8 2427.23   282.5 2426.45   292.9 2427.37   299.9 2428.06  314.442428.005
  404.832428.618   412.8 2428.57   430.2 2429.58   460.6 2433.45   473.9 2434.08
   543.1 2436.12   573.5 2436.09   603.9 2437.02   634.3 2436.73   679.8 2437.58
#Mann= 5 ,-1 , 0
       0     .06       0   273.8    .045       0   292.9     .06       0
  314.44     .05       0  404.83     .06       0
#XS Ineff= 2 , 0
       0  251.21 2429.33  337.13       0 2429.03
Permanent Ineff=
       F       F
Bank Sta=273.8,292.9
XS Rating Curve= 0 ,0
Exp/Cntr(USF)=0,0
Exp/Cntr=0.5,0.3

Type RM Length L Ch R = 1 ,35134   ,276.5,276.5,276.5
XS GIS Cut Line= 2
2422501.22553785534971.4559717272423127.17733559534706.222159126
#Sta/Elev= 30
       0 2465.99    16.6 2459.63    25.3 2456.75      34 2454.62    38.4 2452.88
    50.1  2446.4    64.4 2439.63    68.8 2438.52    80.32438.011   117.2  2436.9
   120.9 2436.24   129.6 2432.16   138.6 2430.42   151.3 2429.56  182.552428.744
  215.282427.724   225.1 2427.19   251.5 2427.36   257.6 2426.79   264.2 2426.31
   280.6 2426.81   290.3 2427.82     325 2427.29   420.6 2428.51   474.2 2432.67
   489.32432.819   529.2 2434.57   614.72435.672   663.9 2435.55   679.8 2436.12
#Mann= 8 ,-1 , 0
       0     .05       0    80.3     .06       0  182.55     .05       0
  215.28     .06       0   257.6    .045       0   280.6     .06       0
   489.3     .05       0   614.7     .06       0
Bank Sta=257.6,280.6
XS Rating Curve= 0 ,0
Exp/Cntr(USF)=0,0
Exp/Cntr=0.5,0.3

Type RM Length L Ch R = 1 ,34857   ,547.8,547.8,547.8
XS GIS Cut Line= 2
2422625.82896305535262.5139679472423109.28182742534916.405667321
#Sta/Elev= 30
       0 2439.11     8.2 2435.87    20.2 2431.88      23 2431.32    32.8 2432.52
    43.8 2432.95  112.652433.574   126.3 2433.16   131.2 2432.54   136.1 2431.08
   141.1 2428.42   146.3 2426.45   150.9 2426.88   157.8 2428.37   169.3 2428.57
   177.9 2428.12   185.3 2425.91   190.2 2424.95  223.522425.627   249.5  2425.5
     298 2423.95   303.4  2423.4   306.9 2423.96   313.2 2424.92   349.9 2423.97
   367.1 2424.61     390 2424.32   441.1 2428.01   510.4 2430.22   594.6  2430.9
#Mann= 5 ,-1 , 0
       0      .1       0  112.65     .06       0  223.52     .05       0
     298    .045       0   306.9     .05       0
Bank Sta=298,306.9
XS Rating Curve= 0 ,0
Exp/Cntr(USF)=0,0
Exp/Cntr=0.3,0.1

Type RM Length L Ch R = 1 ,34309   ,212.9,212.9,212.9
XS GIS Cut Line= 2
2422949.96213348535669.0538766192423422.42743275535182.854120978
#Sta/Elev= 30
       0 2472.85    38.6 2451.25   55.652445.718    64.1 2443.85    89.7 2435.66
   106.1 2434.11   118.4 2430.13   129.9 2430.35   143.3 2429.69   147.1 2428.69
   154.6  2424.4   158.6 2422.77  179.382419.912   191.3 2419.27   262.2 2419.81
   296.3 2419.06   301.2 2418.65   304.5    2419     313    2420   358.2 2418.78
   369.5 2419.57   406.3 2419.91   474.1 2421.94   497.2 2421.64   531.6 2422.25
   548.8 2421.07   641.4  2423.5     658 2423.28   669.3 2424.25   677.9 2422.44
#Mann= 5 ,-1 , 0
       0      .1       0   55.65     .06       0  179.38     .05       0
   296.3    .045       0   304.5     .05       0
Bank Sta=296.3,304.5
XS Rating Curve= 0 ,0
Exp/Cntr(USF)=0,0
Exp/Cntr=0.3,0.1

Type RM Length L Ch R = 1 ,34097   ,308.4,308.4,308.4
XS GIS Cut Line= 4
2423154.16498548535849.7887051532423292.25497046535674.650187626
 2423278.7827768   535571.9247112423514.54616578535255.328160085
#Sta/Elev= 30
       0 2462.87    21.4 2458.65    42.5 2455.21    46.9 2453.53    53.5 2449.48
    55.4 2448.84   95.912447.852     108 2446.07   133.2 2438.12   170.3 2436.59
   174.2  2435.7   184.4 2430.77   190.2 2428.52     223 2421.33     261 2417.57
   277.8 2416.48     285 2416.22   295.7 2416.42   332.8 2417.76   418.5 2416.97
   494.8 2419.09   539.7 2418.46   577.2 2420.08   637.5 2420.96   650.1 2420.04
   667.2 2420.88   677.7 2422.91   684.3 2423.56   697.8 2423.75   721.4 2425.26
#Mann= 4 ,-1 , 0
       0     .06       0   95.91     .05       0   277.8    .045       0
   295.7     .05       0
Bank Sta=277.8,295.7
XS Rating Curve= 0 ,0
Exp/Cntr(USF)=0,0
Exp/Cntr=0.3,0.1

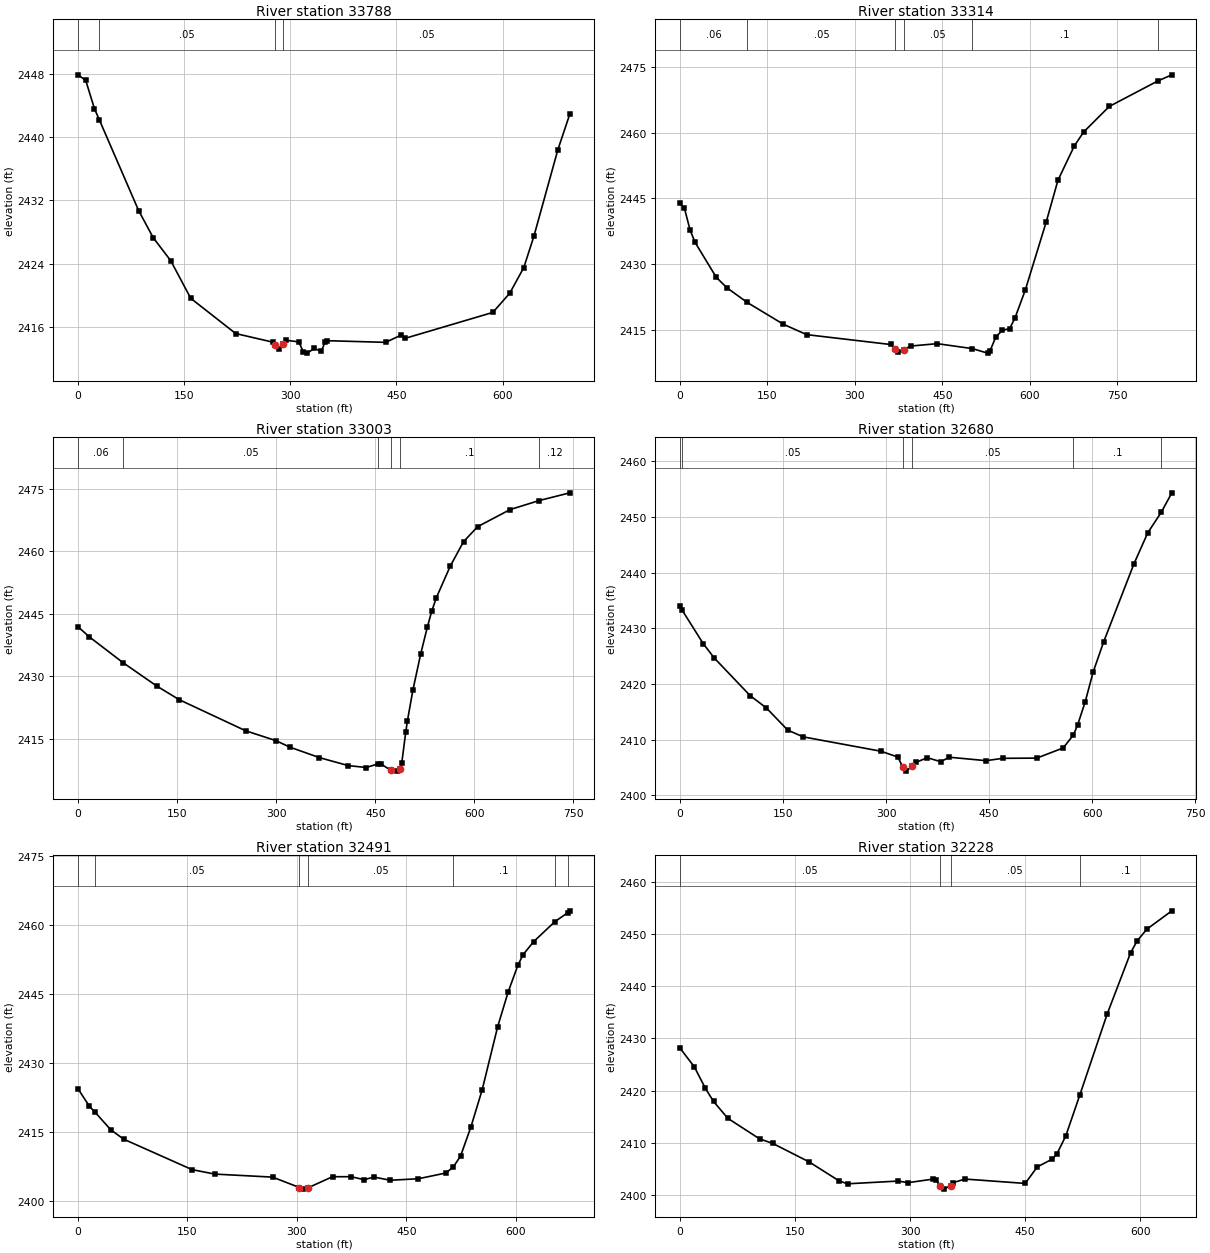
Type RM Length L Ch R = 1 ,33788   ,473.9,473.9,473.9
XS GIS Cut Line= 2
2423331.78002068535993.187047047 2423787.7639723535468.530813558
#Sta/Elev= 30
       0 2447.86    10.9 2447.16    23.3 2443.57   30.062442.197    85.7 2430.72
   106.3  2427.3   131.1 2424.39   159.3 2419.65   222.9  2415.2   275.6 2414.11
   278.5 2413.76   284.2 2413.22   289.8 2413.85   293.7 2414.36     312 2414.15
   318.3 2412.92   323.6 2412.73   334.2 2413.32   343.7 2412.94   349.4 2414.18
   352.2  2414.3   434.8 2414.09     456 2414.98   462.8 2414.61   586.3 2417.87
   610.2  2420.3     630 2423.53   644.2 2427.46   678.2 2438.42   695.1 2442.92
#Mann= 4 ,-1 , 0
       0     .06       0   30.06     .05       0   278.5    .045       0
   289.8     .05       0
Bank Sta=278.5,289.8
XS Rating Curve= 0 ,0
Exp/Cntr(USF)=0,0
Exp/Cntr=0.3,0.1

Type RM Length L Ch R = 1 ,33314   ,311.1,311.1,311.1
XS GIS Cut Line= 3
2423499.34038844536232.1665879562423878.41138437 535800.90465781
 2424147.6067293 535800.90465781
#Sta/Elev= 30
       0 2443.85     7.7 2442.72    17.2 2437.83    25.6 2435.02    62.2 2426.99
    80.4  2424.6  115.442421.236   177.3 2416.27   217.3  2413.9   361.1 2411.65
   369.52410.542   374.3  2409.9   383.3 2410.47   395.4 2411.29     441 2411.84
  501.442410.711   527.4 2409.68   531.5 2410.14   541.5 2413.33     553 2414.94
   565.1 2415.24   574.2 2417.61   592.2  2424.1   628.2  2439.7   648.2 2449.15
   676.2 2456.96   692.2 2460.14   736.1 2465.97  819.142471.773   843.4 2473.19
#Mann= 6 ,-1 , 0
       0     .06       0  115.44     .05       0   369.5    .045       0
   383.3     .05       0  501.44      .1       0  819.14     .12       0
Bank Sta=369.5,383.3
XS Rating Curve= 0 ,0
Exp/Cntr(USF)=0,0
Exp/Cntr=0.3,0.1

Type RM Length L Ch R = 1 ,33003   ,323.2,323.2,323.2
XS GIS Cut Line= 2
2423664.15386493536405.220738269 2424169.5818595535858.589374581
#Sta/Elev= 30
       0 2441.95    16.8 2439.55   67.852433.354   119.3  2427.7     153 2424.45
   253.7 2416.98   300.4 2414.56   320.2 2413.07   365.5 2410.53     409 2408.62
   436.3 2408.16  454.712409.059   458.9 2408.96   473.1 2407.55   483.5 2407.29
   487.2 2407.83   490.1 2409.29   496.1 2416.67   498.5 2419.25     507 2426.82
   518.8 2435.47   528.8 2441.86   535.3 2445.61   542.4  2448.9   563.6 2456.53
   583.6 2462.37   605.1 2465.98   654.1 2470.06   698.32472.237   744.5 2474.08
#Mann= 6 ,-1 , 0
       0     .06       0   67.85     .05       0  454.71      .1       0
   473.1    .045       0   487.2      .1       0   698.3     .12       0
Bank Sta=473.1,487.2
XS Rating Curve= 0 ,0
Exp/Cntr(USF)=0,0
Exp/Cntr=0.3,0.1

Type RM Length L Ch R = 1 ,32680   ,188.7,188.7,188.7
XS GIS Cut Line= 2
2423900.38651456536578.2748885822424375.59870511536042.631089994
#Sta/Elev= 30
       0 2433.93    3.392433.212    33.9 2427.23      50 2424.65   102.5 2417.86
   125.6 2415.71   156.9 2411.71   179.5 2410.49   292.8 2407.91   317.3 2406.86
     324 2405.17   329.6 2404.34   337.5  2405.2   343.5 2405.91   360.1 2406.75
   379.7 2406.03     392 2406.84   445.6 2406.22   470.1 2406.64   519.5 2406.68
   557.9  2408.5  572.852410.834     579 2412.65     590 2416.79   601.6 2422.16
   616.7 2427.51   661.1 2441.62     681 2447.13  701.03  2450.9   716.1 2454.33
#Mann= 6 ,-1 , 0
       0     .06       0    3.39     .05       0     324    .045       0
   337.5     .05       0  572.85      .1       0  701.03     .12       0
Bank Sta=324,337.5
XS Rating Curve= 0 ,0
Exp/Cntr(USF)=0,0
Exp/Cntr=0.3,0.1

Type RM Length L Ch R = 1 ,32491   ,263.4,263.4,263.4
XS GIS Cut Line= 2
2424045.88779955536679.3500750322424503.80260984536184.605655332
#Sta/Elev= 30
       0 2424.36    15.4  2420.6   23.432419.253    44.9 2415.45    62.5 2413.41
   156.3 2406.78   187.5 2405.81   266.7 2405.15   303.5 2402.89   308.6 2402.54
   315.7 2402.86   348.8 2405.24   374.3 2405.24   392.3 2404.59   405.4 2405.17
     428 2404.47   466.6  2404.8   504.2 2406.05  514.442407.367   524.3 2409.73
   538.4 2416.02   553.8 2424.06   575.2 2437.88   589.4 2445.35   602.8  2451.2
   610.1 2453.55   624.6 2456.38  653.642460.717   671.52462.674   674.1 2463.06
#Mann= 7 ,-1 , 0
       0     .06       0   23.43     .05       0   303.5    .045       0
   315.7     .05       0  514.44      .1       0  653.64     .12       0
   671.5      .1       0
Bank Sta=303.5,315.7
XS Rating Curve= 0 ,0
Exp/Cntr(USF)=0,0
Exp/Cntr=0.3,0.1

Type RM Length L Ch R = 1 ,32228   ,465.7,465.7,465.7
XS GIS Cut Line= 2
2424221.77279372536852.9640160632424658.52850641 536383.24560807
#Sta/Elev= 30
       0 2428.13    18.9 2424.49    33.2  2420.4    43.8  2417.9    62.5 2414.67
   103.9 2410.74   120.8 2409.89   168.3 2406.35   207.7 2402.69   218.6 2402.15
   284.1 2402.67   297.5 2402.37   330.2 2403.05   333.3 2402.93   339.72401.796
   344.3 2401.13   352.8 2401.82   356.2 2402.36   371.5 2403.06   450.2 2402.22
     466 2405.39   485.4 2406.87   491.7 2407.91   503.1 2411.31   521.62419.218
   557.2 2434.68   587.7 2446.38   596.2 2448.64   608.8 2450.87   641.4 2454.39
#Mann= 4 ,-1 , 0
       0     .05       0   339.7    .045       0   352.8     .05       0
   521.6      .1       0
Bank Sta=339.7,352.8
XS Rating Curve= 0 ,0
Exp/Cntr(USF)=0,0
Exp/Cntr=0.3,0.1