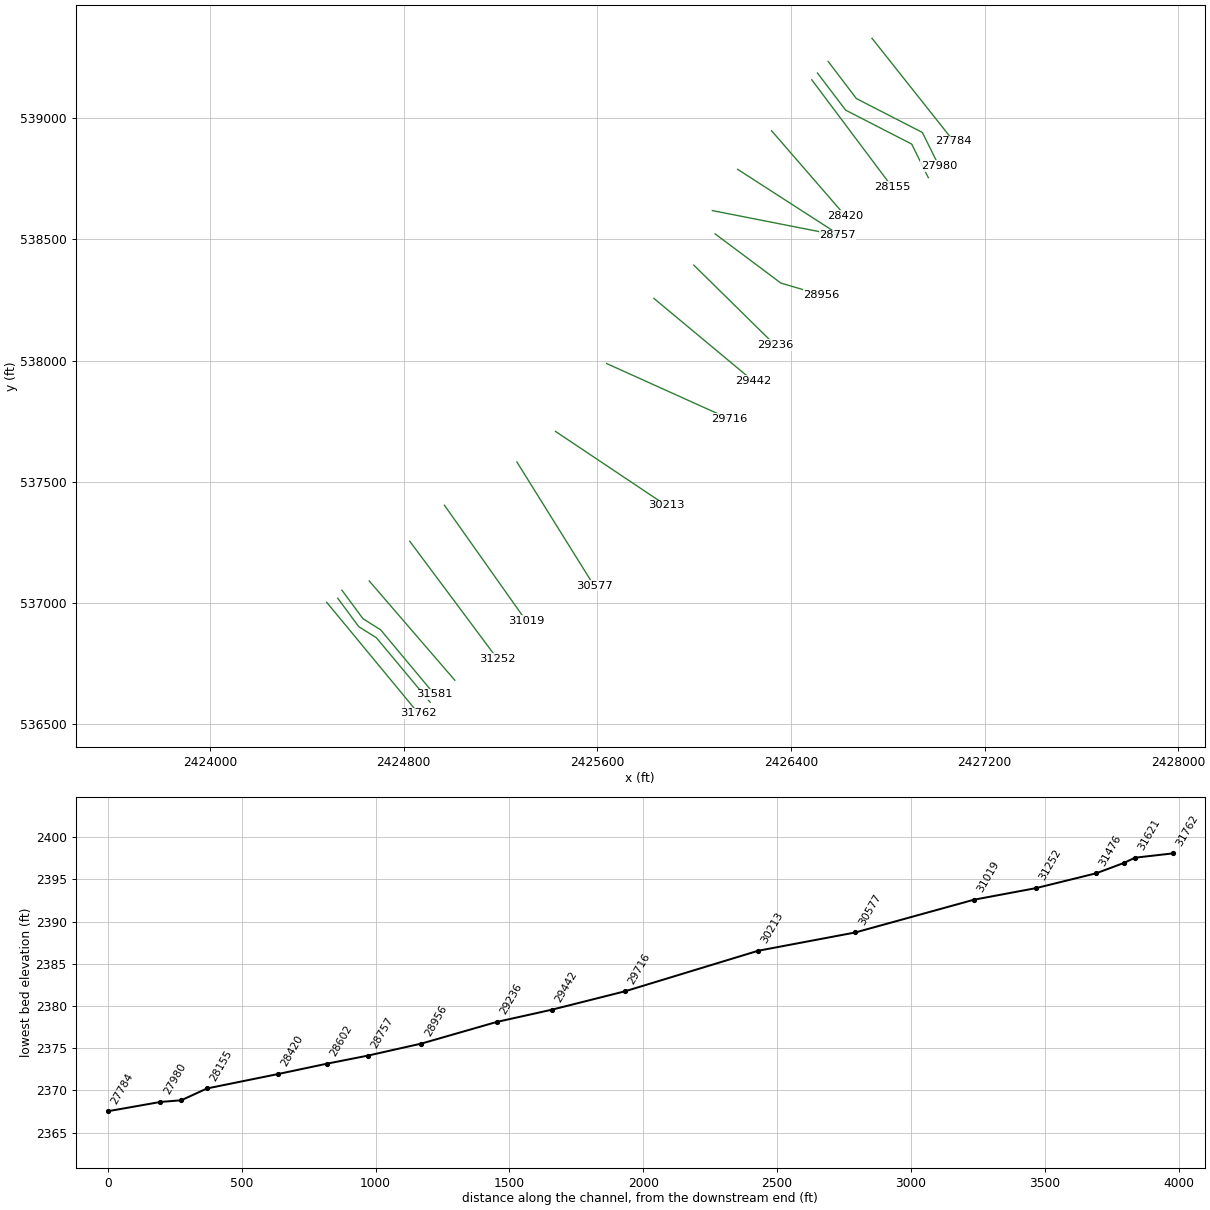
HEC-RAS study WHITHORNCK.prj: WHITHORNCK

--- WHITHORNCK.g01 (geometry) --- (continued)

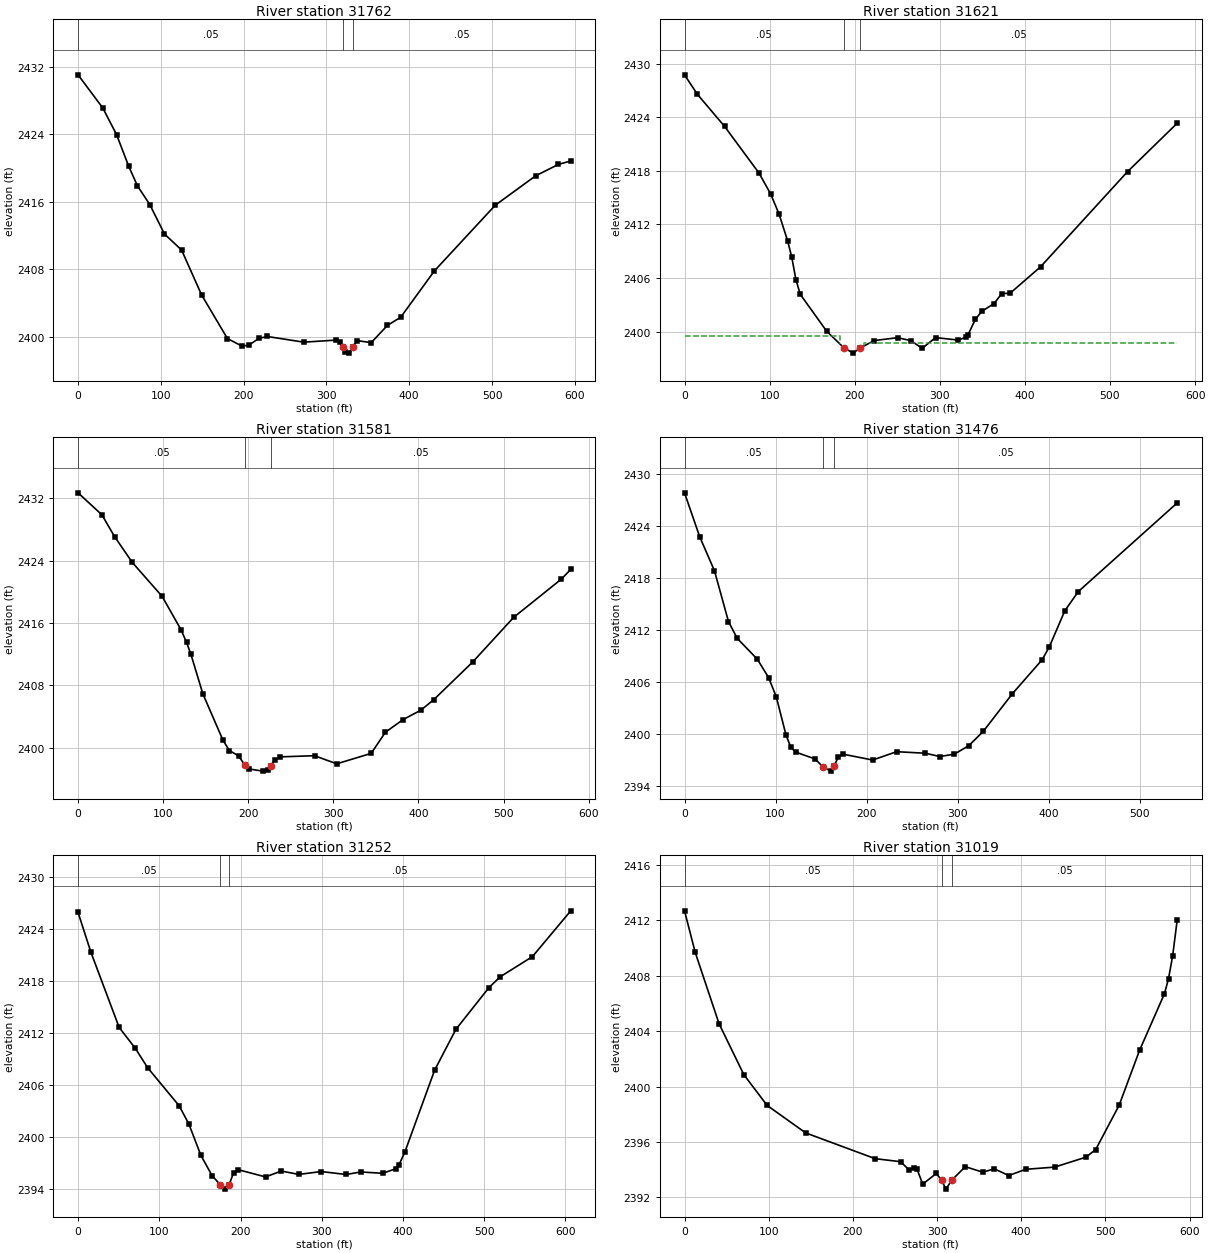
Type RM Length L Ch R = 1 ,31762   ,140.8,140.8,140.8
XS GIS Cut Line= 2
2424482.72746482537001.2961449032424861.79846075536542.565302009
#Sta/Elev= 30
       0 2431.06    29.9 2427.13    46.5 2423.98    61.1 2420.25    71.6 2417.93
    86.7 2415.68   104.4  2412.2   125.1  2410.3   149.2 2404.99   180.4 2399.82
   197.8 2398.93     206 2399.02   218.5 2399.84   228.6 2400.06   272.5 2399.39
   311.1 2399.63   316.5 2399.39   319.6 2398.84   322.7 2398.24   327.5 2398.09
   332.6 2398.86   336.7 2399.58   354.1 2399.33   373.6 2401.37   389.7 2402.34
   430.4 2407.83   503.9 2415.61   552.6 2419.09   580.2 2420.45   595.1 2420.85
#Mann= 3 ,-1 , 0
       0     .05       0   319.6    .045       0   332.6     .05       0
Bank Sta=319.6,332.6
XS Rating Curve= 0 ,0
Exp/Cntr(USF)=0,0
Exp/Cntr=0.5,0.3

Type RM Length L Ch R = 1 ,31621   ,40.3,40.3,40.3
XS GIS Cut Line= 4
2424528.35568278537018.1824815762424615.51909171536900.327731473
2424687.95065687536854.9045465382424910.15596696536588.503705162
#Sta/Elev= 30
       0 2428.76    15.2 2426.57      47 2422.99    87.4 2417.77   101.2 2415.42
   111.1 2413.16   121.1 2410.18     126 2408.34     131 2405.77     136 2404.17
   167.1 2400.03   187.4 2398.17   198.3 2397.58   205.8 2398.13   223.1 2398.99
   250.4 2399.31     266 2398.98   279.2 2398.12   295.1 2399.32   321.8 2399.04
   330.3 2399.35   333.2 2399.64   341.7 2401.35   349.3 2402.26   363.8 2403.14
   372.9 2404.26   382.5 2404.28   418.4 2407.25   520.6 2417.91     579 2423.34
#Mann= 3 ,-1 , 0
       0     .05       0   187.4    .045       0   205.8     .05       0
#XS Ineff= 2 , 0
          182.81  2399.5  210.89          2398.7
Permanent Ineff=
       F       F
Bank Sta=187.4,205.8
XS Rating Curve= 0 ,0
Exp/Cntr(USF)=0,0
Exp/Cntr=0.5,0.3

Type RM Length L Ch R = 1 ,31581   ,105,105,105
XS GIS Cut Line= 4
2424545.54283383537051.3291300422424632.70624276 536933.47437994
2424705.13780793536888.0511950042424927.34311802536621.650353628
#Sta/Elev= 30
       0 2432.72      28  2429.9    42.9  2427.1    63.8 2423.77    98.8 2419.42
     121 2415.13   127.5 2413.51   132.5 2412.03   146.6 2406.92   170.3 2400.94
   177.9 2399.61   188.6 2398.93   196.1 2397.74   200.5 2397.26   216.9 2396.97
     223 2397.12   226.4  2397.6   230.9 2398.38     237  2398.8   277.9 2398.95
     304 2397.91   344.5 2399.25   361.2 2401.97   382.1  2403.6   402.9  2404.8
   418.1 2406.16   463.8 2410.99     512 2416.73     568 2421.64     579 2422.89
#Mann= 3 ,-1 , 0
       0     .05       0   196.1    .045       0   226.4     .05       0
Bank Sta=196.1,226.4
XS Rating Curve= 0 ,0
Exp/Cntr(USF)=0,0
Exp/Cntr=0.5,0.3

Type RM Length L Ch R = 1 ,31476   ,223.7,223.7,223.7
XS GIS Cut Line= 2
2424658.48696935537089.3863930962425012.05121965536679.350075032
#Sta/Elev= 30
       0  2427.8    16.6 2422.76    32.9 2418.82    48.3 2412.97    57.9 2411.03
      80 2408.63    92.4 2406.51   100.8  2404.3   111.6 2399.86   116.9 2398.46
   122.2 2397.92   143.5 2397.13     152 2396.23   160.5 2395.73   164.4 2396.31
     169 2397.38   174.3 2397.68   206.7 2397.01   233.1 2397.97   264.8 2397.79
   280.6 2397.41   296.6 2397.69   312.3 2398.66   328.2  2400.3   359.8 2404.59
     393 2408.57   400.9 2410.06   417.9 2414.21   432.7 2416.42   541.4 2426.64
#Mann= 3 ,-1 , 0
       0     .05       0     152    .045       0   164.4     .05       0
Bank Sta=152,164.4
XS Rating Curve= 0 ,0
Exp/Cntr(USF)=0,0
Exp/Cntr=0.3,0.1

Type RM Length L Ch R = 1 ,31252   ,232.7,232.7,232.7
XS GIS Cut Line= 2
2424825.87361255537253.3806611342425188.46326083536767.180905492
#Sta/Elev= 30
       0 2425.94    15.7 2421.37    50.6 2412.65    70.6 2410.23    85.5 2408.02
   124.5  2403.6   136.5 2401.48   151.2 2397.88     165 2395.54   175.3 2394.46
   180.3 2393.98   185.92394.472   191.4 2395.86   196.5 2396.24   230.8 2395.39
   250.2 2396.07   271.7 2395.68   299.4 2396.01     330 2395.67   347.9 2395.96
   374.9 2395.81   390.8 2396.32   394.9 2396.75   402.2 2398.24   438.9 2407.71
   465.1 2412.43   505.8 2417.25   519.6  2418.5   559.3 2420.83   606.5 2426.12
#Mann= 3 ,-1 , 0
       0     .05       0   175.3    .045       0   185.9     .05       0
Bank Sta=175.3,185.9
XS Rating Curve= 0 ,0
Exp/Cntr(USF)=0,0
Exp/Cntr=0.3,0.1

Type RM Length L Ch R = 1 ,31019   ,442.9,442.9,442.9
XS GIS Cut Line= 2
2424968.92722047537402.3422710252425306.79484727536924.383189208
#Sta/Elev= 30
       0 2412.69    12.7 2409.69    41.1 2404.53    70.5 2400.86    98.2 2398.64
   143.9 2396.66   226.4  2394.8   256.6 2394.58   266.4 2394.01   273.2 2394.16
   276.1 2394.06     283 2392.96   299.1 2393.73   305.6 2393.23   310.5  2392.6
   317.6 2393.25   333.5 2394.22   354.5 2393.82   367.9 2394.07   385.2 2393.58
   405.2 2394.03   439.7 2394.19     477 2394.91   488.5 2395.46   516.2 2398.64
   540.7 2402.64   570.1  2406.7     575  2407.8   579.9 2409.45   585.3 2412.04
#Mann= 3 ,-1 , 0
       0     .05       0   305.6    .045       0   317.6     .05       0
Bank Sta=305.6,317.6
XS Rating Curve= 0 ,0
Exp/Cntr(USF)=0,0
Exp/Cntr=0.3,0.1

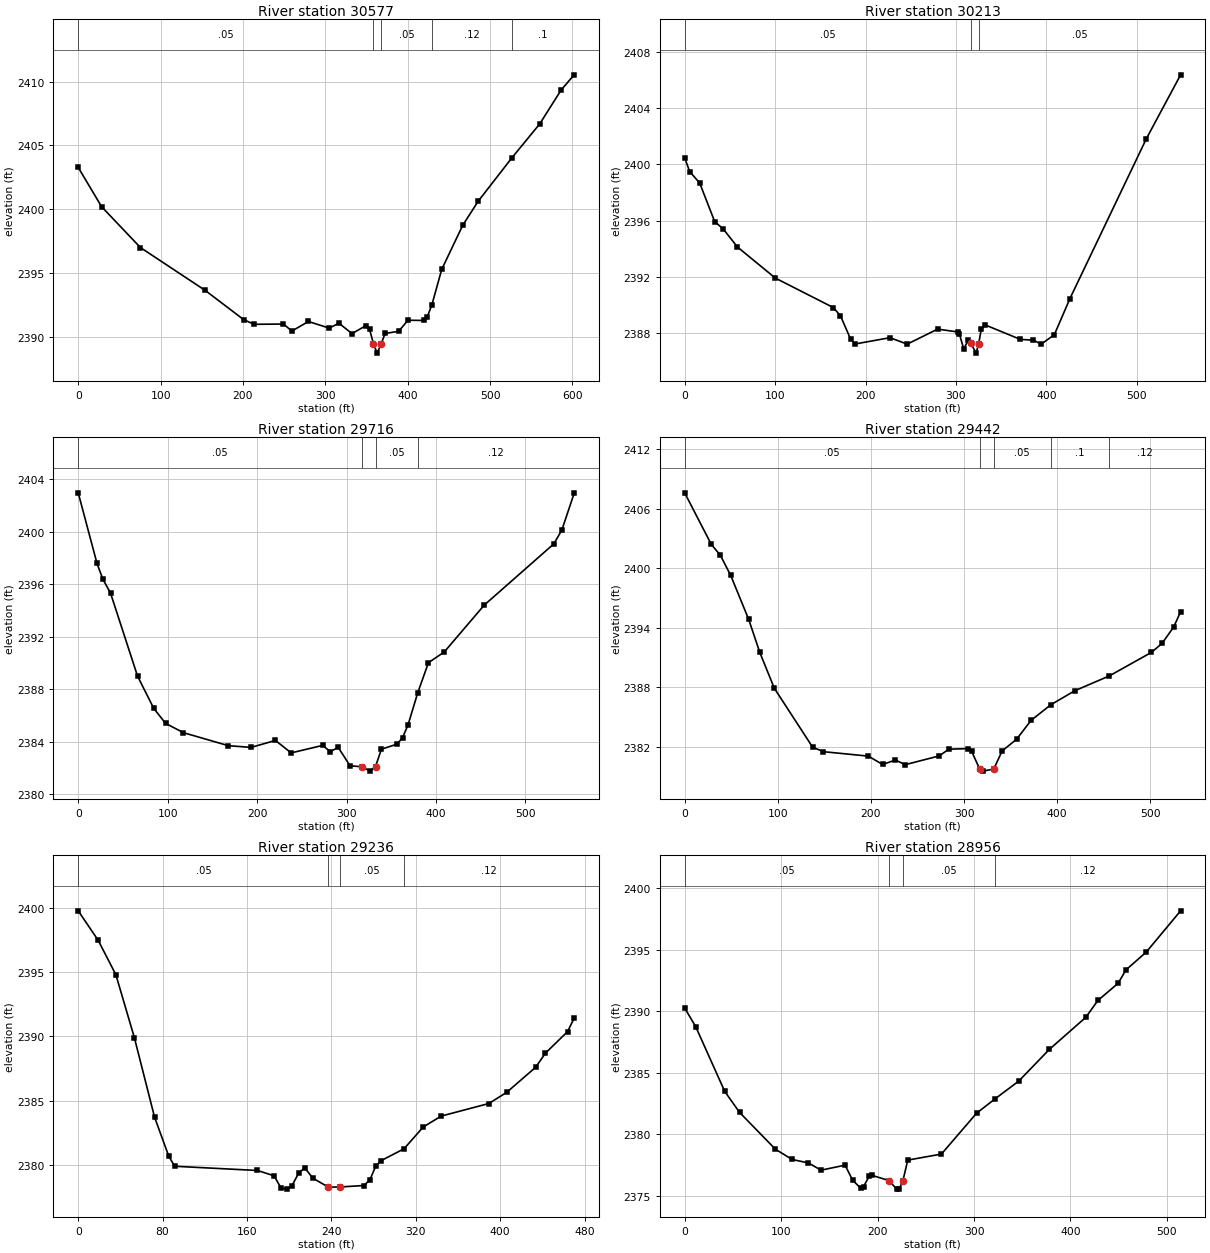
Type RM Length L Ch R = 1 ,30577   ,363.2,363.2,363.2
XS GIS Cut Line= 2
2425268.33836942537580.890203888 2425586.9777573537069.968426773
#Sta/Elev= 30
       0 2403.28    28.4  2400.2    75.5    2397   153.9 2393.65     201 2391.34
   213.6 2390.98   249.2    2391   259.4 2390.45   279.5  2391.2   304.8 2390.68
   316.5 2391.07   332.4 2390.25   348.9 2390.86   353.7 2390.59   358.4 2389.46
   362.9 2388.72   367.8 2389.44   372.5 2390.26     389 2390.43   400.4  2391.3
   419.6 2391.28   423.9 2391.58  429.422392.515   441.3 2395.28   466.8 2398.74
   485.6 2400.63  526.522404.033   560.3 2406.69   586.4 2409.36   602.1 2410.54
#Mann= 5 ,-1 , 0
       0     .05       0   358.4    .045       0   367.8     .05       0
  429.42     .12       0  526.52      .1       0
Bank Sta=358.4,367.8
XS Rating Curve= 0 ,0
Exp/Cntr(USF)=0,0
Exp/Cntr=0.3,0.1

Type RM Length L Ch R = 1 ,30213   ,496.8,496.8,496.8
XS GIS Cut Line= 2
2425427.65806336537707.2472025292425883.64201498537402.342271025
#Sta/Elev= 30
       0 2400.47     5.5 2399.49    16.6 2398.67    33.2 2395.92    42.6  2395.4
    58.4 2394.11   100.2  2391.9   164.3  2389.8   172.3 2389.21   183.5 2387.55
   188.3  2387.2   227.1 2387.65   246.1 2387.19   279.7 2388.26   302.1 2388.06
   303.8 2387.92   308.6 2386.86   313.6 2387.46   316.5 2387.25   322.3 2386.55
   325.1 2387.21     328 2388.24   332.7 2388.55   371.2 2387.53   385.7 2387.47
   394.3 2387.19   408.8 2387.86   426.1 2390.44   510.7 2401.84   548.5 2406.38
#Mann= 3 ,-1 , 0
       0     .05       0   316.5    .045       0   325.1     .05       0
Bank Sta=316.5,325.1
XS Rating Curve= 0 ,0
Exp/Cntr(USF)=0,0
Exp/Cntr=0.3,0.1

Type RM Length L Ch R = 1 ,29716   ,274.3,274.3,274.3
XS GIS Cut Line= 2
2425639.16869152 537987.430112562426144.59668609537759.438136751
#Sta/Elev= 30
       0 2402.97      21 2397.59    27.5 2396.39    36.1 2395.33    66.3    2389
    84.5 2386.53    97.7 2385.39   117.7 2384.68   167.9 2383.69   193.3 2383.56
   220.5 2384.09   238.1 2383.14   273.2 2383.71   281.9 2383.24   290.7 2383.56
   303.9 2382.16   317.3 2382.08   326.4 2381.75   332.4  2382.1     339 2383.42
   356.6 2383.81   362.6  2384.3   368.7 2385.26  379.682387.735   391.6 2390.02
   409.2 2390.83     454 2394.41   531.8 2399.08   540.8 2400.14   554.5 2402.94
#Mann= 4 ,-1 , 0
       0     .05       0   317.3    .045       0   332.4     .05       0
  379.68     .12       0
Bank Sta=317.3,332.4
XS Rating Curve= 0 ,0
Exp/Cntr(USF)=0,0
Exp/Cntr=0.3,0.1

Type RM Length L Ch R = 1 ,29442   ,205.7,205.7,205.7
XS GIS Cut Line= 2
2425834.19797203538256.6254574912426243.48477198537916.010939415
#Sta/Elev= 30
       0 2407.61    28.6 2402.41    38.3 2401.32    49.4 2399.29    68.7 2394.86
    80.6 2391.54    96.2 2387.92   137.4 2381.97     149 2381.52   197.3 2381.07
   212.5 2380.23   226.3 2380.68   236.7 2380.21   273.2 2381.09   283.6 2381.77
   304.4 2381.83   308.1 2381.56   316.6  2379.8     320 2379.56   331.92379.769
   340.8 2381.59   356.3 2382.77     372 2384.68  392.992386.241   418.8 2387.66
  456.082389.163   501.2 2391.53   512.5 2392.43   525.1 2394.09   532.5 2395.63
#Mann= 5 ,-1 , 0
       0     .05       0   316.6    .045       0   331.9     .05       0
  392.99      .1       0  456.08     .12       0
Bank Sta=316.6,331.9
XS Rating Curve= 0 ,0
Exp/Cntr(USF)=0,0
Exp/Cntr=0.3,0.1

Type RM Length L Ch R = 1 ,29236   ,280.9,280.9,280.9
XS GIS Cut Line= 2
2425999.01144852538393.9700212322426334.13218405538064.343068255
#Sta/Elev= 30
       0 2399.76    18.9 2397.47    35.7 2394.79    53.2  2389.9    72.4  2383.7
    85.8 2380.68    91.4 2379.89   169.9 2379.56   185.6 2379.15   192.4 2378.18
     198 2378.11   202.5 2378.36   209.2 2379.39   214.8 2379.76   222.3 2378.97
   237.2 2378.26   248.5 2378.28   270.9 2378.39   276.5 2378.84   282.1 2379.91
     287 2380.32  308.872381.251     327 2382.94     344 2383.79   389.2 2384.77
   406.2 2385.64   433.6 2387.59   442.9 2388.69   463.8 2390.36   470.1 2391.41
#Mann= 4 ,-1 , 0
       0     .05       0   237.2    .045       0   248.5     .05       0
  308.87     .12       0
Bank Sta=237.2,248.5
XS Rating Curve= 0 ,0
Exp/Cntr(USF)=0,0
Exp/Cntr=0.3,0.1

Type RM Length L Ch R = 1 ,28956   ,199,199,199
XS GIS Cut Line= 3
2426086.91196931538523.0739111482426358.85420552538319.803956812
2426526.41457328538270.359913865
#Sta/Elev= 30
       0 2390.28    11.5 2388.75    41.5  2383.5    56.9 2381.79      94  2378.8
   111.4 2377.96   128.3 2377.68   141.4 2377.09   166.3  2377.5   174.1 2376.28
   182.6 2375.62   185.5 2375.76   191.3  2376.6   194.1 2376.67   211.8 2376.25
   219.8 2375.55   222.6 2375.58   226.3 2376.25   231.3 2377.91   266.2  2378.4
   302.6 2381.72  321.78 2382.89   346.3 2384.33   378.2 2386.92   415.9 2389.52
   428.4 2390.89   449.3 2392.28   457.6 2393.38   478.5 2394.82   514.2 2398.18
#Mann= 4 ,-1 , 0
       0     .05       0   211.8    .045       0   226.3     .05       0
  321.78     .12       0
Bank Sta=211.8,226.3
XS Rating Curve= 0 ,0
Exp/Cntr(USF)=0,0
Exp/Cntr=0.3,0.1

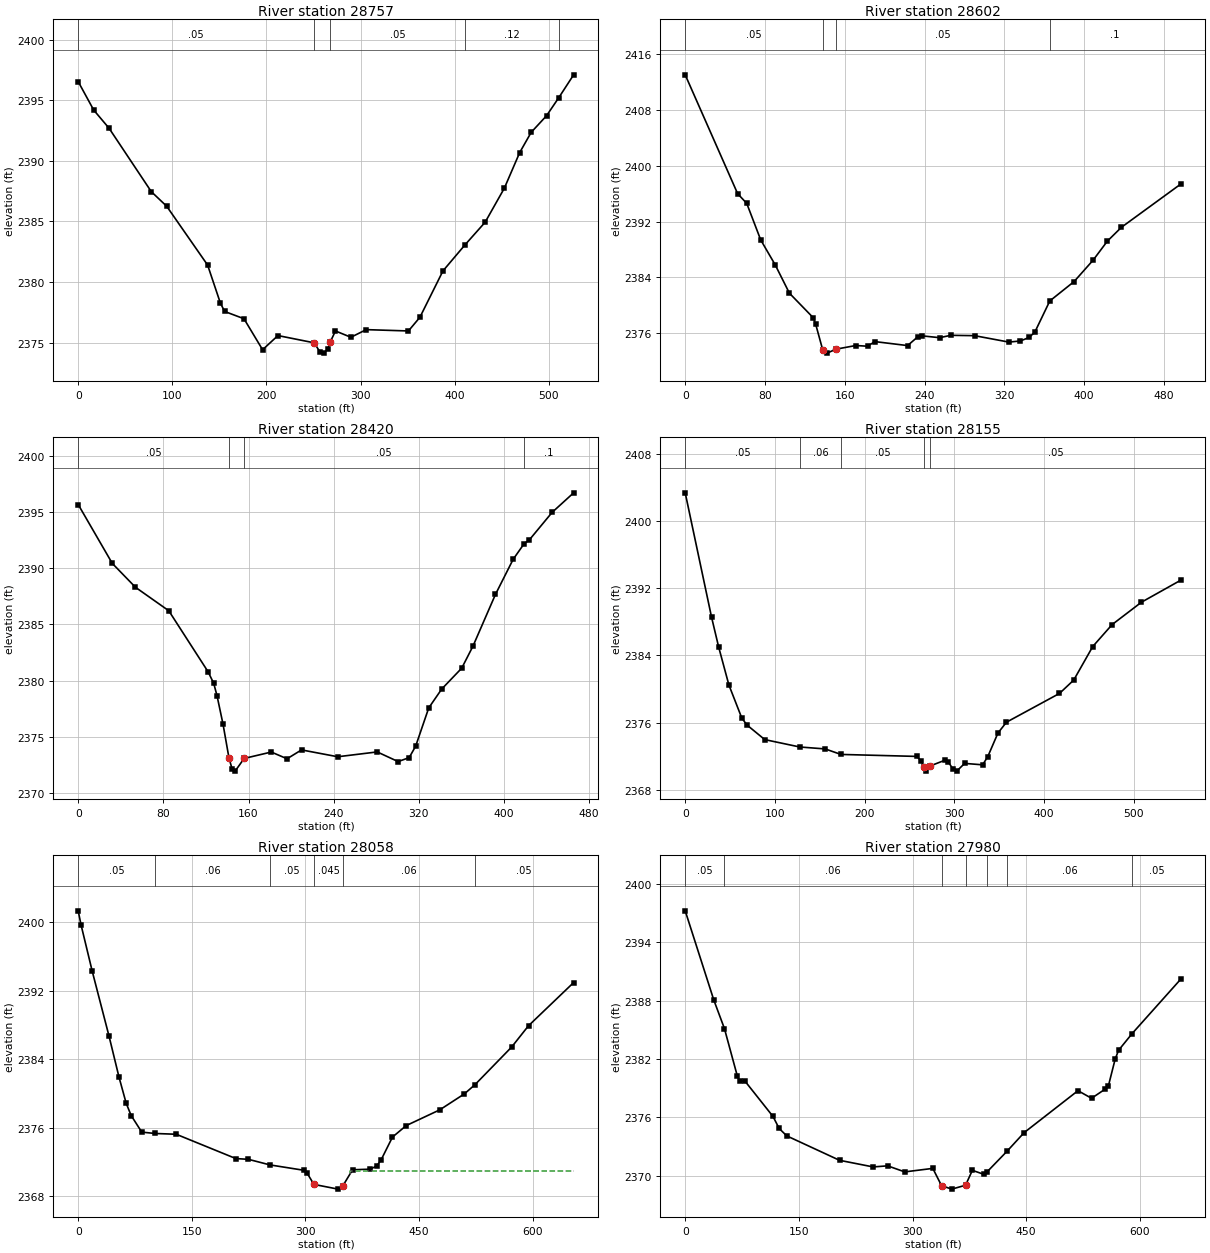
Type RM Length L Ch R = 1 ,28757   ,154.9,154.9,154.9
XS GIS Cut Line= 2
2426075.92440422538619.2151057672426592.33996388538517.580128598
#Sta/Elev= 30
       0 2396.55    16.5  2394.2    32.8  2392.7    77.7 2387.46      94 2386.26
   137.5  2381.4   151.1 2378.25   155.6 2377.57   176.1 2376.97   195.9 2374.41
   212.2 2375.58   250.8 2374.98     257  2374.2     261 2374.13   265.2 2374.48
     268 2375.09   273.3 2375.96   289.7 2375.44     306 2376.07   350.8 2375.96
     363 2377.09   387.5 2380.92  411.042383.082   432.3 2384.94   452.7 2387.75
     469 2390.69   481.2 2392.36   497.5 2393.73  510.412395.211   526.3 2397.11
#Mann= 5 ,-1 , 0
       0     .05       0   250.8    .045       0     268     .05       0
  411.04     .12       0  510.41      .1       0
Bank Sta=250.8,268
XS Rating Curve= 0 ,0
Exp/Cntr(USF)=0,0
Exp/Cntr=0.3,0.1

Type RM Length L Ch R = 1 ,28602   ,181.5,181.5,181.5
XS GIS Cut Line= 2
2426180.30627266538789.5223648052426597.83374643538520.327019873
#Sta/Elev= 30
       0    2413    52.6 2395.98    61.7  2394.6    75.7 2389.37    90.2 2385.81
   104.5 2381.74   128.3 2378.24   130.7 2377.37   137.8 2373.67   142.3 2373.16
     151 2373.72   171.1 2374.25   182.8 2374.15   190.2 2374.81     223 2374.24
     233 2375.47   237.7 2375.63   255.1 2375.37   266.3 2375.71   290.1 2375.66
   324.6 2374.74   336.1  2374.9   344.8  2375.4   350.6 2376.17  365.612380.631
     390 2383.41   409.1 2386.48   423.3 2389.19   437.4 2391.17   496.8 2397.35
#Mann= 4 ,-1 , 0
       0     .05       0   137.8    .045       0     151     .05       0
  365.61      .1       0
Bank Sta=137.8,151
XS Rating Curve= 0 ,0
Exp/Cntr(USF)=0,0
Exp/Cntr=0.3,0.1

Type RM Length L Ch R = 1 ,28420   ,265.6,265.6,265.6
XS GIS Cut Line= 2
2426320.39772767538948.8420587442426625.30265918538597.239975568
#Sta/Elev= 30
       0 2395.68      32 2390.44    53.8 2388.31    85.1 2386.22     122 2380.79
   127.3 2379.76   130.4 2378.66   136.1  2376.1   141.7 2373.08   144.6 2372.13
   147.4 2371.94   155.9 2373.07   181.4 2373.64   196.2 2373.04   209.8 2373.83
   243.8 2373.22   280.9 2373.65   300.5 2372.79   310.9 2373.14     317 2374.16
   329.3 2377.57   341.5 2379.25   360.3 2381.11   370.9 2383.08     392 2387.68
   408.6  2390.8   418.92392.189   423.8 2392.53   445.2 2394.98   465.4 2396.72
#Mann= 4 ,-1 , 0
       0     .05       0   141.7    .045       0   155.9     .05       0
   418.9      .1       0
Bank Sta=141.7,155.9
XS Rating Curve= 0 ,0
Exp/Cntr(USF)=0,0
Exp/Cntr=0.3,0.1

Type RM Length L Ch R = 1 ,28155   ,96.1,96.1,96.1
XS GIS Cut Line= 2
2426486.46324958539159.2104417652426817.92973424538717.255128882
#Sta/Elev= 30
       0 2403.33    29.4 2388.53    37.3 2384.99    48.7 2380.48      63 2376.57
    68.7 2375.73    88.7 2373.98  127.722373.101   156.1 2372.87  173.642372.216
   258.2 2371.98     263 2371.45   265.9 2370.77   268.7  2370.3   273.2 2370.85
   289.4 2371.52   293.2 2371.36   298.2 2370.52   302.7 2370.23   311.6 2371.15
   331.6 2370.98   337.3 2371.94   348.7 2374.76   358.2 2376.05   417.3 2379.47
   433.2 2381.06   454.4 2385.05     476 2387.66   508.7 2390.32   552.4 2392.93
#Mann= 5 ,-1 , 0
       0     .05       0  127.72     .06       0  173.64     .05       0
   265.9    .045       0   273.2     .05       0
Bank Sta=265.9,273.2
XS Rating Curve= 0 ,0
Exp/Cntr(USF)=0,0
Exp/Cntr=0.5,0.3

Type RM Length L Ch R = 1 ,28058   ,78,78,78
XS GIS Cut Line= 4
2426509.78866887539187.4464756432426626.41576532539033.989769781
2426898.95487493538894.0372540352426967.70347916538755.312391935
#Sta/Elev= 30
       0 2401.34     3.8 2399.69    18.6 2394.26    40.8 2386.67    53.8 2381.94
    63.3 2378.87    69.9 2377.43    83.9 2375.49  101.412375.331   129.4 2375.24
   208.1  2372.4   224.7 2372.31  253.162371.658     298 2371.03     302 2370.72
   311.12369.383     343 2368.83   349.5 2369.24   362.1 2371.09   385.1 2371.16
     394 2371.52     400 2372.28   414.8 2374.91   432.9 2376.25   477.2 2378.09
   509.6 2379.95   523.7 2381.03   572.1 2385.43   594.4 2387.92   653.9 2392.96
#Mann= 6 ,-1 , 0
       0     .05       0  101.41     .06       0  253.16     .05       0
   311.1    .045       0   349.5     .06       0   523.7     .05       0
#XS Ineff= 2 , 0
          302.58  2370.6  358.58          2370.9
Permanent Ineff=
       F       F
Bank Sta=311.1,349.5
XS Rating Curve= 0 ,0
Exp/Cntr(USF)=0,0
Exp/Cntr=0.5,0.3

Type RM Length L Ch R = 1 ,27980   ,196.3,196.3,196.3
XS GIS Cut Line= 4
2426553.98420016539235.3249678722426670.61129661 539081.86826201
2426943.15040622538941.9157462642427011.89901045538803.190884164
#Sta/Elev= 30
       0 2397.21    37.7 2388.06   51.792385.115    68.7 2380.27      72 2379.72
    78.8 2379.73   115.9 2376.09     124 2374.86     134  2374.1   203.7 2371.59
     248 2370.91   267.2 2371.02   289.8  2370.4   326.8 2370.76   338.3 2368.99
   351.8 2368.63     370 2369.03     379 2370.56   393.8 2370.16  398.592370.417
  424.99 2372.54   447.3 2374.43   518.4 2378.74   536.3 2377.96   554.1 2378.89
   558.6 2379.25   567.5 2381.99     572 2382.89   589.92384.608   653.9 2390.18
#Mann= 7 ,-1 , 0
       0     .05       0   51.79     .06       0   338.3    .045       0
     370     .06       0  398.59     .05       0  424.99     .06       0
   589.9     .05       0
Bank Sta=338.3,370
XS Rating Curve= 0 ,0
Exp/Cntr(USF)=0,0
Exp/Cntr=0.5,0.3

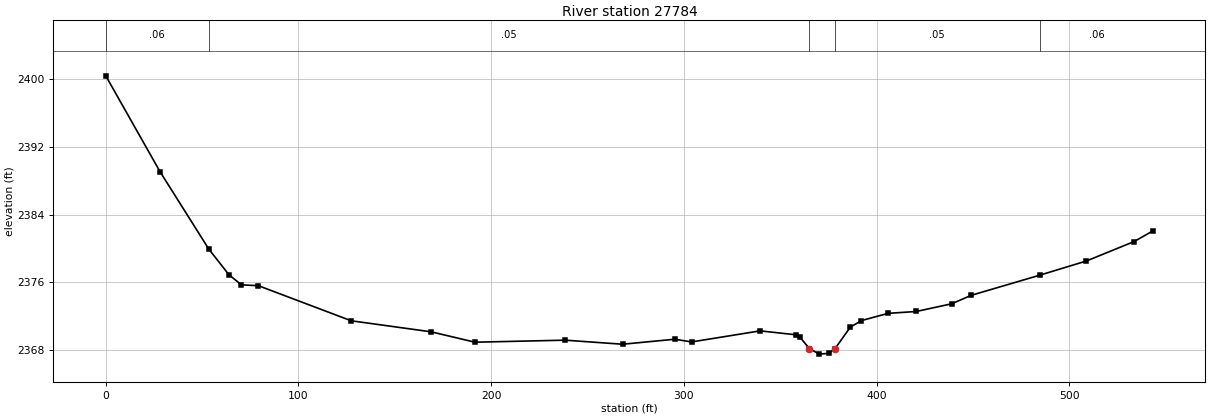
Type RM Length L Ch R = 1 ,27784   ,297.5,297.5,297.5
XS GIS Cut Line= 2
2426735.17831017539330.6599459432427073.04593697538904.891798347
#Sta/Elev= 30
       0 2400.43    28.2 2389.08   53.482379.943    63.9 2376.92    70.4 2375.72
    79.2 2375.62   127.4 2371.47   168.8 2370.17   191.6 2368.94   238.4 2369.18
   268.2  2368.7   295.3 2369.29     304 2368.97   339.6 2370.28     358 2369.82
   360.1 2369.57   365.2 2368.18   370.3 2367.53   375.1 2367.62   378.2  2368.1
   386.4 2370.72   392.1 2371.49     406 2372.35   420.6 2372.57     439 2373.48
   449.1 2374.48  484.622376.857   508.9 2378.54   533.7 2380.84   543.5 2382.11
#Mann= 5 ,-1 , 0
       0     .06       0   53.48     .05       0   365.2    .045       0
   378.2     .05       0  484.62     .06       0
Bank Sta=365.2,378.2
XS Rating Curve= 0 ,0
Exp/Cntr(USF)=0,0
Exp/Cntr=0.3,0.1