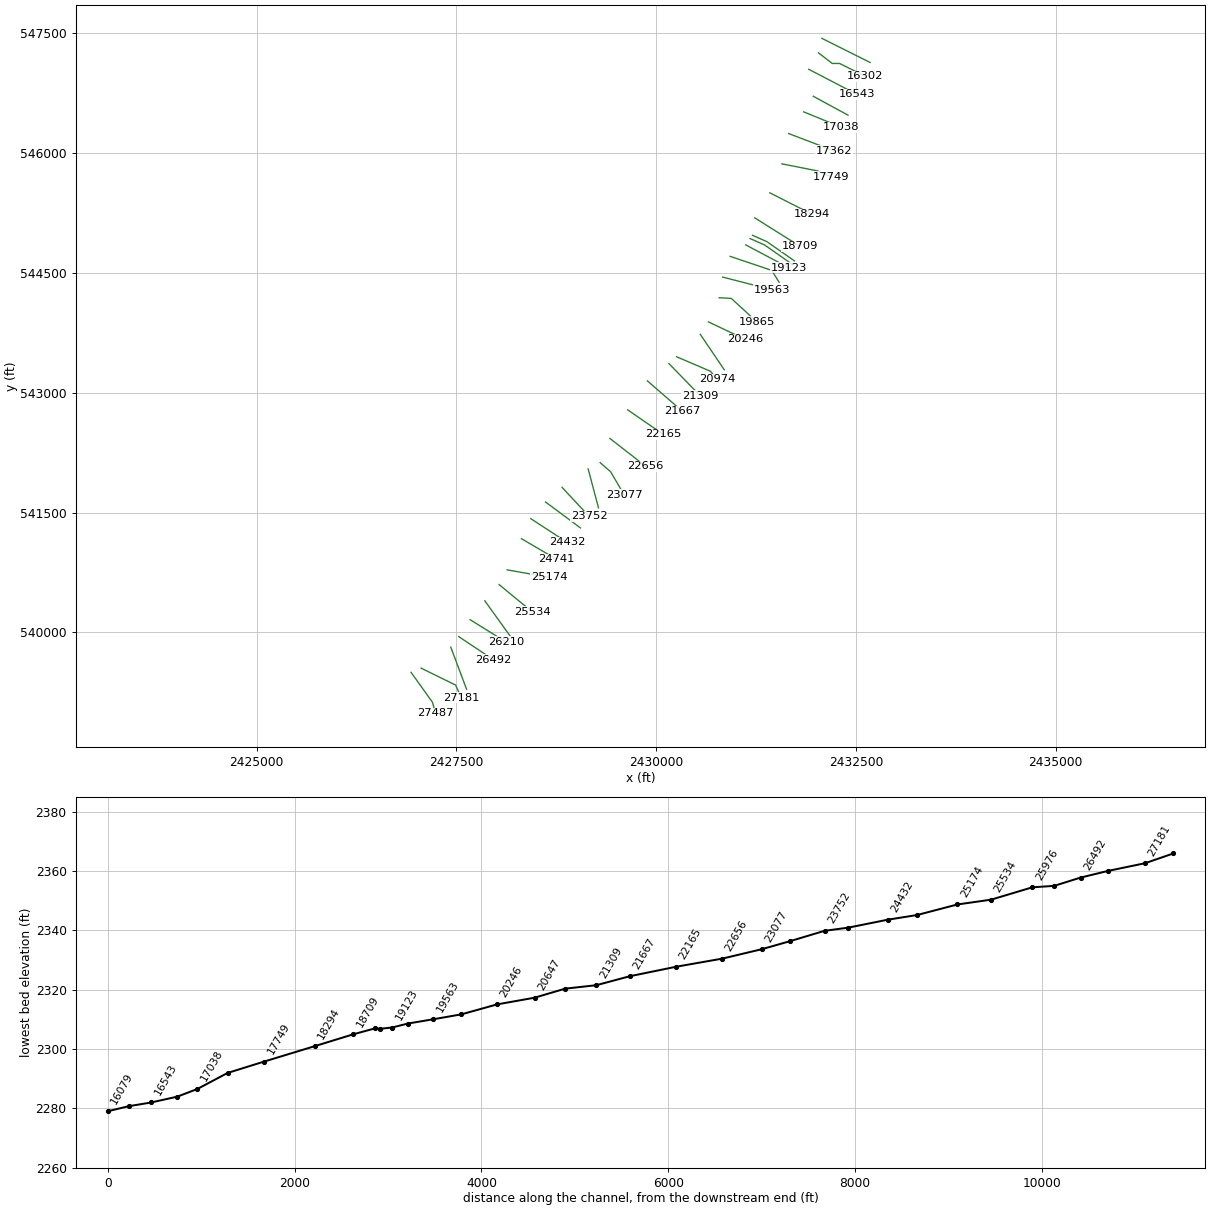
HEC-RAS study WHITHORNCK.prj: WHITHORNCK

--- WHITHORNCK.g01 (geometry) --- (continued)

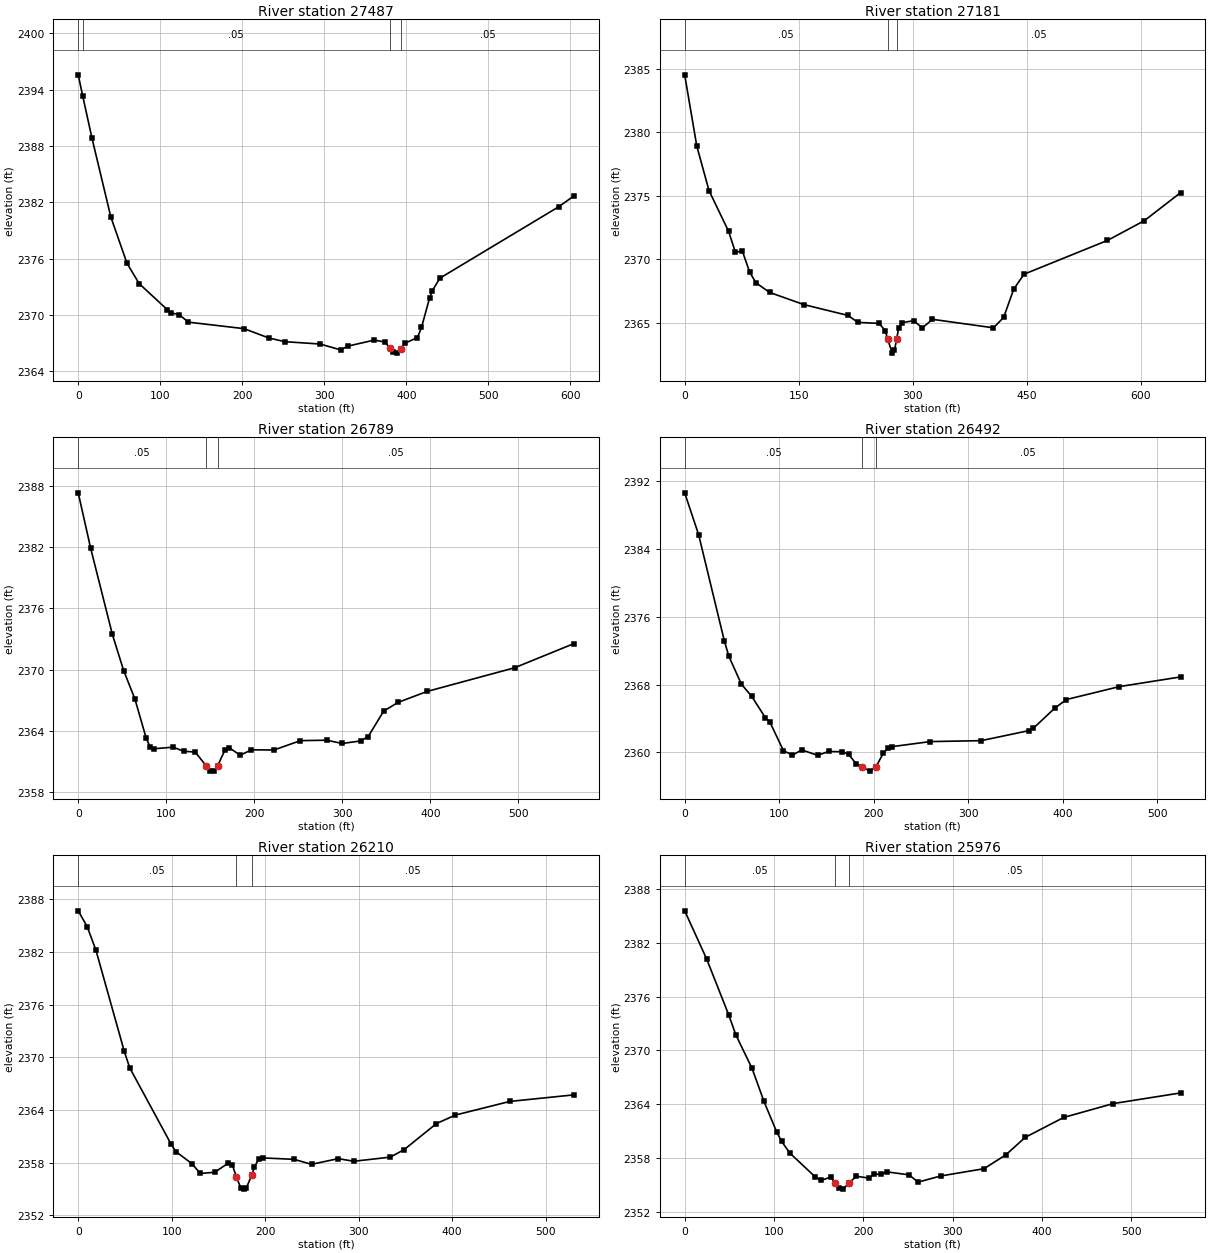
Type RM Length L Ch R = 1 ,27487   ,305.2,305.2,305.2
XS GIS Cut Line= 3
2426932.95448196539500.9672049812427202.14982689539124.643100332
2427237.85941346538987.298536591
#Sta/Elev= 30
       0 2395.59    5.572393.303    16.8 2388.83    39.8 2380.43    59.5  2375.5
    74.3 2373.34   108.6 2370.56   113.6 2370.21   122.9 2370.04   134.4 2369.23
   202.1 2368.54   232.2 2367.55   251.9 2367.15   294.9  2366.9   320.1 2366.27
   328.4 2366.67   360.9 2367.32   374.2 2367.11   379.92366.438   384.1 2366.05
     389 2365.93   393.9 2366.39   398.1 2366.98   413.6 2367.59   418.5 2368.67
   428.3 2371.79   431.6 2372.58   441.1 2373.93   585.6 2381.52   604.6  2382.7
#Mann= 4 ,-1 , 0
       0     .06       0    5.57     .05       0   379.9    .045       0
   393.9     .05       0
Bank Sta=379.9,393.9
XS Rating Curve= 0 ,0
Exp/Cntr(USF)=0,0
Exp/Cntr=0.3,0.1

Type RM Length L Ch R = 1 ,27181   ,392.7,392.7,392.7
XS GIS Cut Line= 3
 2427059.3114806539553.1581392022427490.57341074539341.647511042
2427561.99258389539185.074708378
#Sta/Elev= 30
       0 2384.51    15.9 2378.91      32  2375.4    57.8 2372.19    66.8 2370.53
    75.7 2370.67    85.5 2368.98    93.7 2368.15   111.6 2367.39   156.7 2366.43
   214.6 2365.58     228 2365.03   255.7 2364.95   263.7 2364.39     267 2363.72
     273 2362.61     276 2362.85     279 2363.76   281.5 2364.59   285.9 2365.01
   301.1 2365.16   312.7  2364.6     326 2365.27   406.2  2364.6   419.6 2365.42
   432.9 2367.65   446.4 2368.82   556.2 2371.48   604.6 2373.03   652.4 2375.24
#Mann= 3 ,-1 , 0
       0     .05       0     267    .045       0     279     .05       0
Bank Sta=267,279
XS Rating Curve= 0 ,0
Exp/Cntr(USF)=0,0
Exp/Cntr=0.3,0.1

Type RM Length L Ch R = 1 ,26789   ,296.3,296.3,296.3
XS GIS Cut Line= 2
 2427430.1418027539816.8597015842427627.91797448 539289.45657682
#Sta/Elev= 30
       0 2387.33    14.1 2381.91    38.8 2373.45    51.6 2369.91    64.4 2367.12
    77.2 2363.28    81.5 2362.45    85.8 2362.24   107.8  2362.4     120 2361.99
   132.8 2361.93   145.6 2360.54   149.9 2360.05   154.1 2360.08   158.4 2360.58
   166.9 2362.16   171.2 2362.36     184 2361.61   196.8 2362.14   222.3 2362.12
   252.4 2363.04   282.3 2363.08   299.9 2362.76   320.7 2363.01   329.3 2363.43
     347 2365.94   363.4 2366.79   396.2 2367.86   495.6 2370.18   563.3 2372.56
#Mann= 3 ,-1 , 0
       0     .05       0   145.6    .045       0   158.4     .05       0
Bank Sta=145.6,158.4
XS Rating Curve= 0 ,0
Exp/Cntr(USF)=0,0
Exp/Cntr=0.3,0.1

Type RM Length L Ch R = 1 ,26492   ,282.7,282.7,282.7
XS GIS Cut Line= 2
2427529.02988859539948.7104827752427965.78560129539657.540007645
#Sta/Elev= 30
       0 2390.66    14.8  2385.7      42 2373.15    46.8 2371.34      60 2368.06
    70.9 2366.62    85.3 2364.11    90.1 2363.59   104.5 2360.21   114.1 2359.66
   123.7 2360.29   140.7 2359.65   152.3  2360.1     167 2360.07   173.4 2359.77
   181.4 2358.67   187.8 2358.28   195.8 2357.78   202.2 2358.24   210.3 2359.91
   215.7 2360.53   219.9 2360.68   259.9 2361.27   313.8 2361.38   364.1 2362.56
   368.9 2362.83   391.6 2365.21   404.1 2366.24   460.2 2367.77   524.9 2368.91
#Mann= 3 ,-1 , 0
       0     .05       0   187.8    .045       0   202.2     .05       0
Bank Sta=187.8,202.2
XS Rating Curve= 0 ,0
Exp/Cntr(USF)=0,0
Exp/Cntr=0.3,0.1

Type RM Length L Ch R = 1 ,26210   ,233.9,233.9,233.9
XS GIS Cut Line= 2
2427671.86823488540160.2211109362428122.35840395539880.038200905
#Sta/Elev= 30
       0 2386.66     9.6 2384.86      19 2382.16    49.3 2370.66    55.1 2368.79
      99 2360.18   104.4 2359.27   121.8 2357.87   130.6 2356.77   146.1 2356.91
   160.3 2357.94     165 2357.71   169.22356.364   174.1 2355.09     177 2354.99
   179.9 2355.14   185.7 2356.59   188.5 2357.52   193.2 2358.41     198 2358.54
   230.9 2358.38   249.6 2357.81     278 2358.46   294.8 2358.16   333.8 2358.63
   348.7 2359.49   383.2 2362.45   403.5 2363.42   461.7 2364.97   530.5 2365.72
#Mann= 3 ,-1 , 0
       0     .05       0   169.2    .045       0   185.7     .05       0
Bank Sta=169.2,185.7
XS Rating Curve= 0 ,0
Exp/Cntr(USF)=0,0
Exp/Cntr=0.3,0.1

Type RM Length L Ch R = 1 ,25976   ,442.2,442.2,442.2
XS GIS Cut Line= 2
2427855.90995029540396.4537605692428180.04312072  539945.9635915
#Sta/Elev= 30
       0 2385.57    24.6 2380.19    49.3 2373.95    57.3 2371.71    75.4 2367.98
    88.7  2364.3   102.8 2360.92   108.4 2359.85   117.5 2358.54   146.2 2355.86
   152.7 2355.47   163.4 2355.85   168.72355.185   172.4 2354.58   177.4  2354.5
   183.62355.166   192.1 2355.94   206.3 2355.73   212.1 2356.19   219.2 2356.14
   226.1 2356.43   251.3 2356.09   261.1 2355.28   286.6 2355.97     335 2356.78
   359.7 2358.35   381.1 2360.28   424.1  2362.5   479.5 2364.05     555 2365.24
#Mann= 3 ,-1 , 0
       0     .05       0   168.7    .045       0   183.6     .05       0
Bank Sta=168.7,183.6
XS Rating Curve= 0 ,0
Exp/Cntr(USF)=0,0
Exp/Cntr=0.3,0.1

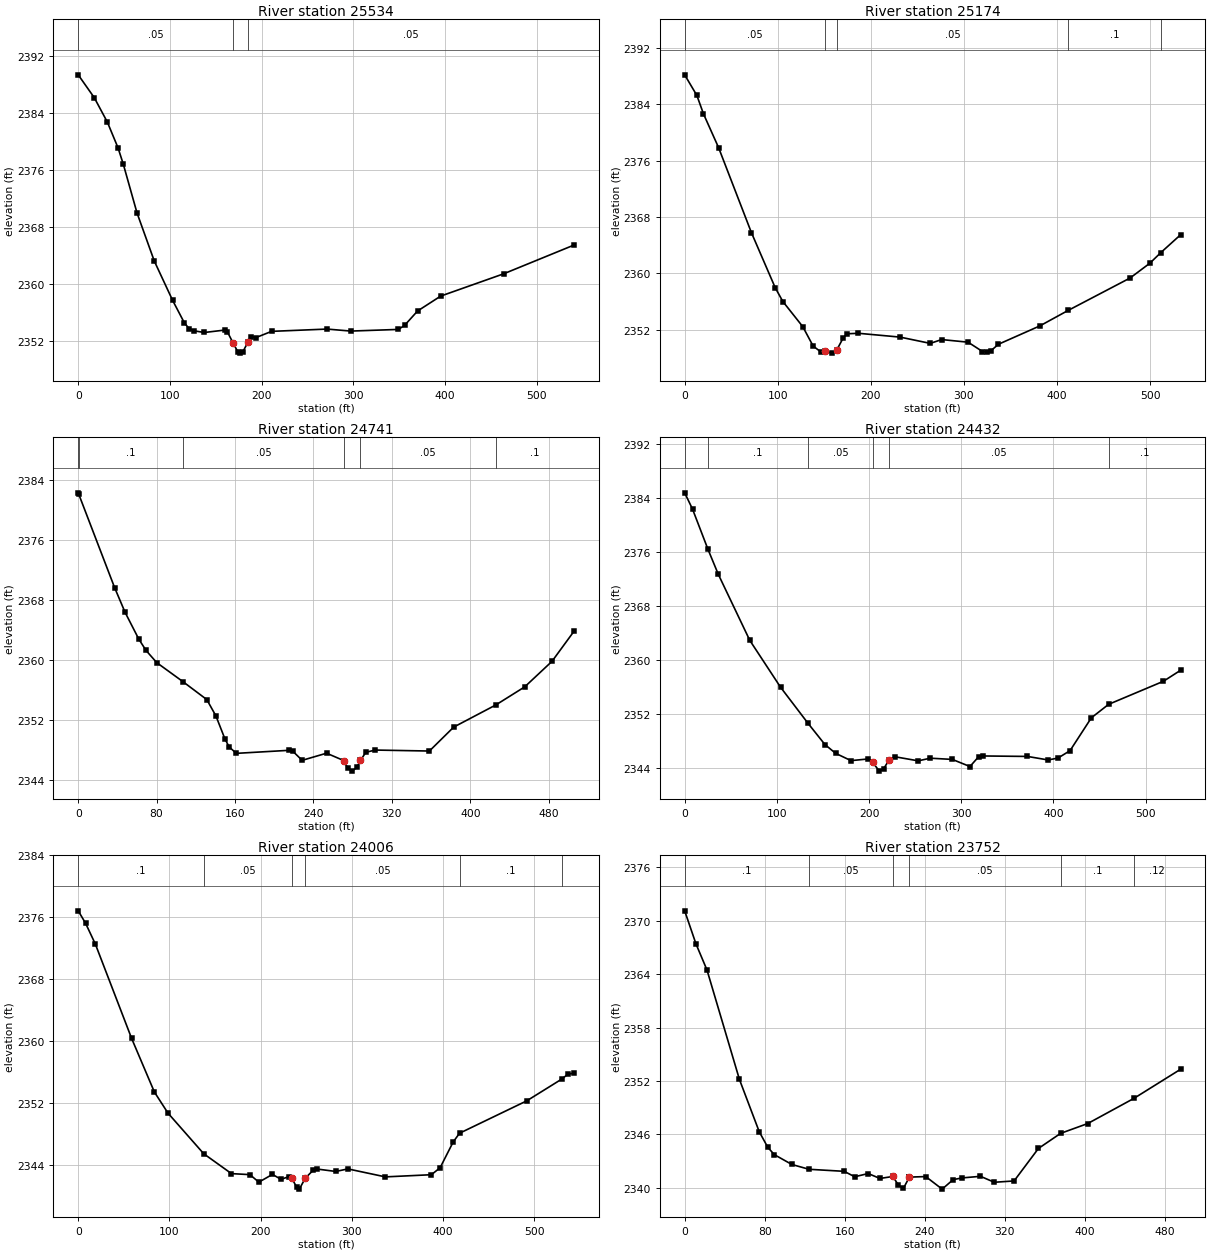
Type RM Length L Ch R = 1 ,25534   ,359.9,359.9,359.9
XS GIS Cut Line= 2
2428034.45788316540599.7237149052428451.98535693540256.362305554
#Sta/Elev= 30
       0 2389.32    17.5 2386.12    31.8 2382.69    43.4 2379.09    49.2 2376.78
    64.1 2369.97    82.9 2363.24   102.8 2357.75   115.8 2354.55     121 2353.75
   126.2 2353.46   137.4 2353.22   159.7 2353.56   162.6 2353.31   168.82351.759
   173.9 2350.53   176.7 2350.33   179.6 2350.55   185.2 2351.91   188.3 2352.64
   193.8 2352.51   210.8 2353.38   271.2  2353.7   297.1 2353.42   348.9 2353.65
   355.7 2354.21   369.9 2356.23   395.1 2358.32   463.7 2361.44   540.6 2365.48
#Mann= 3 ,-1 , 0
       0     .05       0   168.8    .045       0   185.2     .05       0
Bank Sta=168.8,185.2
XS Rating Curve= 0 ,0
Exp/Cntr(USF)=0,0
Exp/Cntr=0.3,0.1

Type RM Length L Ch R = 1 ,25174   ,433,433,433
XS GIS Cut Line= 2
2428136.09286032540783.7654303172428660.74909381540690.371126974
#Sta/Elev= 30
       0 2388.14    13.1 2385.22    20.2 2382.61    36.4 2377.84    71.7 2365.79
    97.3 2357.98   105.5 2356.03   126.9 2352.47     138 2349.73   146.1 2348.91
   150.72349.033   158.3 2348.72   163.22349.103   170.5 2350.92   174.5 2351.46
   186.7 2351.53   231.4 2350.99   263.9  2350.1   276.1 2350.64   304.5 2350.27
     320 2348.95   324.8 2348.91   328.9 2349.04   337.2 2349.98   381.7 2352.58
  412.142354.776   478.6 2359.36   499.8 2361.45  511.472362.938   532.9 2365.49
#Mann= 5 ,-1 , 0
       0     .05       0   150.7    .045       0   163.2     .05       0
  412.14      .1       0  511.47      .1       0
Bank Sta=150.7,163.2
XS Rating Curve= 0 ,0
Exp/Cntr(USF)=0,0
Exp/Cntr=0.3,0.1

Type RM Length L Ch R = 1 ,24741   ,308.7,308.7,308.7
XS GIS Cut Line= 2
2428314.64079319541173.8239913412428751.39650588540918.363102783
#Sta/Elev= 30
       0 2382.26     .352382.146    37.1 2369.63    47.8 2366.33    61.7 2362.78
    69.2 2361.24    80.2 2359.61  106.822357.084   131.2 2354.69   140.5 2352.51
   149.7 2349.44     154 2348.38   161.3 2347.52   214.6 2347.92   219.2 2347.77
   228.5 2346.59   253.4 2347.54   270.9 2346.56   274.9 2345.59   279.5 2345.15
   284.1 2345.64     288 2346.57   293.4 2347.66   303.1 2347.96   358.3 2347.83
   383.1 2351.02  426.212353.983   455.6 2356.39   483.4 2359.79     506 2363.83
#Mann= 6 ,-1 , 0
       0     .05       0     .35      .1       0  106.82     .05       0
   270.9    .045       0     288     .05       0  426.21      .1       0
Bank Sta=270.9,288
XS Rating Curve= 0 ,0
Exp/Cntr(USF)=0,0
Exp/Cntr=0.3,0.1

Type RM Length L Ch R = 1 ,24432   ,426.4,426.4,426.4
XS GIS Cut Line= 2
  2428432.757118541423.7910973492428883.24728707541129.873730944
#Sta/Elev= 30
       0 2384.72     8.5 2382.32   25.232376.385    36.5 2372.67    70.6 2362.93
     104    2356  133.872350.657   152.1 2347.54   163.7 2346.24   180.4 2345.16
   198.4  2345.4   203.9 2344.89   211.2 2343.61   215.7 2343.95   221.5  2345.2
   228.2 2345.73   253.3 2345.13   266.4 2345.52   290.3 2345.34   309.4 2344.29
   318.9 2345.75   323.7 2345.85   371.8 2345.78   394.2 2345.26   404.9 2345.54
     418 2346.64   441.1 2351.49   459.82353.476   519.2 2356.88   537.9 2358.51
#Mann= 6 ,-1 , 0
       0     .05       0   25.23      .1       0  133.87     .05       0
   203.9    .045       0   221.5     .05       0   459.8      .1       0
Bank Sta=203.9,221.5
XS Rating Curve= 0 ,0
Exp/Cntr(USF)=0,0
Exp/Cntr=0.3,0.1

Type RM Length L Ch R = 1 ,24006   ,253.4,253.4,253.4
XS GIS Cut Line= 2
2428616.79883342541632.5548342342429053.55454611541308.421663806
#Sta/Elev= 30
       0 2376.82     8.1 2375.21    18.8 2372.53    58.6 2360.35    83.5 2353.45
    98.5 2350.71  137.662345.475   168.1 2342.91   188.3 2342.78   198.1 2341.81
     213 2342.81   222.5 2342.17   231.1 2342.53   234.12342.338   239.7 2341.14
   242.5 2340.91     2492342.322   257.9 2343.37   262.1  2343.5   282.5 2343.19
   295.7 2343.52   336.9 2342.49   387.3 2342.77   396.9 2343.67   411.2 2346.99
  418.222348.124   491.9  2352.3  530.062355.091   537.3 2355.76   543.9 2355.87
#Mann= 6 ,-1 , 0
       0      .1       0  137.66     .05       0   234.1    .045       0
     249     .05       0  418.22      .1       0  530.06     .12       0
Bank Sta=234.1,249
XS Rating Curve= 0 ,0
Exp/Cntr(USF)=0,0
Exp/Cntr=0.3,0.1

Type RM Length L Ch R = 1 ,23752   ,369.1,369.1,369.1
XS GIS Cut Line= 2
2428822.81567903541816.5965496472429160.68330583541454.006901372
#Sta/Elev= 30
       0 2371.11    11.3 2367.39    22.3 2364.46    54.7 2352.17    74.5 2346.29
      83 2344.55    89.5 2343.72   107.1 2342.61  124.282342.069   159.4 2341.84
   169.9 2341.23   183.4 2341.59   195.1 2341.04   208.1 2341.26   213.6 2340.28
   218.6 2339.93   224.5 2341.18   224.5 2341.19   240.9 2341.25   257.3 2339.84
   268.3 2340.91   277.3  2341.1   295.6 2341.28   309.4 2340.61   329.2 2340.76
   353.5 2344.41   375.72346.107   402.8 2347.21  448.952350.037   495.6 2353.31
#Mann= 6 ,-1 , 0
       0      .1       0  124.28     .05       0   208.1    .045       0
   224.5     .05       0   375.7      .1       0  448.95     .12       0
Bank Sta=208.1,224.5
XS Rating Curve= 0 ,0
Exp/Cntr(USF)=0,0
Exp/Cntr=0.3,0.1

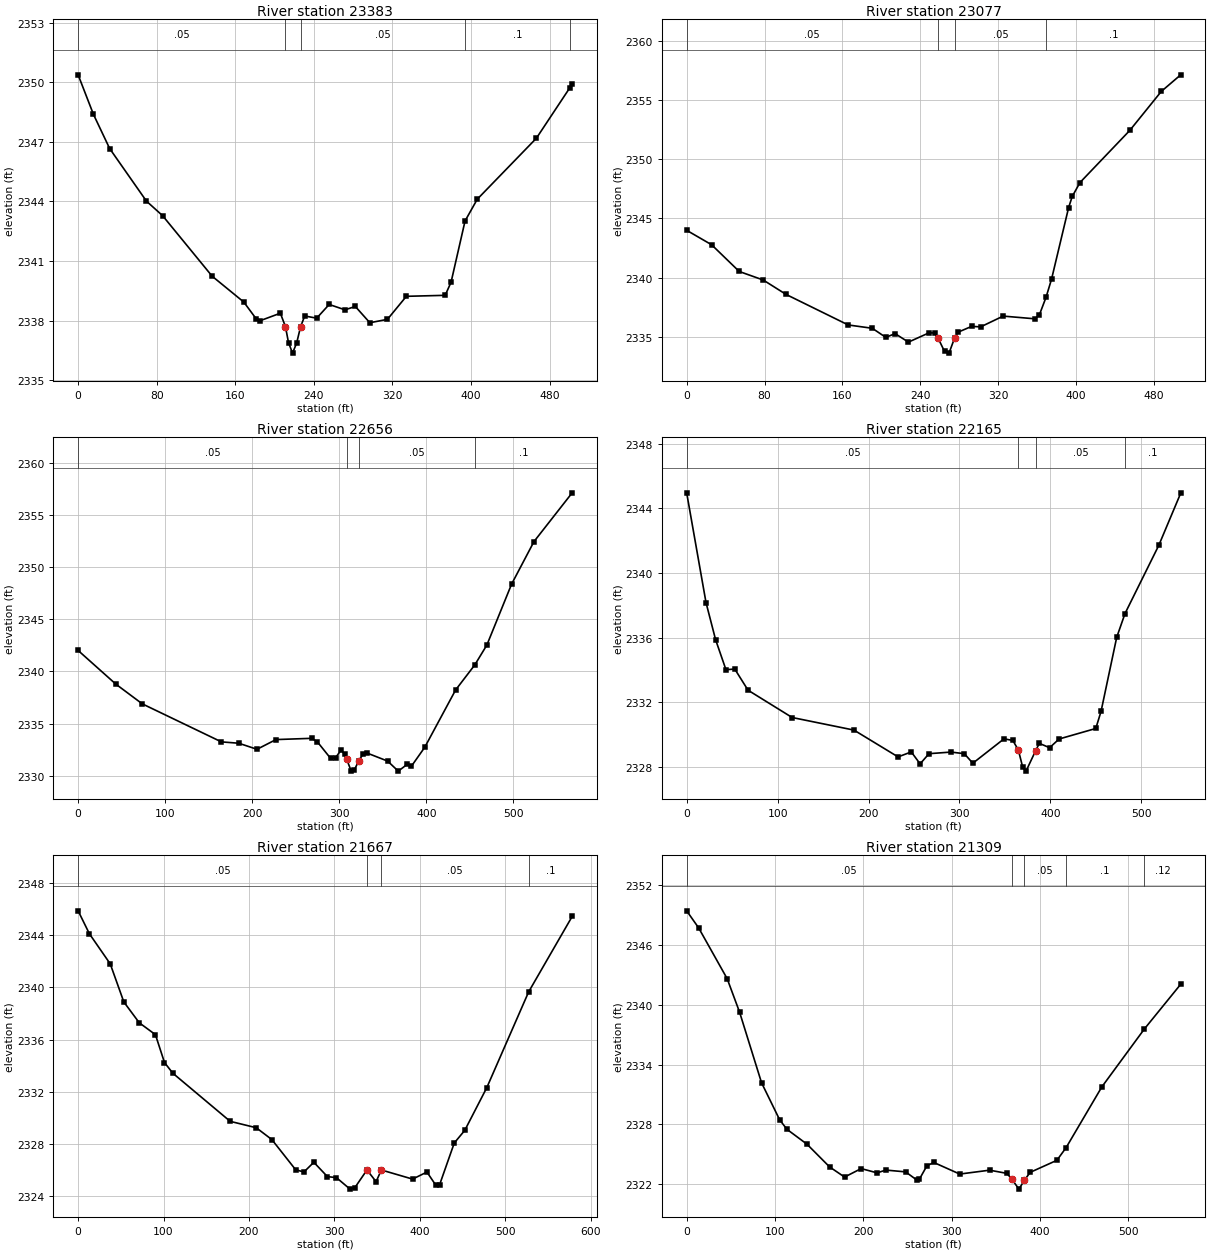
Type RM Length L Ch R = 1 ,23383   ,305.8,305.8,305.8
XS GIS Cut Line= 2
2429149.69574073542047.3354167312429278.79963065541561.135661089
#Sta/Elev= 30
       0 2350.37    15.6 2348.38    32.1 2346.66    69.6 2344.01      86 2343.28
   136.5 2340.23   168.7 2338.93   181.1  2338.1   185.2 2337.99   205.9 2338.37
   211.12337.691   214.2 2336.89   218.3 2336.36   222.5 2336.87   226.5 2337.69
   230.7 2338.23   242.9 2338.12   255.6 2338.81   271.7 2338.54   282.2 2338.71
     297 2337.89   314.9 2338.06   334.2 2339.22   373.7 2339.27   379.7 2339.93
  393.942343.013   406.4 2344.11   466.6 2347.18  500.452349.706     503  2349.9
#Mann= 5 ,-1 , 0
       0     .05       0   211.1    .045       0   226.5     .05       0
  393.94      .1       0  500.45      .1       0
Bank Sta=211.1,226.5
XS Rating Curve= 0 ,0
Exp/Cntr(USF)=0,0
Exp/Cntr=0.3,0.1

Type RM Length L Ch R = 1 ,23077   ,421.9,421.9,421.9
XS GIS Cut Line= 3
2429300.46817223542125.0618066462429430.37669484542012.277517153
 2429600.1859098541723.202246303
#Sta/Elev= 30
       0    2344    25.6 2342.78      54 2340.52    78.6  2339.8   102.1 2338.58
   165.9    2336   190.6 2335.72   204.5 2334.95     214 2335.27   227.7 2334.55
     249 2335.34   254.9 2335.32   257.9 2334.93   264.8 2333.76   269.4 2333.62
   275.3 2334.94   278.7 2335.39   292.6 2335.88   301.9 2335.84     325 2336.75
   357.6 2336.52   362.2 2336.86  369.052338.347   374.7 2339.88   392.2 2345.92
   395.9 2346.86   403.9 2348.04     455 2352.44   487.4 2355.74   507.3 2357.14
#Mann= 4 ,-1 , 0
       0     .05       0   257.9    .045       0   275.3     .05       0
  369.05      .1       0
Bank Sta=257.9,275.3
XS Rating Curve= 0 ,0
Exp/Cntr(USF)=0,0
Exp/Cntr=0.3,0.1

Type RM Length L Ch R = 1 ,22656   ,491,491,491
XS GIS Cut Line= 2
2429421.63797694 542429.153303932429869.38125473542080.298112029
#Sta/Elev= 30
       0 2342.01    43.3 2338.79    73.7  2336.9   164.6 2333.26   184.6 2333.13
   205.5 2332.55   227.3 2333.48   268.3  2333.6   274.8 2333.27     290 2331.69
   295.7 2331.74   301.9 2332.45   306.9 2332.06   308.42331.622   313.8 2330.46
   317.1 2330.53   322.42331.445   327.2 2332.07   332.3 2332.18   355.6 2331.42
   367.8 2330.46   377.9  2331.1     383 2330.94   398.3 2332.75   433.7 2338.23
  455.722340.627   469.6 2342.53     498 2348.36   523.7 2352.43   567.6  2357.1
#Mann= 4 ,-1 , 0
       0     .05       0   308.4    .045       0   322.4     .05       0
  455.72      .1       0
Bank Sta=308.4,322.4
XS Rating Curve= 0 ,0
Exp/Cntr(USF)=0,0
Exp/Cntr=0.3,0.1

Type RM Length L Ch R = 1 ,22165   ,498,498,498
XS GIS Cut Line= 2
 2429644.1361702542786.2491696552430091.87944799542478.597346876
#Sta/Elev= 30
       0 2344.97    21.3 2338.17    31.8 2335.88    43.2 2334.02    52.9 2334.06
    67.5 2332.75     116 2331.06     184 2330.28   232.5 2328.62     247 2328.93
   256.7 2328.19   266.5 2328.82   290.7 2328.92   305.3 2328.82   314.7 2328.23
     349 2329.74   358.7 2329.64   364.8 2329.04   369.4 2328.01   373.2 2327.74
   383.8 2329.01   387.8 2329.46   399.1 2329.19   409.6 2329.73   449.9 2330.38
   455.7 2331.44   472.9 2336.02  482.022337.493   519.2 2341.72   543.3 2344.95
#Mann= 4 ,-1 , 0
       0     .05       0   364.8    .045       0   383.8     .05       0
  482.02      .1       0
Bank Sta=364.8,383.8
XS Rating Curve= 0 ,0
Exp/Cntr(USF)=0,0
Exp/Cntr=0.3,0.1

Type RM Length L Ch R = 1 ,21667   ,357.5,357.5,357.5
XS GIS Cut Line= 2
2429891.35638493 543148.838817932430328.11209762542769.767822006
#Sta/Elev= 30
       0 2345.88    13.2 2344.12    37.6 2341.81    53.5 2338.89    71.6 2337.29
    90.5 2336.38   101.1 2334.24   110.9 2333.42     178 2329.73   208.5 2329.24
   226.8 2328.33   254.7 2326.01   264.4 2325.85   275.9 2326.59   291.8 2325.49
   302.4 2325.41   318.3 2324.53     324 2324.65   338.1    2326   348.8  2325.1
   354.9    2326   391.5  2325.3   408.3 2325.84   418.9 2324.81   423.2 2324.88
   440.3 2328.07   452.6 2329.04   478.4 2332.32  527.392339.667   578.3 2345.45
#Mann= 4 ,-1 , 0
       0     .05       0   338.1    .045       0   354.9     .05       0
  527.39      .1       0
Bank Sta=338.1,354.9
XS Rating Curve= 0 ,0
Exp/Cntr(USF)=0,0
Exp/Cntr=0.3,0.1

Type RM Length L Ch R = 1 ,21309   ,334.6,334.6,334.6
XS GIS Cut Line= 2
2430160.55172986 543365.843228642430550.61029088542964.797102518
#Sta/Elev= 30
       0 2349.41    13.5 2347.71    45.9  2342.6      60 2339.23    84.8 2332.17
   105.3 2328.46   113.5 2327.51   136.3 2326.01   161.8 2323.74   178.8 2322.72
   197.6 2323.57   215.6 2323.14   225.5 2323.42   247.9 2323.24   260.8 2322.41
   263.6 2322.52   272.1 2323.86   279.9 2324.18   309.2 2323.02     343 2323.41
   362.6 2323.09   368.3  2322.5   376.2 2321.51   382.4  2322.4   388.9 2323.19
   419.2  2324.4  429.64 2325.67   470.1 2331.76  518.252337.566   559.4 2342.05
#Mann= 5 ,-1 , 0
       0     .05       0   368.3    .045       0   382.4     .05       0
  429.64      .1       0  518.25     .12       0
Bank Sta=368.3,382.4
XS Rating Curve= 0 ,0
Exp/Cntr(USF)=0,0
Exp/Cntr=0.3,0.1

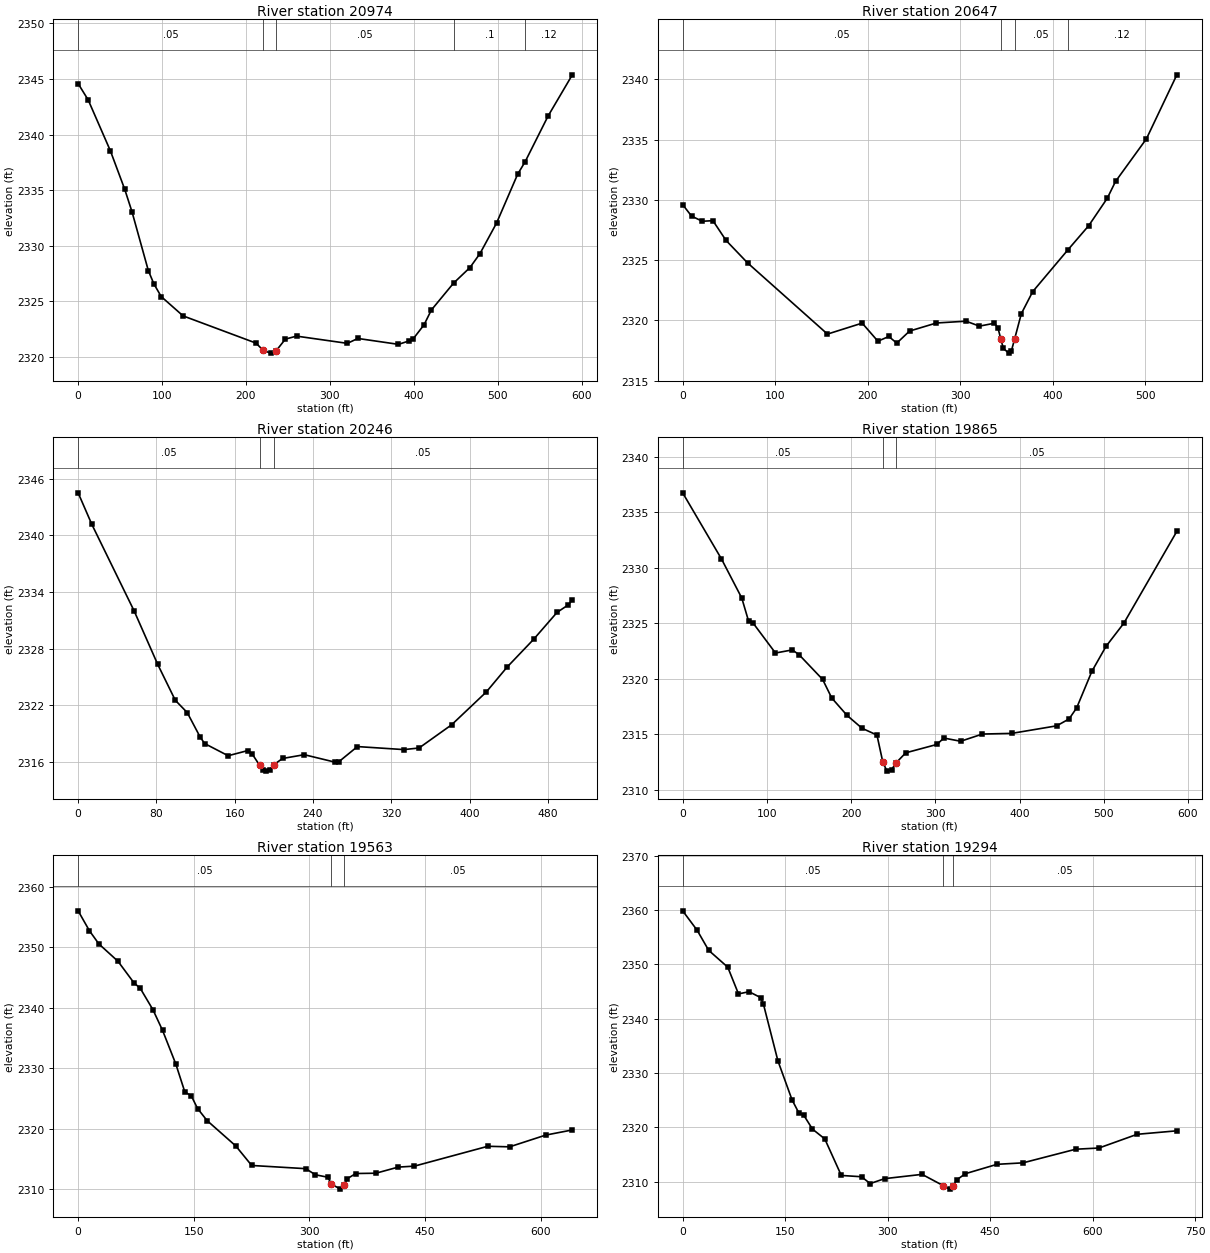
Type RM Length L Ch R = 1 ,20974   ,327.3,327.3,327.3
XS GIS Cut Line= 3
2430256.69292448 543450.99685816 2430679.7141808543269.702034022
2430762.12091904543170.813948129
#Sta/Elev= 30
       0 2344.59      12 2343.12    38.4 2338.55    55.5 2335.09    64.2 2333.06
    83.7 2327.76    90.3 2326.57      99 2325.43   125.1 2323.69   212.1 2321.24
   220.5 2320.59   229.5 2320.34     236 2320.55     247  2321.6   260.3 2321.87
   320.9 2321.22   333.4 2321.66   381.8 2321.13   394.9 2321.45   399.3 2321.62
   412.3 2322.89     421 2324.22  447.452326.637     467 2328.04   478.9 2329.29
   498.7 2332.04   523.8 2336.43  532.872337.575   560.1 2341.67     589 2345.38
#Mann= 5 ,-1 , 0
       0     .05       0   220.5    .045       0     236     .05       0
  447.45      .1       0  532.87     .12       0
Bank Sta=220.5,236
XS Rating Curve= 0 ,0
Exp/Cntr(USF)=0,0
Exp/Cntr=0.3,0.1

Type RM Length L Ch R = 1 ,20647   ,401.4,401.4,401.4
XS GIS Cut Line= 2
2430553.35718216 543731.179768192430852.76833111543288.930272946
#Sta/Elev= 30
       0 2329.61     9.6 2328.66    21.2 2328.23    32.7 2328.28    46.9 2326.64
    70.1 2324.78   156.5 2318.87     194 2319.78     211 2318.28   222.8 2318.67
   231.4 2318.12   245.2 2319.12   274.2 2319.79   306.3 2319.94   320.7 2319.53
     337 2319.77   340.8 2319.37   343.7  2318.5   346.6 2317.68   352.4 2317.29
   355.2 2317.45   358.82318.476     366 2320.56   378.3 2322.39  416.242325.849
   438.8 2327.86   458.9 2330.14   467.8 2331.53   501.2 2335.07   534.1 2340.38
#Mann= 4 ,-1 , 0
       0     .05       0   343.7    .045       0   358.8     .05       0
  416.24     .12       0
Bank Sta=343.7,358.8
XS Rating Curve= 0 ,0
Exp/Cntr(USF)=0,0
Exp/Cntr=0.3,0.1

Type RM Length L Ch R = 1 ,20246   ,380.6,380.6,380.6
XS GIS Cut Line= 2
2430654.99215933543887.7525708552431110.97611094543670.748160144
#Sta/Elev= 30
       0 2344.51      14 2341.17    57.3 2331.99    81.3 2326.35    99.3 2322.54
   111.5 2321.24   124.8 2318.63   129.3 2317.96   153.3 2316.67   173.5 2317.22
   177.9 2316.85   185.4 2315.67   189.3 2315.17   192.3 2315.04   195.6 2315.17
   200.1 2315.73   208.9 2316.38   231.1 2316.78   262.1    2316   266.5 2316.04
   285.4 2317.64   332.9 2317.32   348.4 2317.49   381.7 2319.95   417.1 2323.42
   438.4 2326.06   465.4 2328.99   489.4 2331.85   500.8 2332.64     505 2333.19
#Mann= 3 ,-1 , 0
       0     .05       0   185.4    .045       0   200.1     .05       0
Bank Sta=185.4,200.1
XS Rating Curve= 0 ,0
Exp/Cntr(USF)=0,0
Exp/Cntr=0.3,0.1

Type RM Length L Ch R = 1 ,19865   ,301.8,301.8,301.8
XS GIS Cut Line= 3
2430789.58983179544189.9106110842430940.66885191 544181.66993726
2431262.05513106543887.752570855
#Sta/Elev= 30
       0 2336.76    46.1  2330.8    70.2 2327.28    78.2 2325.22    83.5 2325.04
   110.2 2322.33   130.2 2322.61   138.2 2322.18   166.2 2319.95     177 2318.28
   195.2 2316.71     213 2315.55   230.7 2314.94   237.72312.489   242.6 2311.69
     248 2311.82   253.6 2312.45   264.9 2313.34   301.7 2314.09   310.2 2314.67
   330.1 2314.38   355.9 2315.03   390.7 2315.09   444.1 2315.77   458.8 2316.39
   467.8 2317.38   485.9 2320.68   502.7 2322.93   523.9 2325.02   586.8 2333.29
#Mann= 3 ,-1 , 0
       0     .05       0   237.7    .045       0   253.6     .05       0
Bank Sta=237.7,253.6
XS Rating Curve= 0 ,0
Exp/Cntr(USF)=0,0
Exp/Cntr=0.3,0.1

Type RM Length L Ch R = 1 ,19563   ,269.7,269.7,269.7
XS GIS Cut Line= 2
2430833.54009219544448.118390916 2431454.3375203544288.798696977
#Sta/Elev= 30
       0 2356.02    14.6 2352.74    26.9 2350.55    51.7 2347.68    72.4 2344.12
    80.6 2343.21    97.1 2339.66   109.5 2336.26   126.7  2330.7   138.4 2326.08
   146.7 2325.46   154.9 2323.35   167.3 2321.35   204.5 2317.16   225.1 2313.94
   295.3 2313.41   307.7  2312.4   323.8    2312   328.4 2310.86   340.2 2310.03
   344.9 2310.67     349 2311.74     360 2312.61   386.2 2312.66   415.1 2313.67
   436.1 2313.83   531.3 2317.11   559.6 2317.02   606.4 2318.96   640.9 2319.81
#Mann= 3 ,-1 , 0
       0     .05       0   328.4    .045       0   344.9     .05       0
Bank Sta=328.4,344.9
XS Rating Curve= 0 ,0
Exp/Cntr(USF)=0,0
Exp/Cntr=0.3,0.1

Type RM Length L Ch R = 1 ,19294   ,171.1,171.1,171.1
XS GIS Cut Line= 3
 2430927.5325529544707.4795199142431448.15146595544532.090235516
2431539.52948277544384.059505708
#Sta/Elev= 30
       0 2359.86    21.2 2356.28    38.1 2352.58      66 2349.48    81.7 2344.56
    97.2 2344.96   114.1 2343.88   118.3 2342.63   139.4 2332.23   160.1 2325.04
   170.1 2322.62   177.4 2322.18     190 2319.65     208 2317.85   232.2 2311.12
   261.8 2310.88   274.4 2309.62   295.5 2310.53   350.4 2311.32   381.7 2309.22
   391.1  2308.6   395.6 2309.16     401 2310.29   413.7 2311.44   460.1 2313.17
   498.1 2313.44   575.2 2315.95   609.2 2316.17   665.2  2318.7   723.3 2319.34
#Mann= 3 ,-1 , 0
       0     .05       0   381.7    .045       0   395.6     .05       0
Bank Sta=381.7,395.6
XS Rating Curve= 0 ,0
Exp/Cntr(USF)=0,0
Exp/Cntr=0.3,0.1

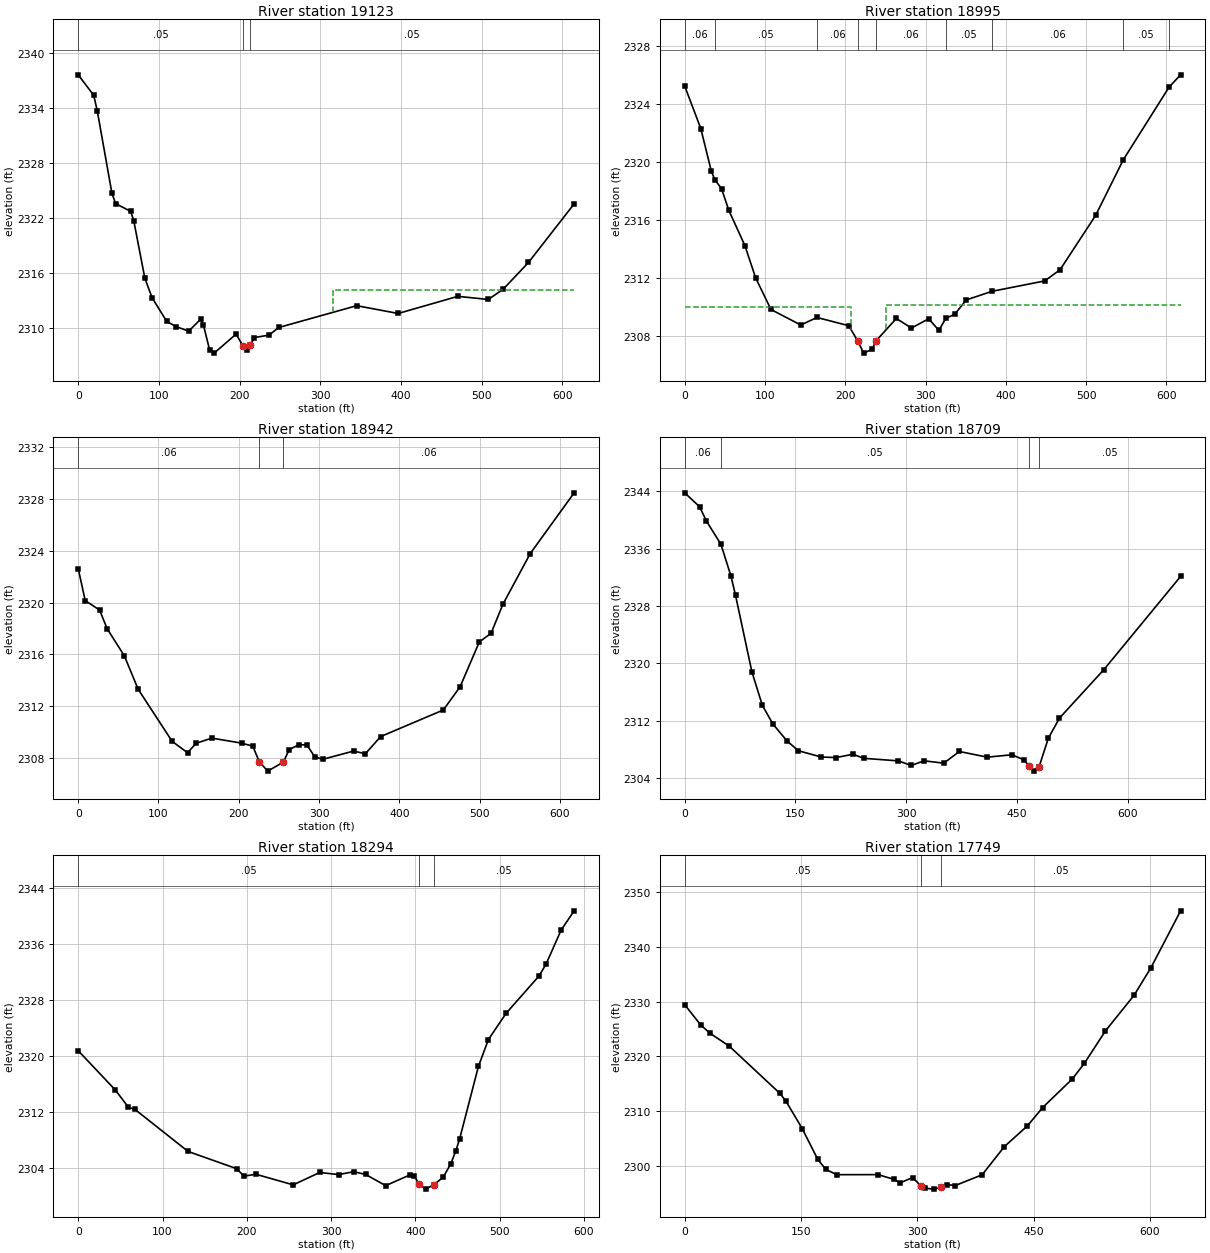
Type RM Length L Ch R = 1 ,19123   ,127.9,127.9,127.9
XS GIS Cut Line= 2
 2431122.6426847544851.0219666642431665.53840855544563.205389447
#Sta/Elev= 30
       0 2337.64    19.2 2335.41    23.7 2333.67    41.8 2324.69    46.4 2323.57
    65.1 2322.73      69 2321.63    82.6 2315.41    91.6 2313.29   109.7 2310.71
   121.3 2310.15   136.9 2309.65   151.6 2310.94     155 2310.37   162.7 2307.64
   168.4 2307.25   195.7 2309.33   204.1 2308.04   209.3 2307.55     213  2308.1
   218.4 2308.95   236.5 2309.22   248.5 2310.05   345.1 2312.43   396.4 2311.58
   470.4 2313.45   508.1 2313.11   526.6 2314.23   557.9 2317.15   614.5 2323.55
#Mann= 3 ,-1 , 0
       0     .05       0   204.1    .045       0     213     .05       0
#XS Ineff= 2 , 0
                          315.15         2314.14
Permanent Ineff=
       F       F
Bank Sta=204.1,213
XS Rating Curve= 0 ,0
Exp/Cntr(USF)=0,0
Exp/Cntr=0.5,0.3

Type RM Length L Ch R = 1 ,18995   ,52.8,52.8,52.8
XS GIS Cut Line= 3
2431177.20506901544930.1374239092431357.26093722544851.021966664
2431702.36801796544609.583416107
#Sta/Elev= 30
       0 2325.24    20.1  2322.3    33.2 2319.36    37.6 2318.77    45.9 2318.16
      55 2316.66      75 2314.23    88.4    2312   107.5 2309.82   144.6 2308.75
  164.84 2309.27   204.4  2308.7   215.9 2307.62   222.9 2306.81   233.7 2307.08
   237.9 2307.63   263.7  2309.2   282.5 2308.54   303.9 2309.18   316.7 2308.38
  325.222309.212   336.2 2309.48   350.8 2310.48  383.012311.076   448.4 2311.79
   467.6 2312.56   511.9 2316.31  546.542320.163  603.582325.174   617.8 2326.01
#Mann= 9 ,-1 , 0
       0     .06       0    37.6     .05       0  164.84     .06       0
   215.9    .045       0   237.9     .06       0  325.22     .05       0
  383.01     .06       0  546.54     .05       0  603.58     .06       0
#XS Ineff= 2 , 0
       0  207.32    2310   251.4       0  2310.1
Permanent Ineff=
       F       F
Bank Sta=215.9,237.9
XS Rating Curve= 0 ,0
Exp/Cntr(USF)=0,0
Exp/Cntr=0.5,0.3

Type RM Length L Ch R = 1 ,18942   ,232.8,232.8,232.8
XS GIS Cut Line= 3
2431207.21438038544971.0592121392431387.27024859544891.943754894
2431732.37732933544650.505204337
#Sta/Elev= 30
       0 2322.62     8.7 2320.15    26.6 2319.42      36 2317.98    57.4 2315.89
    74.7  2313.3     117 2309.28   136.2  2308.4   146.9 2309.13   166.4 2309.53
   203.6 2309.14   217.5 2308.91   225.6  2307.7   236.1 2306.98   255.6 2307.68
   262.9 2308.65   275.1 2309.02   284.9    2309   294.5  2308.1   304.4 2307.89
   343.1 2308.53   357.7 2308.32   376.8 2309.65   454.8  2311.7   475.7 2313.49
   499.7 2316.96   514.3 2317.62     529 2319.86   563.1 2323.78   617.8 2328.47
#Mann= 3 ,-1 , 0
       0     .06       0   225.6    .045       0   255.6     .06       0
Bank Sta=225.6,255.6
XS Rating Curve= 0 ,0
Exp/Cntr(USF)=0,0
Exp/Cntr=0.5,0.3

Type RM Length L Ch R = 1 ,18709   ,414.9,414.9,414.9
XS GIS Cut Line= 2
2431234.58621831545189.779035115 2431803.1927122 544832.68316939
#Sta/Elev= 30
       0 2343.81    20.1 2341.88    29.5 2339.86   49.052336.634    62.6 2332.21
    68.8 2329.53    90.9 2318.88   105.1 2314.17   119.3 2311.57   138.4 2309.21
   153.8 2307.83   184.8 2306.95   205.1 2306.87   227.9 2307.34   242.1 2306.77
   289.2 2306.41   306.7 2305.77   324.1 2306.42   350.7 2306.09   371.9 2307.72
   409.5 2306.93     443 2307.26   459.3 2306.56   466.82305.632   473.5 2304.98
   479.9 2305.62   492.3 2309.56   507.3 2312.37   567.5 2319.14   671.4 2332.15
#Mann= 4 ,-1 , 0
       0     .06       0   49.05     .05       0   466.8    .045       0
   479.9     .05       0
Bank Sta=466.8,479.9
XS Rating Curve= 0 ,0
Exp/Cntr(USF)=0,0
Exp/Cntr=0.3,0.1

Type RM Length L Ch R = 1 ,18294   ,544.8,544.8,544.8
XS GIS Cut Line= 2
2431424.12171627545502.9246404442431948.77794976545236.476186787
#Sta/Elev= 30
       0 2320.75    44.2 2315.11    59.6 2312.66    67.3 2312.36   130.3 2306.35
   187.8 2303.89   196.8 2302.81   210.7 2303.09   255.1 2301.57   286.5 2303.34
   308.9 2303.04   326.9 2303.45     341 2303.06   364.8 2301.46   394.1 2303.02
   398.6 2302.87   404.22301.721   412.1 2300.96   421.8 2301.57   433.2 2302.69
   442.1  2304.6     448 2306.43   452.5 2308.12   474.8  2318.5   486.7 2322.35
   507.6 2326.09   546.7 2331.43   555.2 2333.16     573 2338.01   588.4 2340.75
#Mann= 3 ,-1 , 0
       0     .05       0   404.2    .045       0   421.8     .05       0
Bank Sta=404.2,421.8
XS Rating Curve= 0 ,0
Exp/Cntr(USF)=0,0
Exp/Cntr=0.3,0.1

Type RM Length L Ch R = 1 ,17749   ,387.9,387.9,387.9
XS GIS Cut Line= 3
2431575.20073639545865.5142887192432020.19712291545777.613767925
2432190.50438195545703.447703505
#Sta/Elev= 30
       0 2329.44    20.7 2325.72      33 2324.18    57.4 2321.87   122.7 2313.24
   130.5 2311.82   151.5 2306.81   171.6 2301.17   182.1 2299.33   196.1 2298.38
   249.1 2298.39   269.4 2297.55   277.6 2296.87   293.9 2297.86   304.7  2296.3
   310.2 2295.89   321.7 2295.74   330.6  2296.1   338.7 2296.56   348.9  2296.4
   383.6 2298.37   412.1  2303.5   441.9  2307.3   461.6 2310.65     500  2315.9
   515.2  2318.7   542.5 2324.65   579.4 2331.15   601.2  2336.2   639.4 2346.58
#Mann= 3 ,-1 , 0
       0     .05       0   304.7    .045       0   330.6     .05       0
Bank Sta=304.7,330.6
XS Rating Curve= 0 ,0
Exp/Cntr(USF)=0,0
Exp/Cntr=0.3,0.1

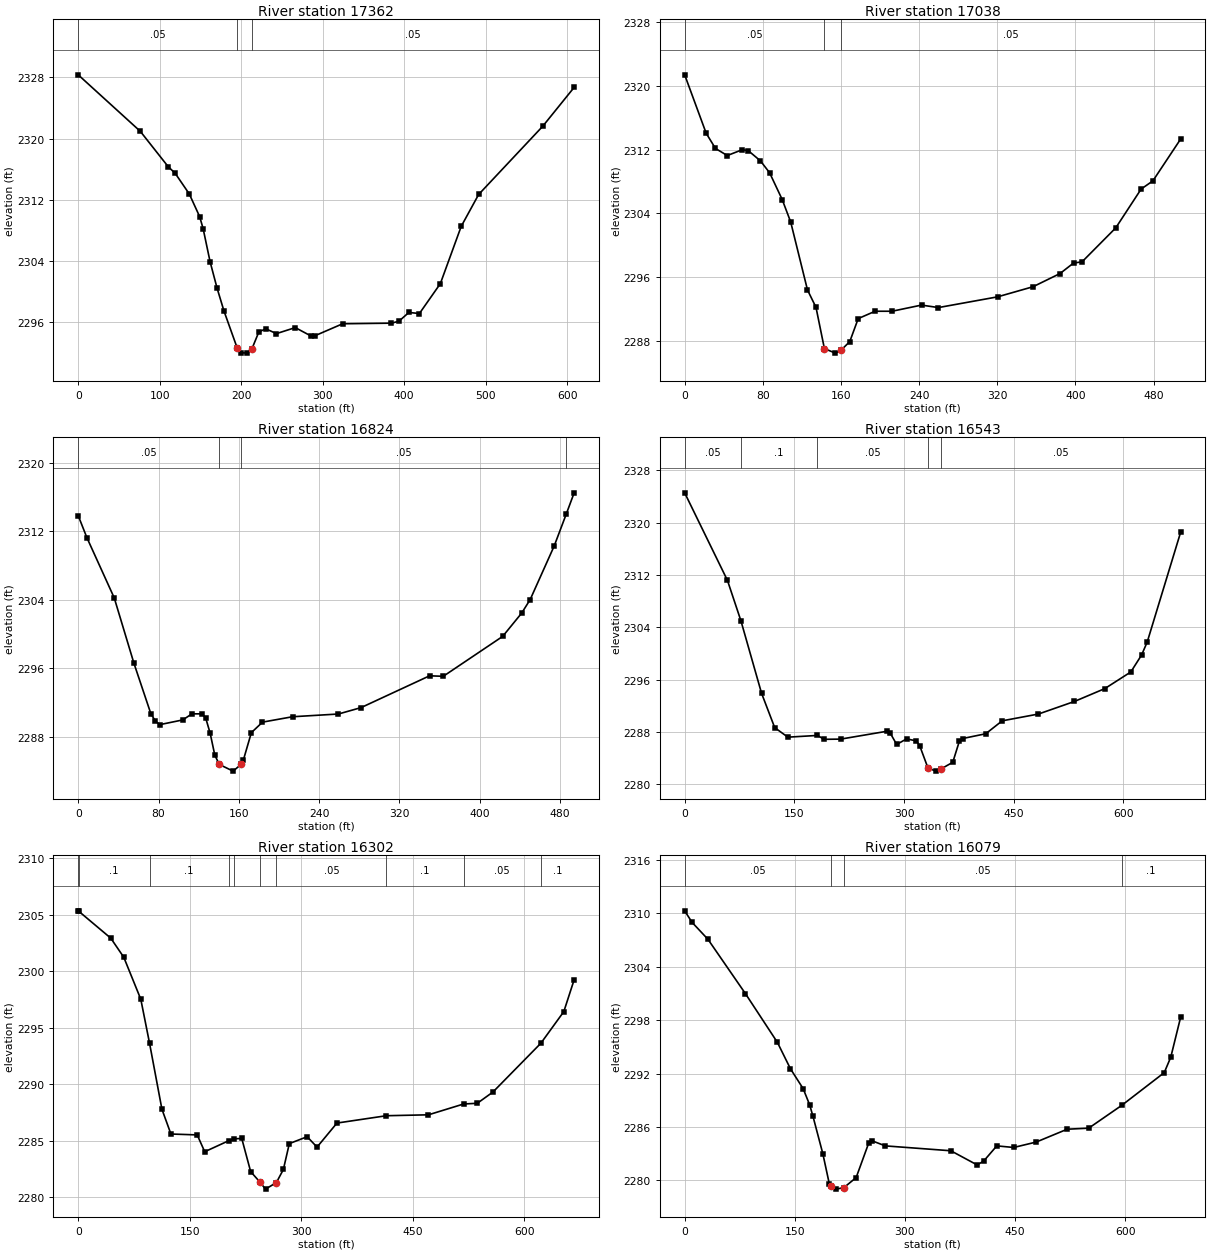
Type RM Length L Ch R = 1 ,17362   ,323.6,323.6,323.6
XS GIS Cut Line= 2
2431660.35436591546244.5852846432432228.96085979546027.580873933
#Sta/Elev= 30
       0 2328.33    76.2 2320.94   110.4 2316.32     119 2315.45   136.3 2312.75
     149 2309.79   153.3 2308.21   161.8  2303.9   170.4 2300.43   178.9 2297.43
   195.2 2292.57   200.3 2291.98   207.6 2291.93   213.2  2292.5   221.7 2294.71
   230.3 2295.11   243.2 2294.48   266.4 2295.27     286 2294.15   290.2 2294.19
   324.5 2295.77   384.4 2295.85   393.5  2296.1   405.8 2297.25   418.7 2297.11
   444.4 2301.02     470 2308.51   491.4 2312.68   570.1 2321.61   608.6 2326.69
#Mann= 3 ,-1 , 0
       0     .05       0   195.2    .045       0   213.2     .05       0
Bank Sta=195.2,213.2
XS Rating Curve= 0 ,0
Exp/Cntr(USF)=0,0
Exp/Cntr=0.3,0.1

Type RM Length L Ch R = 1 ,17038   ,214.2,214.2,214.2
XS GIS Cut Line= 2
2431847.14297259546516.5275208492432316.86138059546324.245131612
#Sta/Elev= 30
       0 2321.35      22 2314.04    31.5 2312.14    43.6 2311.25    59.1 2311.99
    65.3 2311.84    77.5 2310.59    86.9  2309.1    99.8 2305.75   108.5 2302.94
   125.7 2294.43   134.4 2292.26     143  2287.1   154.2 2286.53   160.4 2286.94
     169 2287.98   177.6 2290.85   194.9 2291.77   212.2 2291.77   242.4 2292.54
   259.7 2292.23   320.2 2293.57   356.6 2294.84   384.2 2296.49     398  2297.8
   406.7 2297.95   441.2  2302.2   467.2 2307.06   479.2 2308.08   507.6 2313.31
#Mann= 3 ,-1 , 0
       0     .05       0     143    .045       0   160.4     .05       0
Bank Sta=143,160.4
XS Rating Curve= 0 ,0
Exp/Cntr(USF)=0,0
Exp/Cntr=0.3,0.1

Type RM Length L Ch R = 1 ,16824   ,280.6,280.6,280.6
XS GIS Cut Line= 2
2431968.00618869546711.5568013612432402.01501011546475.324151727
#Sta/Elev= 30
       0 2313.83     8.6 2311.27    35.9 2304.21    55.5 2296.57    72.3 2290.69
    76.9 2289.79    81.4 2289.39   104.2 2289.94   113.3 2290.65   123.3 2290.65
   126.9 2290.21   131.5 2288.36   136.1 2285.81   140.6 2284.73   154.3 2283.95
   162.32284.738   164.6 2285.27   172.5 2288.45   183.6 2289.68   213.5 2290.31
   259.2 2290.63   281.8 2291.38   350.1  2295.1   363.7 2295.04   422.9 2299.71
   441.8 2302.43   450.3 2304.02   474.2 2310.28  486.122313.982   494.1  2316.5
#Mann= 4 ,-1 , 0
       0     .05       0   140.6    .045       0   162.3     .05       0
  486.12     .12       0
Bank Sta=140.6,162.3
XS Rating Curve= 0 ,0
Exp/Cntr(USF)=0,0
Exp/Cntr=0.3,0.1

Type RM Length L Ch R = 1 ,16543   ,240.6,240.6,240.6
XS GIS Cut Line= 2
2431910.32147191547049.424428162 2432511.8906611546736.278822834
#Sta/Elev= 30
       0 2324.58    58.5 2311.17   76.992304.964   105.1 2293.91   123.1 2288.64
   141.1 2287.18  181.592287.442   190.7 2286.85   213.3 2286.88   276.4 2288.08
   280.9 2287.84   289.9 2286.06   303.5 2286.92     317  2286.6   321.5 2285.84
   332.8 2282.42     344 2281.98   350.1 2282.29   366.6 2283.33   375.6 2286.55
   380.1 2286.97   411.7  2287.7   434.2 2289.68   483.8 2290.72   532.9 2292.64
   574.5 2294.61   610.1 2297.16   624.9 2299.77   632.6 2301.77   678.2 2318.54
#Mann= 5 ,-1 , 0
       0     .05       0   76.99      .1       0  181.59     .05       0
   332.8    .045       0   350.1     .05       0
Bank Sta=332.8,350.1
XS Rating Curve= 0 ,0
Exp/Cntr(USF)=0,0
Exp/Cntr=0.3,0.1

Type RM Length L Ch R = 1 ,16302   ,223.6,223.6,223.6
XS GIS Cut Line= 4
2432032.91258122547255.1338769212432204.36814737 547122.31618484
2432296.13309826 547122.316184842432617.31042638546962.934954342
#Sta/Elev= 30
       0 2305.36     .642305.327    43.8 2302.94    61.3 2301.25    84.2 2297.53
   96.012293.623   112.6  2287.8   124.7  2285.6   160.1 2285.52   170.2 2284.03
  202.232284.999  209.082285.167     220 2285.21     232 2282.27     244 2281.38
     252 2280.72   266.6  2281.3     276 2282.46     284 2284.75     308 2285.36
   321.3 2284.44   348.1 2286.57  414.572287.219   471.2  2287.3  518.532288.258
   536.9 2288.32     558 2289.32  622.492293.642   653.3 2296.44   667.2 2299.26
#Mann= 10 ,-1 , 0
       0     .05       0     .64      .1       0   96.01      .1       0
  202.23      .1       0  209.08     .05       0     244    .045       0
   266.6     .05       0  414.57      .1       0  518.53     .05       0
  622.49      .1       0
Bank Sta=244,266.6
XS Rating Curve= 0 ,0
Exp/Cntr(USF)=0,0
Exp/Cntr=0.3,0.1

Type RM Length L Ch R = 1 ,16079   ,406.2,406.2,406.2
XS GIS Cut Line= 2
 2432075.1349484547436.7360979112432679.45102886547134.578057682
#Sta/Elev= 30
       0  2310.3      10 2309.01    31.7  2307.1    82.8 2300.99   126.3 2295.52
   144.1 2292.55   161.4 2290.32   170.3 2288.49   174.8  2287.2   188.2 2283.01
   197.2 2279.56   199.1 2279.35   206.1 2279.03   216.9  2279.2   233.6 2280.33
   250.8 2284.23   255.3 2284.46   273.2 2283.89   362.6 2283.34   398.4 2281.75
   407.3 2282.18   425.2 2283.89   448.2 2283.71   478.9 2284.32     521 2285.76
   550.4 2285.88  595.422288.443   653.3 2292.12   662.2 2293.86   675.6 2298.34
#Mann= 4 ,-1 , 0
       0     .05       0   199.1    .045       0   216.9     .05       0
  595.42      .1       0
Bank Sta=199.1,216.9
XS Rating Curve= 0 ,0
Exp/Cntr(USF)=0,0
Exp/Cntr=0.3,0.1