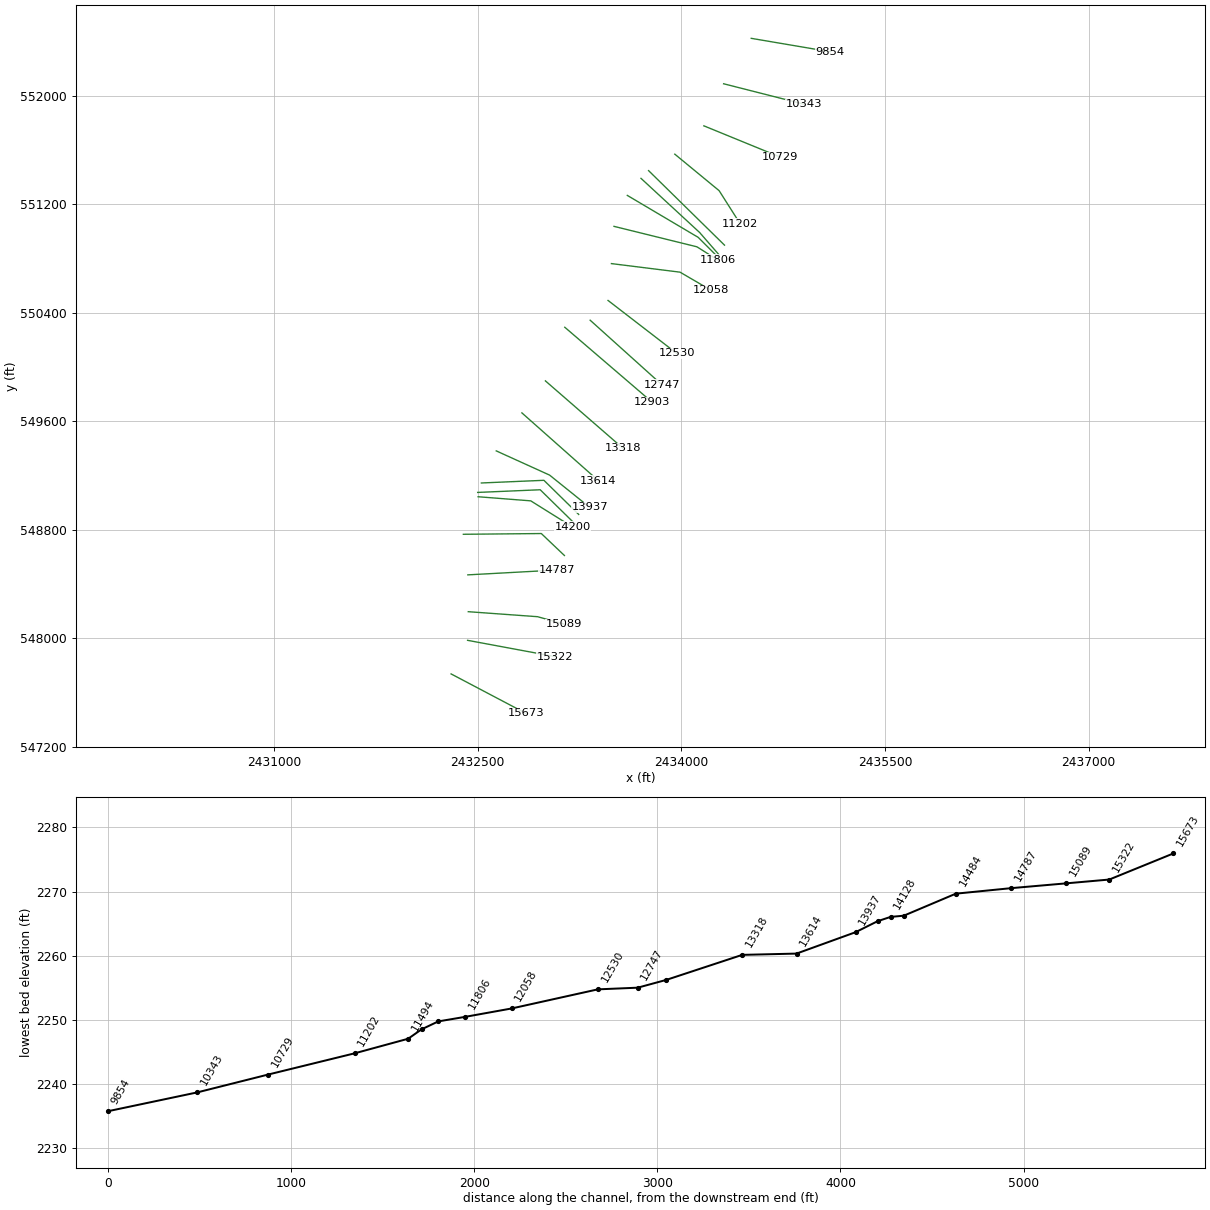
HEC-RAS study WHITHORNCK.prj: WHITHORNCK

--- WHITHORNCK.g01 (geometry) --- (continued)

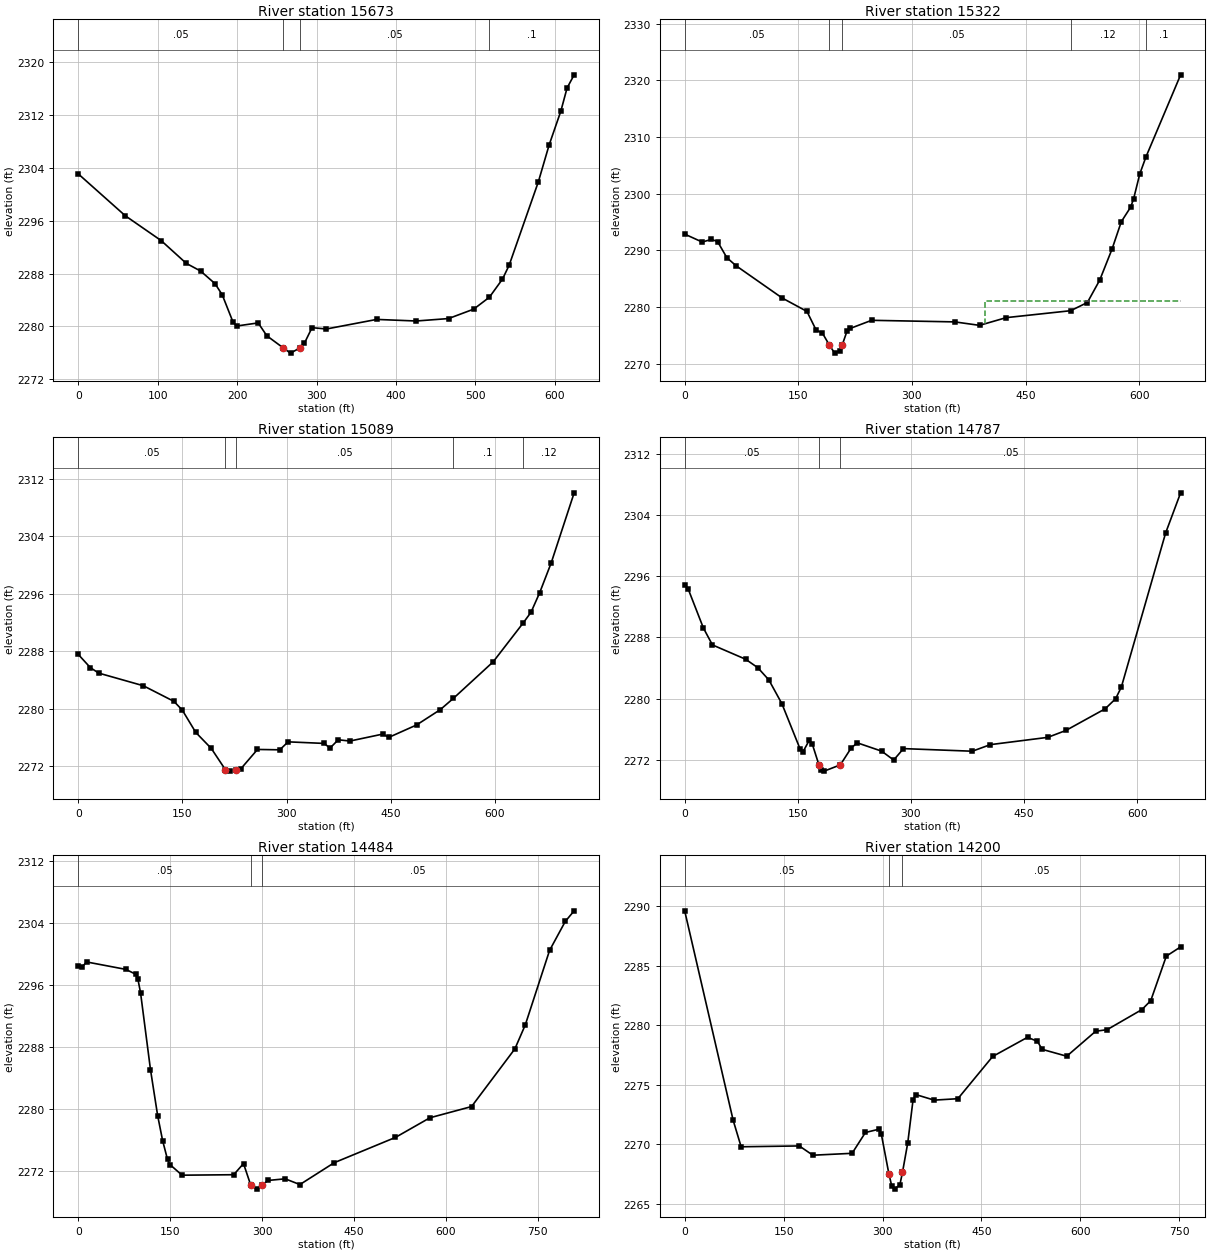
Type RM Length L Ch R = 1 ,15673   ,350.5,350.5,350.5
XS GIS Cut Line= 2
2432303.12692421547736.1472468652432855.25207045547444.976771735
#Sta/Elev= 30
       0 2303.12    59.2 2296.77   104.4    2293     136 2289.55   154.1 2288.38
   172.3 2286.46   181.3 2284.77   194.8 2280.66   199.4 2280.05   226.5 2280.52
   237.4 2278.57   258.2 2276.72   258.2 2276.71   267.2 2275.94   278.9 2276.72
   284.8 2277.47   294.3  2279.8   312.4  2279.6   375.7 2281.05   425.4 2280.81
   466.1 2281.18   497.8 2282.61  517.522284.416     534 2287.16   542.4 2289.27
   579.2 2301.93   592.6 2307.46   607.5 2312.65   615.3 2316.14   624.2 2318.13
#Mann= 4 ,-1 , 0
       0     .05       0   258.2    .045       0   278.9     .05       0
  517.52      .1       0
Bank Sta=258.2,278.9
XS Rating Curve= 0 ,0
Exp/Cntr(USF)=0,0
Exp/Cntr=0.3,0.1

Type RM Length L Ch R = 1 ,15322   ,233.6,233.6,233.6
XS GIS Cut Line= 2
2432424.77071169547983.8429095322433068.44218636547864.090077035
#Sta/Elev= 30
       0 2292.87    23.1 2291.47    35.3 2291.93    43.4 2291.56    55.6 2288.72
    67.8 2287.29   128.9 2281.58   161.4 2279.23   173.6 2275.92   181.7 2275.43
   191.1 2273.27     198 2271.87   204.9 2272.31     208 2273.32   214.3 2275.75
   218.4 2276.22   246.8 2277.66   356.7 2277.38   389.2 2276.77   424.4 2278.13
  509.532279.354   531.6  2280.8   547.9 2284.75   564.2 2290.24   576.4 2295.06
   588.6  2297.6   592.5 2299.02   600.8 2303.49  608.882306.469   654.7 2320.97
#Mann= 5 ,-1 , 0
       0     .05       0   191.1    .045       0     208     .05       0
  509.53     .12       0  608.88      .1       0
#XS Ineff= 2 , 0
                          396.17         2281.02
Permanent Ineff=
       F       F
Bank Sta=191.1,208
XS Rating Curve= 0 ,0
Exp/Cntr(USF)=0,0
Exp/Cntr=0.3,0.1

Type RM Length L Ch R = 1 ,15089   ,301.5,301.5,301.5
XS GIS Cut Line= 3
2432430.01738266548195.0887771962432940.17567593548158.259167789
2433135.23619982548103.696783482
#Sta/Elev= 30
       0 2287.55    17.5  2285.7    29.5 2284.94    93.7 2283.18   137.8    2281
   149.8 2279.79   169.2 2276.68   191.6 2274.44   211.82271.495     218 2271.28
   226.9 2271.47     234 2271.59   258.1  2274.3   290.2 2274.25   302.2 2275.36
   354.3 2275.14   362.4 2274.48   374.4 2275.65   391.1 2275.47   438.4 2276.44
   447.3 2275.99   487.1 2277.71   521.3 2279.85  540.222281.427   597.4 2286.51
  640.17 2291.87   651.9 2293.42   664.4 2296.15     681 2300.31     714 2310.06
#Mann= 5 ,-1 , 0
       0     .05       0   211.8    .045       0   226.9     .05       0
  540.22      .1       0  640.17     .12       0
Bank Sta=211.8,226.9
XS Rating Curve= 0 ,0
Exp/Cntr(USF)=0,0
Exp/Cntr=0.3,0.1

Type RM Length L Ch R = 1 ,14787   ,302.7,302.7,302.7
XS GIS Cut Line= 2
2432426.73703158548466.8203259652433083.24404626548502.529912538
#Sta/Elev= 30
       0 2294.87     4.7  2294.3    24.8 2289.22    36.8 2287.01    80.8 2285.14
    96.9 2284.04   111.6 2282.44   128.9 2279.33   152.9 2273.45   156.9 2273.06
     165 2274.53     169 2274.12   177.9 2271.37     181 2270.65     185 2270.53
   206.42271.352     221 2273.59     229 2274.22   261.1 2273.14   277.1 2271.98
   290.1 2273.47   381.3 2273.13   405.3 2273.99   481.4 2274.94   505.4 2275.84
   557.5 2278.67   571.3 2279.98   578.9  2281.5   637.6 2301.62   657.5 2306.87
#Mann= 3 ,-1 , 0
       0     .05       0   177.9    .045       0   206.4     .05       0
Bank Sta=177.9,206.4
XS Rating Curve= 0 ,0
Exp/Cntr(USF)=0,0
Exp/Cntr=0.3,0.1

Type RM Length L Ch R = 1 ,14484   ,284.2,284.2,284.2
XS GIS Cut Line= 3
2432393.77433628 548766.231474922432967.87461272548771.725257469
2433138.18187175548609.658672255
#Sta/Elev= 30
       0 2298.47     5.7 2298.29    13.7    2299    77.7 2298.04    93.7 2297.42
    97.3 2296.81   101.7 2295.03   117.9 2285.11   129.6 2279.17   137.7 2275.94
   145.7  2273.5   149.7 2272.84   169.4 2271.47   253.7 2271.53   269.7 2272.97
   281.7 2270.14   292.2 2269.67   300.1  2270.2   309.7 2270.79   337.7    2271
   361.7 2270.26   417.7 2273.08   517.7 2276.35   573.8 2278.88   641.8 2280.33
   712.5 2287.78   729.5 2290.88   769.1 2300.49   794.8 2304.24   809.2  2305.6
#Mann= 3 ,-1 , 0
       0     .05       0   281.7    .045       0   300.1     .05       0
Bank Sta=281.7,300.1
XS Rating Curve= 0 ,0
Exp/Cntr(USF)=0,0
Exp/Cntr=0.3,0.1

Type RM Length L Ch R = 1 ,14200   ,72.4,72.4,72.4
XS GIS Cut Line= 3
2432502.14226831549043.187692633 2432890.1414456549012.875256907
2433197.81266822548820.391290047
#Sta/Elev= 30
       0 2289.63    73.5 2272.03    85.6  2269.8   173.8 2269.87   194.4 2269.09
   253.9 2269.25   274.1    2271   294.2 2271.27   298.2 2270.87   309.8 2267.49
   314.2 2266.47   318.2 2266.24   326.3  2266.6   330.3 2267.65   338.3 2270.13
   346.3 2273.73   350.3 2274.19   378.4 2273.72   414.3 2273.84   467.1 2277.39
   519.9    2279     535 2278.66     542 2277.99   579.4 2277.41   623.3 2279.51
   640.6 2279.64   693.4 2281.33   706.8 2282.08   730.4 2285.82   752.1  2286.6
#Mann= 3 ,-1 , 0
       0     .05       0   309.8    .045       0   330.3     .05       0
Bank Sta=309.8,330.3
XS Rating Curve= 0 ,0
Exp/Cntr(USF)=0,0
Exp/Cntr=0.5,0.3

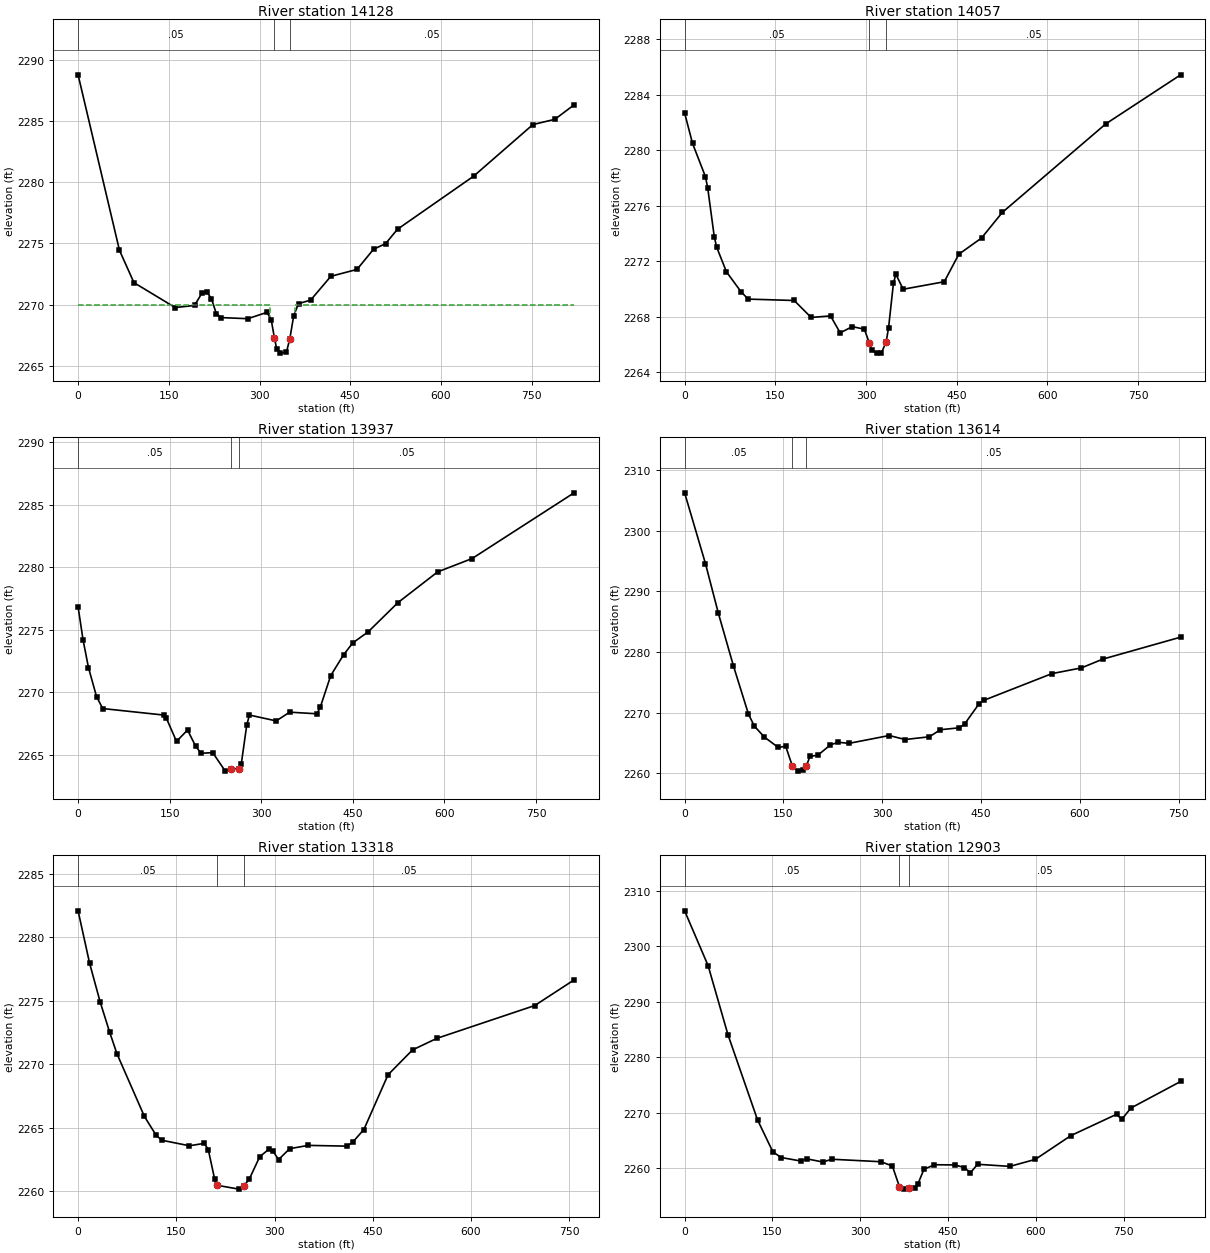
Type RM Length L Ch R = 1 ,14128   ,70.8,70.8,70.8
XS GIS Cut Line= 3
2432499.11102474549075.0157501452432959.86004777549094.718833367
2433216.00012965548843.125616841
#Sta/Elev= 30
       0 2288.76    68.4 2274.44    92.4  2271.8   160.5 2269.77   192.5 2269.94
   204.5 2270.92   212.5 2271.06   220.5  2270.5   228.5 2269.28   236.5 2268.95
   280.6 2268.86   312.6 2269.38   319.5 2268.73   324.6 2267.31   328.6 2266.35
   334.4 2266.05   344.6 2266.14   350.2 2267.24   356.6 2269.12   364.6 2270.09
   384.6 2270.38     418 2272.32   461.2 2272.88   488.6 2274.53   508.4 2274.98
   528.2 2276.16   654.1 2280.49   752.1  2284.7   788.4 2285.13   820.2 2286.31
#Mann= 3 ,-1 , 0
       0     .05       0   324.6    .045       0   350.2     .05       0
#XS Ineff= 2 , 0
           316.6    2270   358.3            2270
Permanent Ineff=
       F       F
Bank Sta=324.6,350.2
XS Rating Curve= 0 ,0
Exp/Cntr(USF)=0,0
Exp/Cntr=0.5,0.3

Type RM Length L Ch R = 1 ,14057   ,120,120,120
XS GIS Cut Line= 3
2432526.39221689549144.7343523142432987.14123992549164.437435536
2433243.28132181548912.844219011
#Sta/Elev= 30
       0 2282.67    13.1 2280.48    34.4 2278.09    38.2 2277.27    49.1 2273.74
    53.1    2273    69.1 2271.24    93.1 2269.81   105.1 2269.27   181.2 2269.17
   209.2 2267.95   241.3 2268.06   257.3 2266.84   277.3 2267.29   297.3  2267.1
   305.3 2266.12   309.3 2265.57   317.3 2265.38   325.3 2265.38   333.3  2266.2
   337.3 2267.22   345.3 2270.41   349.3 2271.06   361.4 2269.98   429.4 2270.52
   453.4  2272.5     491 2273.67   525.3 2275.51   696.5 2281.89   820.2 2285.42
#Mann= 3 ,-1 , 0
       0     .05       0   305.3    .045       0   333.3     .05       0
Bank Sta=305.3,333.3
XS Rating Curve= 0 ,0
Exp/Cntr(USF)=0,0
Exp/Cntr=0.5,0.3

Type RM Length L Ch R = 1 ,13937   ,322.4,322.4,322.4
XS GIS Cut Line= 3
2432635.97561276549381.4440315852433028.78106506549202.896098723
2433325.44532274548963.916557814
#Sta/Elev= 30
       0 2276.82     8.2 2274.16      17 2271.96    30.2 2269.64    40.3 2268.68
     140 2268.16   144.4 2267.93   161.2 2266.05   179.3 2266.96   192.7 2265.65
   201.5  2265.1   220.5 2265.15   241.1 2263.67   249.8 2263.85   263.8 2263.88
   267.4 2264.28   276.2 2267.34   280.6 2268.16   324.5 2267.69   346.5 2268.39
   391.3 2268.26   396.7 2268.79   413.8 2271.32   434.8 2272.98     450 2273.94
   475.1 2274.82   523.9 2277.16   588.9 2279.62   645.4 2280.69   812.4 2285.95
#Mann= 3 ,-1 , 0
       0     .05       0   249.8    .045       0   263.8     .05       0
Bank Sta=249.8,263.8
XS Rating Curve= 0 ,0
Exp/Cntr(USF)=0,0
Exp/Cntr=0.3,0.1

Type RM Length L Ch R = 1 ,13614   ,296.3,296.3,296.3
XS GIS Cut Line= 2
2432825.03626643549661.7180305082433388.14897776549161.783818493
#Sta/Elev= 30
       0 2306.29    31.6 2294.62    51.3 2286.38    74.1 2277.72    96.9 2269.76
   105.8 2267.78   120.9 2265.98   142.1 2264.25   153.4 2264.45   163.6 2261.18
   172.1 2260.34   179.7 2260.45     185 2261.26   190.4 2262.79   202.2 2262.96
   221.4 2264.68   233.2  2265.1   249.8 2264.93   310.6 2266.22   334.7 2265.56
   371.6 2266.01   388.3 2267.18   416.9 2267.49   425.1 2268.12   447.1 2271.48
   453.8 2272.01   557.6 2276.44   602.2 2277.38   635.1 2278.84     753 2282.46
#Mann= 3 ,-1 , 0
       0     .05       0   163.6    .045       0     185     .05       0
Bank Sta=163.6,185
XS Rating Curve= 0 ,0
Exp/Cntr(USF)=0,0
Exp/Cntr=0.3,0.1

Type RM Length L Ch R = 1 ,13318   ,415,415,415
XS GIS Cut Line= 2
2432998.09041674549897.950680142 2433569.4438019549400.763359401
#Sta/Elev= 30
       0 2282.09    17.6 2277.95    33.6 2274.92    48.1 2272.53    59.4 2270.81
   101.3 2265.87   118.9 2264.41   127.4    2264     170 2263.56   192.7 2263.75
   198.8 2263.26   208.5 2260.93   212.5 2260.44   245.6 2260.14   253.6 2260.42
   261.5 2260.94   277.4  2262.7   291.9 2263.31   297.5 2263.15   306.1 2262.47
   323.1 2263.33   351.4 2263.59   410.9 2263.53   419.4 2263.85   436.4 2264.84
   473.3 2269.16   510.7 2271.12   547.8 2272.03   697.3 2274.62   757.4 2276.64
#Mann= 3 ,-1 , 0
       0     .05       0   212.5    .045       0   253.6     .05       0
Bank Sta=212.5,253.6
XS Rating Curve= 0 ,0
Exp/Cntr(USF)=0,0
Exp/Cntr=0.3,0.1

Type RM Length L Ch R = 1 ,12903   ,155.9,155.9,155.9
XS GIS Cut Line= 2
2433140.92876303550293.5030237152433783.70132134549741.377877478
#Sta/Elev= 30
       0 2306.42    40.1 2296.54    74.1 2284.06   124.5 2268.74   150.7 2262.97
   164.9 2261.94   198.3 2261.31   208.9  2261.7   236.5 2261.12   251.1 2261.63
   335.4 2261.18   354.9 2260.41     367 2256.66   374.8 2256.24   383.8 2256.53
   393.4 2256.48   398.7 2257.22   408.8 2259.81   426.8 2260.64     462  2260.6
   477.8 2260.13   488.3 2259.19   500.4 2260.72   555.7 2260.34     599  2261.6
     660  2265.9   737.8 2269.73   746.7 2268.82   762.5 2270.87   847.3 2275.65
#Mann= 3 ,-1 , 0
       0     .05       0     367    .045       0   383.8     .05       0
Bank Sta=367,383.8
XS Rating Curve= 0 ,0
Exp/Cntr(USF)=0,0
Exp/Cntr=0.3,0.1

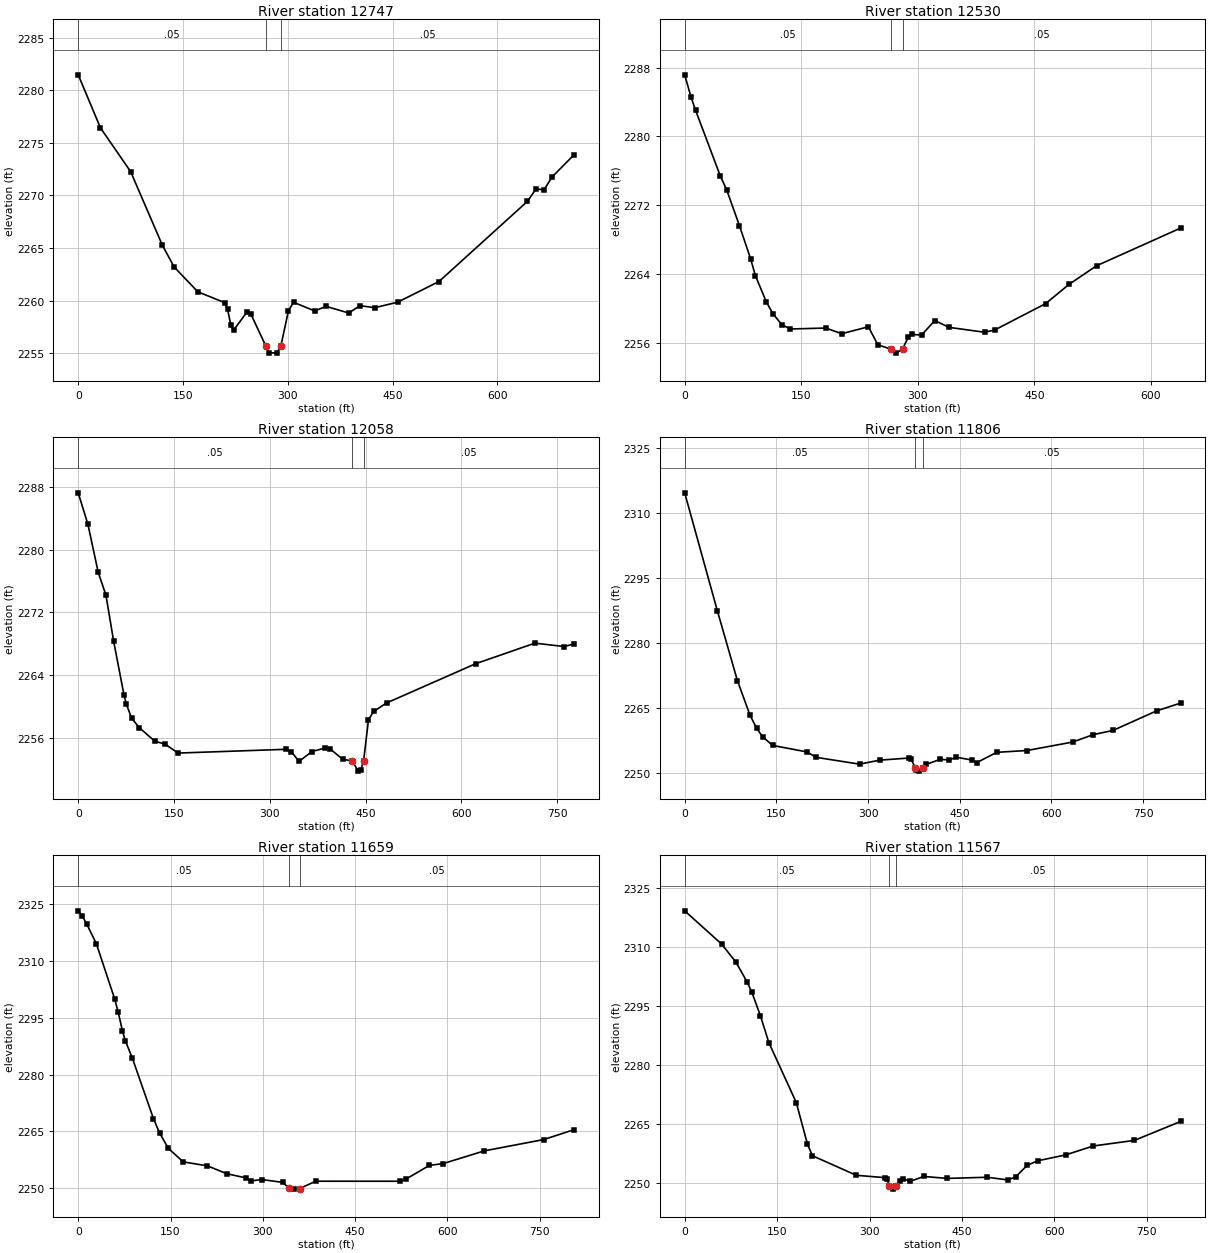
Type RM Length L Ch R = 1 ,12747   ,217.5,217.5,217.5
XS GIS Cut Line= 2
2433327.71736972550345.6939579362433855.12049448549870.481767394
#Sta/Elev= 30
       0 2281.46    31.8 2276.43    75.1 2272.26   120.3  2265.3   137.3 2263.21
   171.3 2260.85   209.5 2259.83   213.8 2259.18   218.5 2257.69   222.3  2257.2
   241.8 2258.95   247.2 2258.73   268.7 2255.69   273.3 2255.08   284.3 2255.03
   290.2 2255.75     301 2259.07   308.2 2259.86   338.4 2259.04   354.9 2259.47
   387.2 2258.84   403.3 2259.53   424.8 2259.35   457.3 2259.87   516.4 2261.83
   642.8 2269.43   655.6 2270.64   666.7 2270.52   677.9 2271.73   709.9 2273.88
#Mann= 3 ,-1 , 0
       0     .05       0   268.7    .045       0   290.2     .05       0
Bank Sta=268.7,290.2
XS Rating Curve= 0 ,0
Exp/Cntr(USF)=0,0
Exp/Cntr=0.3,0.1

Type RM Length L Ch R = 1 ,12530   ,471.4,471.4,471.4
XS GIS Cut Line= 2
2433459.56815091550491.2791955012433964.99614547550101.220634478
#Sta/Elev= 30
       0 2287.17     8.3 2284.54      14 2283.05    45.7 2275.43      54 2273.79
    70.5 2269.61      85 2265.71      91  2263.8   105.3 2260.69   113.8 2259.33
   125.2 2258.07   136.1 2257.58   181.6 2257.69   202.2 2257.03   236.5 2257.84
   248.6 2255.75     265 2255.24   272.5 2254.77   280.62255.279   287.8 2256.63
   292.8 2256.94   304.9 2256.88     322 2258.56   340.3 2257.77   386.1  2257.2
   399.2 2257.47   464.6 2260.53   494.8 2262.78   530.2 2264.94   638.4 2269.33
#Mann= 3 ,-1 , 0
       0     .05       0     265    .045       0   280.6     .05       0
Bank Sta=265,280.6
XS Rating Curve= 0 ,0
Exp/Cntr(USF)=0,0
Exp/Cntr=0.3,0.1

Type RM Length L Ch R = 1 ,12058   ,252.7,252.7,252.7
XS GIS Cut Line= 3
2433484.29017238550763.2214317082433989.71816695550700.042932387
2434220.45703403550565.445259921
#Sta/Elev= 30
       0 2287.24    15.2 2283.22    31.3 2277.12    43.4  2274.2    55.5 2268.33
    71.6 2261.52    75.6 2260.28    83.7 2258.52    95.8 2257.31     120  2255.6
   136.1 2255.23   156.3 2254.09   325.5 2254.57   333.6 2254.29   345.7 2253.02
   365.8 2254.28     386 2254.72   394.1 2254.64   414.2 2253.29     429  2253.1
   438.4 2251.79   442.4 2251.89   446.9 2253.14   454.5 2258.36   462.6 2259.39
   482.7 2260.47   622.3 2265.47   714.9 2268.09   761.2 2267.66   776.5 2268.01
#Mann= 3 ,-1 , 0
       0     .05       0     429    .045       0   446.9     .05       0
Bank Sta=429,446.9
XS Rating Curve= 0 ,0
Exp/Cntr(USF)=0,0
Exp/Cntr=0.3,0.1

Type RM Length L Ch R = 1 ,11806   ,147,147,147
XS GIS Cut Line= 3
 2433503.5184113551037.910559189 2434114.3308863550887.106461631
2434268.61210561550789.701726038
#Sta/Elev= 30
       0  2314.6    53.4 2287.46    86.3 2271.34   106.9 2263.38   117.6  2260.4
   127.6 2258.39     144 2256.41   200.2 2254.91     215 2253.67   286.1  2252.1
   319.2 2253.02   366.5  2253.5   370.6 2253.29   377.32251.238   378.8 2250.71
     383 2250.49   390.32251.213   395.5 2252.05   418.3 2253.22   432.4 2253.05
   444.8 2253.69   469.5 2253.06   477.8 2252.44   510.7 2254.82   560.1 2255.24
     635 2257.19   668.1 2258.87   701.2 2259.88   772.2 2264.37   811.6 2266.16
#Mann= 3 ,-1 , 0
       0     .05       0   377.3    .045       0   390.3     .05       0
Bank Sta=377.3,390.3
XS Rating Curve= 0 ,0
Exp/Cntr(USF)=0,0
Exp/Cntr=0.3,0.1

Type RM Length L Ch R = 1 ,11659   ,91.8,91.8,91.8
XS GIS Cut Line= 3
2433601.44447382551266.3150325622434123.87930356550956.673501622
2434264.37744315550816.175362032
#Sta/Elev= 30
       0 2323.27     6.9 2321.82    13.8 2319.79    29.5 2314.58    59.1 2300.07
    64.9 2296.59    71.9 2291.54    76.5 2288.99    88.2 2284.28   122.3 2268.39
   132.4 2264.56   146.6 2260.52   170.7 2256.97   209.9 2255.93   241.3 2253.86
   272.2 2252.75   280.9 2251.95   298.4 2252.31   332.3 2251.56   343.2 2249.96
   350.6 2249.78   359.7 2249.91     386 2251.87   523.2 2251.86     532 2252.36
   570.7 2256.05   593.3 2256.53   660.1 2259.89   756.3 2262.86     806 2265.49
#Mann= 3 ,-1 , 0
       0     .05       0   343.2    .045       0   359.7     .05       0
Bank Sta=343.2,359.7
XS Rating Curve= 0 ,0
Exp/Cntr(USF)=0,0
Exp/Cntr=0.5,0.3

Type RM Length L Ch R = 1 ,11567   ,72.8,72.8,72.8
XS GIS Cut Line= 3
2433702.37569777551392.0260196312434134.79178042550992.139051421
2434276.45720215550829.138573008
#Sta/Elev= 30
       0 2319.15      60 2310.71    83.3 2306.09   101.3 2301.11   108.8 2298.58
   122.9 2292.55   136.6 2285.72   181.1 2270.51   199.3 2259.94   207.3 2257.01
   278.6 2252.05   325.1 2251.45   328.2 2251.02   332.3 2249.44     338 2248.54
   342.8 2249.27   349.3 2250.68   354.6 2251.17   366.3 2250.53   388.1 2251.76
   425.7 2251.26   490.8 2251.55   524.3 2250.88   537.2 2251.64   555.9 2254.59
   572.9 2255.73   618.3 2257.22   662.9 2259.48     730 2260.91   804.9 2265.71
#Mann= 3 ,-1 , 0
       0     .05       0   332.3    .045       0   342.8     .05       0
#XS Ineff= 2 , 0
          327.71  2250.3  348.99          2250.2
Permanent Ineff=
       F       F
Bank Sta=332.3,342.8
XS Rating Curve= 0 ,0
Exp/Cntr(USF)=0,0
Exp/Cntr=0.5,0.3

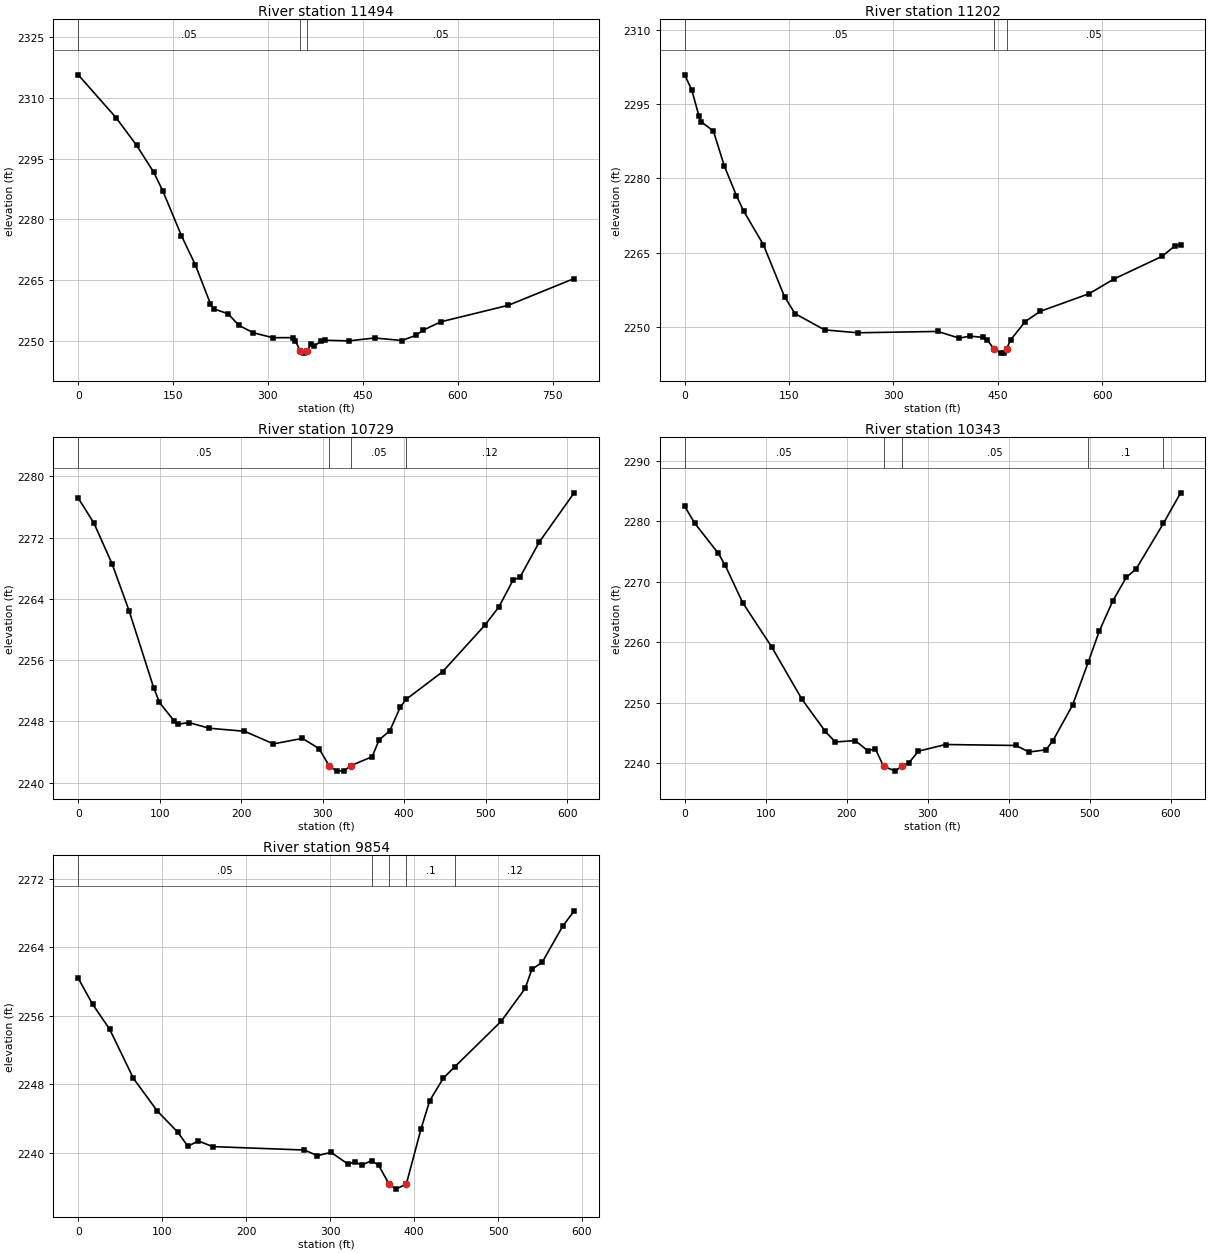
Type RM Length L Ch R = 1 ,11494   ,292.1,292.1,292.1
XS GIS Cut Line= 2
 2433758.3113287551449.0990199892434317.57576785  550899.3829981
#Sta/Elev= 30
       0 2315.63    59.7  2305.1    92.5 2298.23   119.2 2291.68   133.8 2287.02
   163.2 2276.02   185.2 2268.83   208.9 2259.29   214.1 2257.99     237 2256.78
   253.7 2253.97   276.3 2252.12   307.5 2250.88   339.2 2250.89   343.5 2250.12
   350.7 2247.68   356.4 2247.08   362.1 2247.56   367.8  2249.3   373.5 2248.86
   383.8 2250.03   389.5 2250.26   427.6 2250.09   468.7 2250.81   511.8 2250.19
   534.2 2251.47   545.4 2252.74   573.4 2254.79     680 2258.86   784.2 2265.45
#Mann= 3 ,-1 , 0
       0     .05       0   350.7    .045       0   362.1     .05       0
Bank Sta=350.7,362.1
XS Rating Curve= 0 ,0
Exp/Cntr(USF)=0,0
Exp/Cntr=0.5,0.3

Type RM Length L Ch R = 1 ,11202   ,472.8,472.8,472.8
XS GIS Cut Line= 3
2433951.41838452551570.5508457982434278.11908068551301.106972679
2434433.04930772551056.923462664
#Sta/Elev= 30
       0 2300.87    10.2 2297.81    20.6 2292.53      24  2291.4    41.3 2289.54
    56.9 2282.53    74.3 2276.55    84.7 2273.44   113.1 2266.66   143.5 2256.17
   158.5 2252.78   201.1 2249.49   248.7 2248.91   363.5 2249.18   394.9 2247.82
   409.4 2248.24   428.5 2247.98   435.1 2247.43   444.6 2245.61   454.1 2244.81
   458.8 2244.93   462.52245.632   468.3 2247.46   489.4 2251.17   510.9 2253.22
   581.2 2256.78   616.9 2259.74   686.2 2264.32   705.1 2266.49   712.7 2266.53
#Mann= 3 ,-1 , 0
       0     .05       0   444.6    .045       0   462.5     .05       0
Bank Sta=444.6,462.5
XS Rating Curve= 0 ,0
Exp/Cntr(USF)=0,0
Exp/Cntr=0.3,0.1

Type RM Length L Ch R = 1 ,10729   ,385.8,385.8,385.8
XS GIS Cut Line= 2
2434165.51920853551779.5712033882434728.63191987551548.832336304
#Sta/Elev= 30
       0 2277.17    19.2 2273.92    41.5  2268.6    62.4 2262.46    92.7 2252.37
    99.7 2250.47   118.1 2248.01   122.9 2247.64   135.9 2247.84     161  2247.1
     204 2246.71   239.6 2245.06   275.2 2245.78   295.5 2244.44   308.2 2242.16
   317.4  2241.5   326.6 2241.57   334.7 2242.22   360.7 2243.38   369.3  2245.6
   382.3 2246.75   395.2 2249.86  402.262250.866   447.1 2254.48     499 2260.56
   516.3 2262.96   533.5 2266.44   542.2 2266.85   565.8 2271.43   608.6 2277.86
#Mann= 4 ,-1 , 0
       0     .05       0   308.2    .045       0   334.7     .05       0
  402.26     .12       0
Bank Sta=308.2,334.7
XS Rating Curve= 0 ,0
Exp/Cntr(USF)=0,0
Exp/Cntr=0.3,0.1

Type RM Length L Ch R = 1 ,10343   ,488.9,488.9,488.9
XS GIS Cut Line= 2
 2434311.1044461552089.9699174412434904.43296146551938.890897327
#Sta/Elev= 30
       0  2282.5    12.5 2279.69    41.4 2274.75    49.7 2272.84    71.5  2266.6
   107.5 2259.24   144.6 2250.65   173.5 2245.31   185.9 2243.55   210.6 2243.77
   226.1  2242.1   235.4 2242.42   245.5 2239.53   260.2 2238.73   267.7 2239.55
   276.7 2240.09   288.6 2242.03   322.1 2243.13   408.8 2242.97   425.3 2241.89
   445.9 2242.25   454.2 2243.66   478.9 2249.64  498.412256.806   511.9 2261.88
   528.4 2266.82   545.2 2270.76   557.3 2272.13  591.032279.671   612.3 2284.73
#Mann= 5 ,-1 , 0
       0     .05       0   245.5    .045       0   267.7     .05       0
  498.41      .1       0  591.03     .12       0
Bank Sta=245.5,267.7
XS Rating Curve= 0 ,0
Exp/Cntr(USF)=0,0
Exp/Cntr=0.3,0.1

Type RM Length L Ch R = 1 ,9854    ,299,299,299
XS GIS Cut Line= 2
2434514.37440044552425.090652968 2435096.7153507552326.202567075
#Sta/Elev= 30
       0 2260.39    17.1 2257.36    37.4 2254.45    65.8  2248.7    94.2  2244.9
   118.5 2242.44   130.7 2240.78   142.9 2241.42     160 2240.75   269.5 2240.35
   284.9 2239.69   301.1 2240.08   321.4 2238.71   329.5 2238.96   337.6 2238.59
  349.452239.112   357.9 2238.56   370.1  2236.4   378.2 2235.79   390.8 2236.38
   408.2 2242.77   418.7 2246.11     435 2248.75  448.782250.085   503.9 2255.38
   532.3  2259.2   540.4 2261.44   552.6 2262.24   576.9 2266.43   590.7 2268.25
#Mann= 5 ,-1 , 0
       0     .05       0  349.45      .1       0   370.1    .045       0
   390.8      .1       0  448.78     .12       0
Bank Sta=370.1,390.8
XS Rating Curve= 0 ,0
Exp/Cntr(USF)=0,0
Exp/Cntr=0.3,0.1