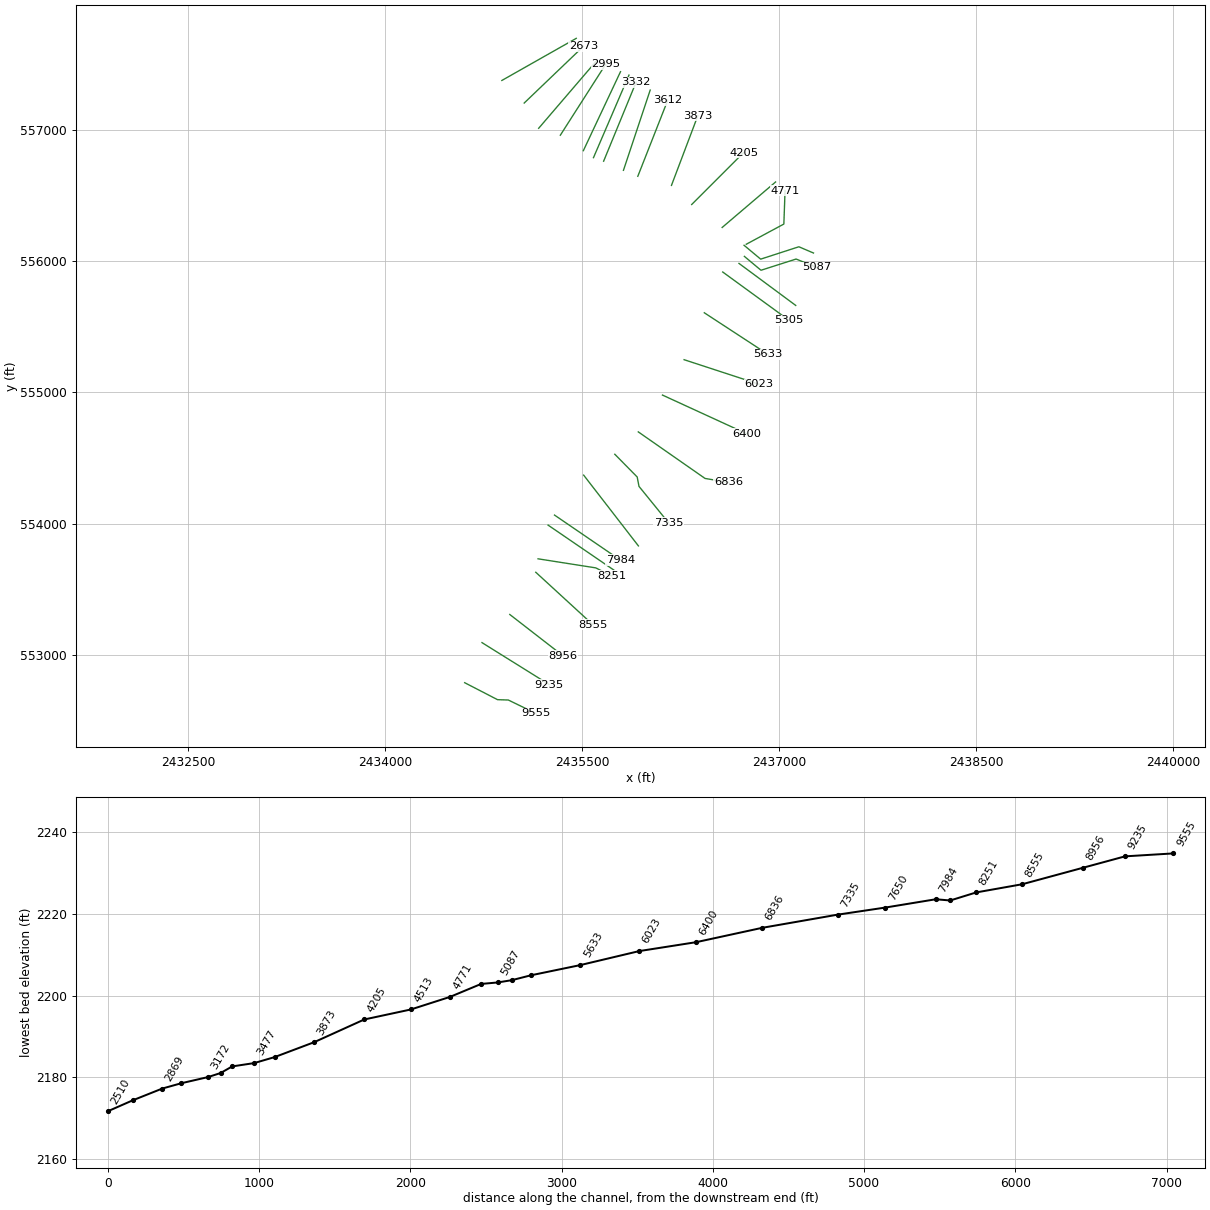
HEC-RAS study WHITHORNCK.prj: WHITHORNCK

--- WHITHORNCK.g01 (geometry) --- (continued)

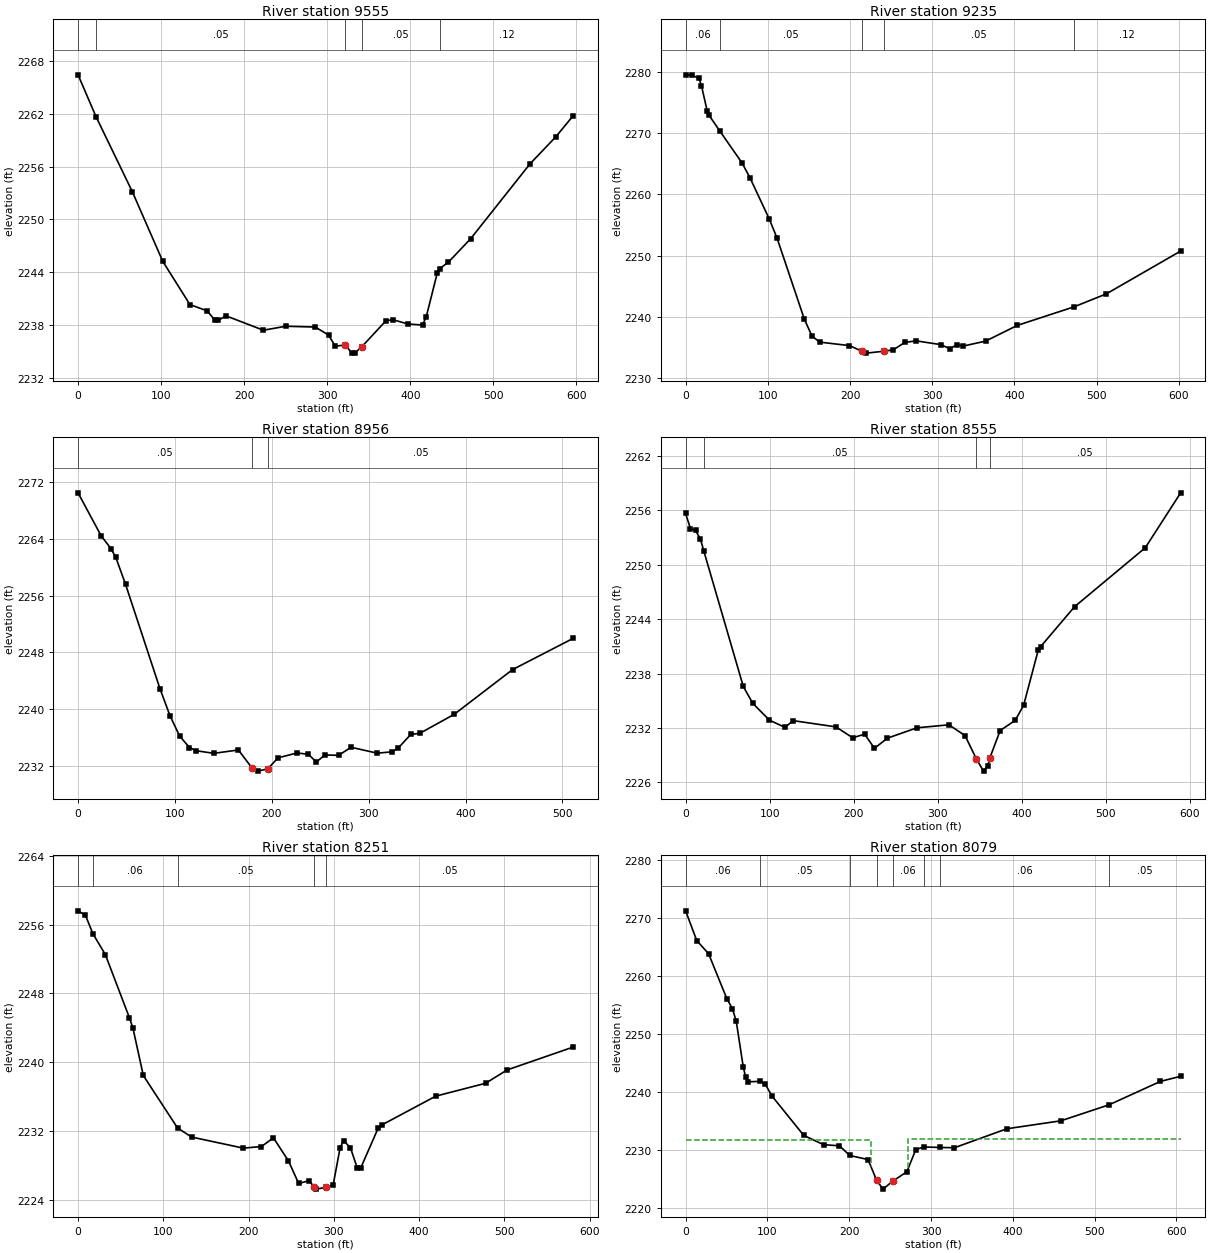
Type RM Length L Ch R = 1 ,9555    ,320,320,320
XS GIS Cut Line= 4
 2434605.0218125552790.4271925182434854.98891851552661.323302602
2434937.39565676552658.5764113272435146.15939364552556.941434159
#Sta/Elev= 30
       0 2266.47   21.562261.724    65.5 2253.13     102 2245.23   134.7 2240.31
   155.5 2239.59   164.5 2238.56     169 2238.51     178 2239.03   223.1 2237.39
   250.1 2237.84   285.6 2237.75   301.6 2236.84   309.6 2235.57   321.6  2235.7
   329.6 2234.81   333.1 2234.78   341.92235.533   370.7 2238.47   379.1 2238.59
   396.9  2238.1   414.7 2237.98   419.2 2238.91   432.5 2243.92   435.42244.402
   445.9 2245.14   472.6  2247.8   544.2 2256.34   574.9 2259.38     596  2261.8
#Mann= 5 ,-1 , 0
       0     .06       0   21.56     .05       0   321.6    .045       0
   341.9     .05       0   435.4     .12       0
Bank Sta=321.6,341.9
XS Rating Curve= 0 ,0
Exp/Cntr(USF)=0,0
Exp/Cntr=0.3,0.1

Type RM Length L Ch R = 1 ,9235    ,279,279,279
XS GIS Cut Line= 2
 2434736.8725937553095.3321240222435247.79437081552776.692736144
#Sta/Elev= 30
       0 2279.54     7.7  2279.5    16.4 2278.94    19.3 2277.74    26.3 2273.61
      28 2273.03    41.72270.336    68.6 2265.15    78.2 2262.74   101.7 2255.99
   111.2 2252.86   144.3 2239.65   153.6 2236.87     163 2235.86   199.3 2235.29
   214.9 2234.35   219.6 2234.06   240.92234.366   252.6  2234.6   266.7 2235.82
   280.6 2236.06   310.3 2235.45   321.2 2234.79   329.9 2235.42   337.4 2235.21
   364.8 2236.02   403.4 2238.59  472.462241.626   511.8 2243.75   602.1 2250.74
#Mann= 5 ,-1 , 0
       0     .06       0    41.7     .05       0   214.9    .045       0
   240.9     .05       0  472.46     .12       0
Bank Sta=214.9,240.9
XS Rating Curve= 0 ,0
Exp/Cntr(USF)=0,0
Exp/Cntr=0.3,0.1

Type RM Length L Ch R = 1 ,8956    ,401.6,401.6,401.6
XS GIS Cut Line= 2
2434948.38322186553309.5896434582435352.17623925552996.444038129
#Sta/Elev= 30
       0 2270.49    23.8 2264.44    33.9 2262.64      39 2261.38    49.1 2257.57
    84.5  2242.9      95 2239.04   104.8 2236.22     115 2234.59   121.6 2234.14
   140.2 2233.77   165.5 2234.24   179.82231.671   185.8 2231.26   195.9 2231.59
   206.4 2233.13     226 2233.82   237.6 2233.64   246.1 2232.54   254.7 2233.54
   268.9 2233.49   281.9 2234.62   308.8 2233.79   323.9 2233.98   330.4  2234.5
   343.5 2236.44   352.8 2236.59   388.2 2239.26   448.5 2245.57     511 2249.97
#Mann= 3 ,-1 , 0
       0     .05       0   179.8    .045       0   195.9     .05       0
Bank Sta=179.8,195.9
XS Rating Curve= 0 ,0
Exp/Cntr(USF)=0,0
Exp/Cntr=0.3,0.1

Type RM Length L Ch R = 1 ,8555    ,303.9,303.9,303.9
XS GIS Cut Line= 2
2435146.15939364553630.9759226112435580.16821506553232.676687763
#Sta/Elev= 30
       0 2255.66     5.8 2253.98    11.8  2253.8    17.7 2252.81   21.722251.502
    68.6 2236.58    79.9 2234.71    99.8 2232.85   118.2 2232.06   128.1  2232.8
     179 2232.11   198.8 2230.91     213 2231.31   224.7 2229.75   240.2 2230.87
   275.3 2232.01   313.4 2232.34   332.5 2231.15     346 2228.58   354.5 2227.23
   359.7 2227.84   361.82228.629   374.3 2231.71   392.2 2232.83   402.2 2234.49
   419.6 2240.58   422.5 2240.97   462.8 2245.37     547 2251.88   589.1 2257.94
#Mann= 4 ,-1 , 0
       0     .06       0   21.72     .05       0     346    .045       0
   361.8     .05       0
Bank Sta=346,361.8
XS Rating Curve= 0 ,0
Exp/Cntr(USF)=0,0
Exp/Cntr=0.3,0.1

Type RM Length L Ch R = 1 ,8251    ,171.8,171.8,171.8
XS GIS Cut Line= 3
2435163.56836568553733.3249810612435603.09868371553664.279988574
2435724.34842661553603.655117123
#Sta/Elev= 30
       0 2257.62     8.7  2257.1   17.342254.971      32 2252.53    60.3 2245.16
    64.4 2243.96    76.5 2238.46  116.66 2232.35   133.2 2231.29   193.9    2230
   215.1 2230.19   229.1  2231.2   246.6 2228.54   258.7 2225.89   270.9 2226.21
     2772225.479   278.9 2225.23   291.1 2225.44   299.2 2225.75   307.3 2230.04
   311.3 2230.88   319.4 2230.05   327.5 2227.66   331.6 2227.72   351.8  2232.3
     357 2232.74   419.4 2236.05   477.9 2237.55   503.1  2239.1   580.5 2241.76
#Mann= 5 ,-1 , 0
       0    .055       0   17.34     .06       0  116.66     .05       0
     277    .045       0   291.1     .05       0
Bank Sta=277,291.1
XS Rating Curve= 0 ,0
Exp/Cntr(USF)=0,0
Exp/Cntr=0.5,0.3

Type RM Length L Ch R = 1 ,8079    ,95.4,95.4,95.4
XS GIS Cut Line= 2
2435239.93751739553989.784657491  2435739.487909553648.313704837
#Sta/Elev= 30
       0 2271.23    13.6 2266.11    28.1 2263.83    50.4 2256.08    57.2 2254.38
    61.9 2252.19    70.5 2244.28    73.4 2242.55    76.3 2241.76   90.942241.834
    97.1 2241.42   105.6  2239.3   144.4 2232.52   168.6 2230.92     188 2230.73
  200.662229.057     223 2228.36   233.42224.798   241.3 2223.26     253 2224.61
   270.4 2226.25   281.4 2230.09  291.342230.532  310.372230.447   328.5 2230.39
   392.8 2233.67   458.5 2235.03  517.672237.799   580.4 2241.83   605.1 2242.71
#Mann= 8 ,-1 , 0
       0     .06       0   90.94     .05       0  200.66     .06       0
   233.4    .045       0     253     .06       0  291.34     .05       0
  310.37     .06       0  517.67     .05       0
#XS Ineff= 2 , 0
          226.58  2231.7  272.25         2231.84
Permanent Ineff=
       F       F
Bank Sta=233.4,253
XS Rating Curve= 0 ,0
Exp/Cntr(USF)=0,0
Exp/Cntr=0.5,0.3

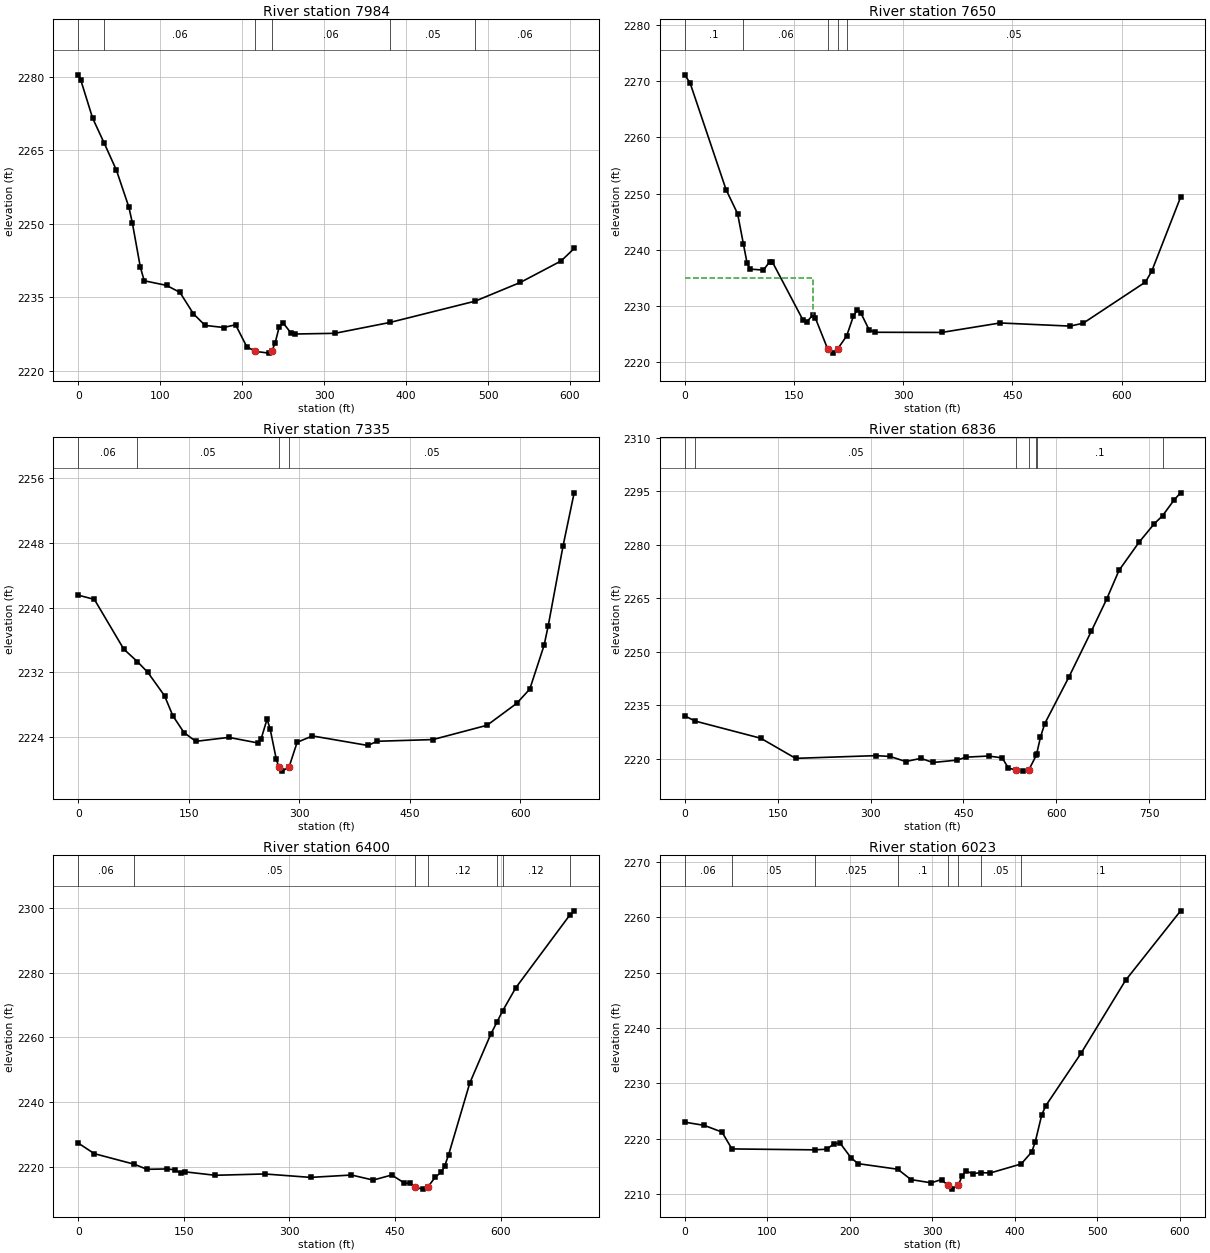
Type RM Length L Ch R = 1 ,7984    ,333.5,333.5,333.5
XS GIS Cut Line= 2
2435288.66309063554066.3534154482435788.21348225553724.882462794
#Sta/Elev= 30
       0 2280.47       3 2279.47    17.6 2271.61   31.622266.533    46.6 2260.98
    61.8 2253.42      66 2250.24    75.7 2241.23    80.5 2238.36   107.8 2237.41
   124.1 2235.98   140.6  2231.6   154.8 2229.23   177.4  2228.8     192 2229.36
   205.7 2224.86   216.2 2223.91   232.8 2223.56   236.22223.993   240.2 2225.59
   245.3 2228.97   250.1 2229.72   259.8 2227.63   264.6 2227.47   313.1 2227.61
  380.492229.838  484.282234.186   539.5 2238.02   589.2 2242.41   605.1 2244.96
#Mann= 6 ,-1 , 0
       0      .1       0   31.62     .06       0   216.2    .045       0
   236.2     .06       0  380.49     .05       0  484.28     .06       0
Bank Sta=216.2,236.2
XS Rating Curve= 0 ,0
Exp/Cntr(USF)=0,0
Exp/Cntr=0.5,0.3

Type RM Length L Ch R = 1 ,7650    ,315.6,315.6,315.6
XS GIS Cut Line= 2
2435510.62632953554370.2623861522435927.42219826553831.498985672
#Sta/Elev= 30
       0 2271.17     7.4 2269.72    56.9 2250.67    72.7  2246.4    80.62241.038
    85.8 2237.52    90.2 2236.51   108.2 2236.35   116.8 2237.83   120.5 2237.78
   162.4 2227.45   168.1 2227.16   176.1 2228.34   179.5 2227.78   196.3 2222.31
   203.5 2221.53     210 2222.26  222.432224.577   231.7  2228.1   236.8 2229.19
   241.9 2228.71   253.6 2225.61   262.1 2225.25   353.1 2225.22   433.2 2226.91
   529.4 2226.35   547.3 2226.86   632.8  2234.2   641.4  2236.1   681.2 2249.36
#Mann= 5 ,-1 , 0
       0      .1       0    80.6     .06       0   196.3    .045       0
     210     .06       0  222.43     .05       0
#XS Ineff= 2 , 0
       0   176.1    2235               0
Permanent Ineff=
       F       F
Bank Sta=196.3,210
XS Rating Curve= 0 ,0
Exp/Cntr(USF)=0,0
Exp/Cntr=0.3,0.1

Type RM Length L Ch R = 1 ,7335    ,498.6,498.6,498.6
XS GIS Cut Line= 4
2435747.72858283554529.2093694742435918.03584186554356.155219161
2435931.77029824554284.7360460162436157.01538277 554007.30002726
#Sta/Elev= 30
       0 2241.54    21.9 2241.02    61.8 2234.87   80.222233.332    94.5 2231.99
   117.1 2229.11   128.4 2226.63   143.5 2224.56   159.5 2223.47   204.4 2223.96
     244 2223.27   248.1 2223.75   256.2  2226.2   260.3 2225.05   268.6 2221.33
   272.1 2220.29   276.6 2219.79     2862220.277     297 2223.35   317.8 2224.14
   393.1 2222.96   405.4 2223.48   481.2 2223.69   554.8 2225.46     595 2228.17
   612.7 2229.93   632.1 2235.34   637.6  2237.7   657.8 2247.61   672.9 2254.19
#Mann= 4 ,-1 , 0
       0     .06       0   80.22     .05       0   272.1    .045       0
     286     .05       0
Bank Sta=272.1,286
XS Rating Curve= 0 ,0
Exp/Cntr(USF)=0,0
Exp/Cntr=0.3,0.1

Type RM Length L Ch R = 1 ,6836    ,436.4,436.4,436.4
XS GIS Cut Line= 3
2435926.27651569554699.5166285122436434.45140153554345.167654062
2436612.99933439554314.951850039
#Sta/Elev= 30
       0 2232.07   16.682230.607   122.9 2225.78   179.1 2220.15   308.2 2220.91
   331.4 2220.69   356.9 2219.26   381.3 2220.15   400.8 2218.99   439.8 2219.66
   454.4 2220.49   490.5  2220.8   512.4 2220.29   522.7 2217.43   535.3 2216.85
   546.5 2216.57   555.5 2216.89  567.682221.033  568.032221.272   574.4 2226.11
   581.3  2229.9   620.1 2242.88   656.6 2255.83     681 2264.69   701.2 2272.85
   733.7 2280.76     758 2285.88  771.442288.137   790.5 2292.66   800.6 2294.56
#Mann= 7 ,-1 , 0
       0     .06       0   16.68     .05       0   535.3    .045       0
   555.5     .05       0  567.68     .12       0  568.03      .1       0
  771.44     .12       0
Bank Sta=535.3,555.5
XS Rating Curve= 0 ,0
Exp/Cntr(USF)=0,0
Exp/Cntr=0.3,0.1

Type RM Length L Ch R = 1 ,6400    ,376.4,376.4,376.4
XS GIS Cut Line= 2
 2436110.3182311554979.6995385432436750.34389813554685.782172138
#Sta/Elev= 30
       0 2227.31    22.8 2224.03   79.732220.749    97.6 2219.19   126.5  2219.3
   137.3 2219.03     146 2217.95     152  2218.4   194.5 2217.34   264.9 2217.75
   329.9 2216.69   388.1 2217.42   418.9 2215.86   445.3 2217.43   462.9 2214.98
   471.7 2214.82   477.7 2213.65   489.3 2213.06   496.3 2213.66     507 2216.75
   515.8 2218.37   520.2 2220.09     526 2223.68   556.1 2245.88   585.8 2260.93
  594.952264.849  602.942268.251   621.4 2275.32  697.992297.772   704.3 2299.12
#Mann= 7 ,-1 , 0
       0     .06       0   79.73     .05       0   477.7    .045       0
   496.3     .12       0  594.95      .1       0  602.94     .12       0
  697.99      .1       0
Bank Sta=477.7,496.3
XS Rating Curve= 0 ,0
Exp/Cntr(USF)=0,0
Exp/Cntr=0.3,0.1

Type RM Length L Ch R = 1 ,6023    ,390.2,390.2,390.2
XS GIS Cut Line= 2
2436275.13170759555248.8948834752436846.48509275555062.106276787
#Sta/Elev= 30
       0 2222.98    23.7  2222.4    45.2 2221.19   57.252218.145  157.782217.977
   172.4  2218.1   180.9 2219.09   188.6 2219.14   201.9 2216.49   210.3 2215.48
   258.32214.474   274.3  2212.6   298.7 2212.02   311.3 2212.61   318.7 2211.58
   323.9 2210.88   331.4 2211.54   336.5 2213.32   340.7 2214.16   349.2 2213.67
  358.83 2213.87   370.2 2213.79  407.882215.429   420.7 2217.61   424.9 2219.42
   432.8 2224.31   437.5 2225.91   480.4 2235.43   534.3  2248.6   601.1 2261.17
#Mann= 8 ,-1 , 0
       0     .06       0   57.25     .05       0  157.78    .025       0
   258.3      .1       0   318.7    .045       0   331.4      .1       0
  358.83     .05       0  407.88      .1       0
Bank Sta=318.7,331.4
XS Rating Curve= 0 ,0
Exp/Cntr(USF)=0,0
Exp/Cntr=0.3,0.1

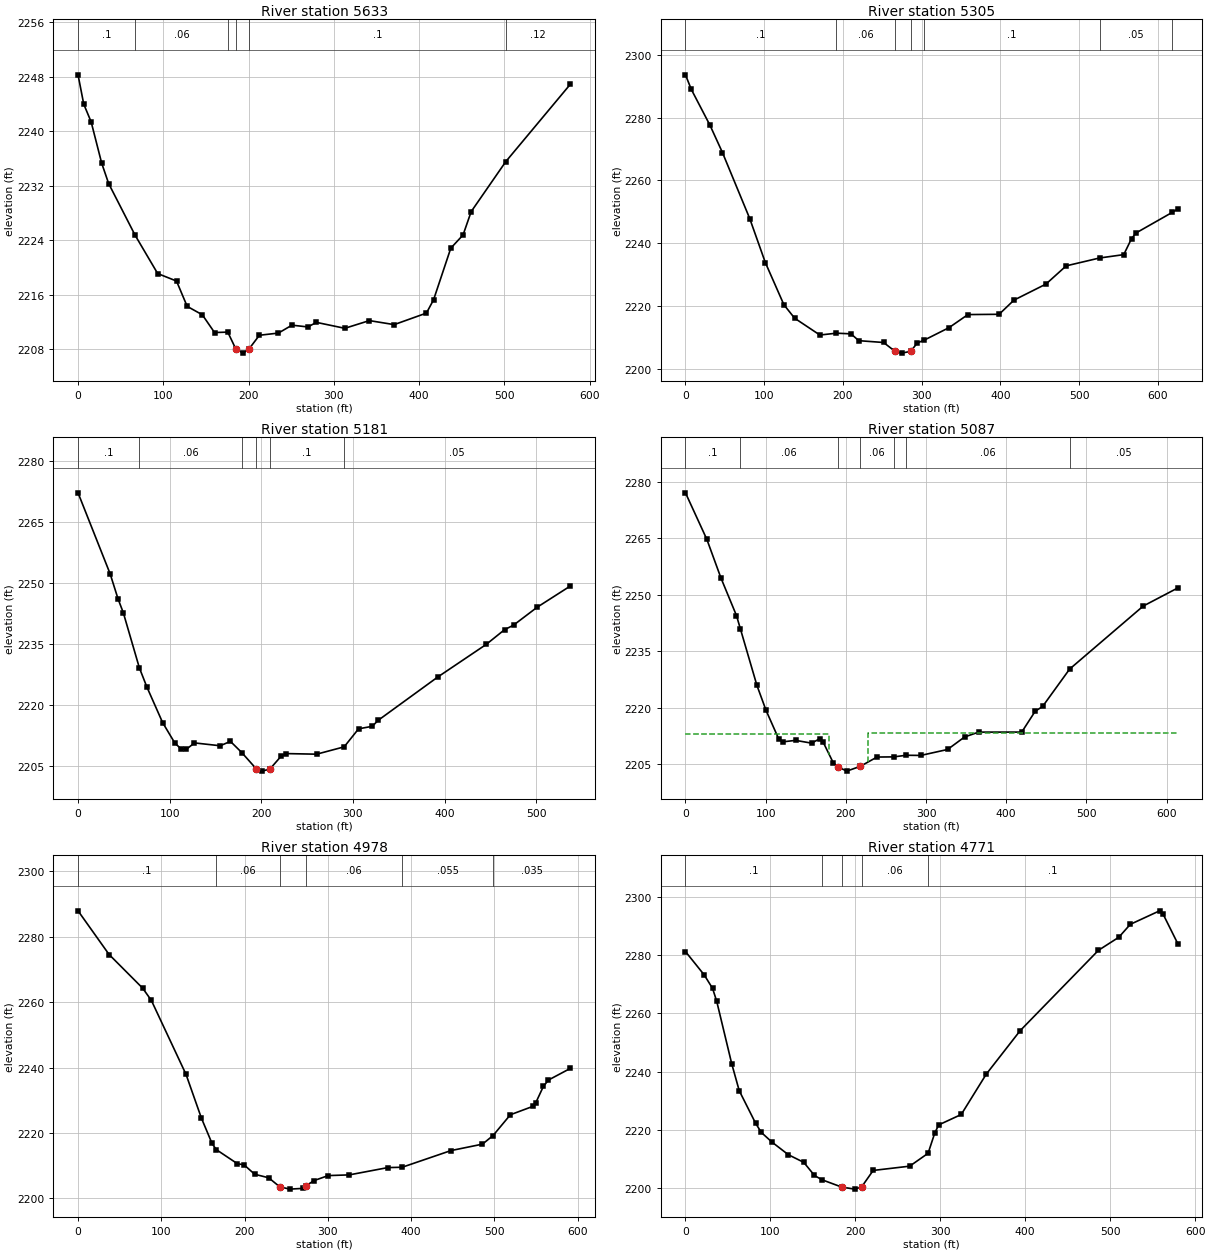
Type RM Length L Ch R = 1 ,5633    ,327.8,327.8,327.8
XS GIS Cut Line= 2
2436428.95761898  555605.99074922436912.41048335555290.098252597
#Sta/Elev= 30
       0 2248.26     6.7 2243.96    15.4 2241.35    27.7 2235.32    35.9 2232.32
   66.962224.732    93.4 2219.12   115.5 2218.02     128 2214.31   145.8 2213.07
   160.1 2210.47  175.642210.532     1852208.069   193.6 2207.45   200.3 2208.02
   212.7 2210.07     235 2210.39   250.9 2211.55   269.6 2211.29   279.6 2211.96
   312.9 2211.09   341.7 2212.22   370.8 2211.63   408.6 2213.32     417 2215.27
   437.2 2222.84   451.6 2224.78   461.1  2228.2  501.662235.527   577.5 2246.89
#Mann= 6 ,-1 , 0
       0      .1       0   66.96     .06       0  175.64      .1       0
     185    .045       0   200.3      .1       0  501.66     .12       0
Bank Sta=185,200.3
XS Rating Curve= 0 ,0
Exp/Cntr(USF)=0,0
Exp/Cntr=0.3,0.1

Type RM Length L Ch R = 1 ,5305    ,124.4,124.4,124.4
XS GIS Cut Line= 2
2436569.04907399555916.3894632542437074.47706856555548.306032429
#Sta/Elev= 30
       0 2293.66     7.4 2289.02    31.2 2277.55      47 2268.86    81.6 2247.85
   101.4 2233.83     125 2220.37   138.6 2216.08   170.7 2210.71  191.732211.298
   210.2 2211.09   220.1 2208.91   251.6 2208.33   265.9 2205.56   274.5 2204.94
     286 2205.51   294.4 2208.17  303.252209.095   334.7 2213.06   358.7 2217.23
   398.3 2217.32   417.2 2221.84   457.8 2226.95   483.5 2232.76  525.892235.269
   556.6 2236.34   566.5 2241.44   572.3 2243.26  617.962249.778   625.3 2250.91
#Mann= 7 ,-1 , 0
       0      .1       0  191.73     .06       0   265.9    .045       0
     286     .06       0  303.25      .1       0  525.89     .05       0
  617.96      .1       0
Bank Sta=265.9,286
XS Rating Curve= 0 ,0
Exp/Cntr(USF)=0,0
Exp/Cntr=0.3,0.1

Type RM Length L Ch R = 1 ,5181    ,94,94,94
XS GIS Cut Line= 2
2436692.85001113555981.7355120792437124.80222022 555661.93931517
#Sta/Elev= 30
       0  2272.1    35.1 2252.17    43.7 2246.03    49.4 2242.67   66.942229.122
    75.1 2224.44    92.3 2215.69   105.8  2210.6   112.2 2209.29     118 2209.08
   127.1 2210.69   155.2 2209.99   166.3 2211.07  178.712208.322   194.52204.322
     201 2203.76   209.5 2204.29   221.6 2207.41   226.8 2208.07   260.4 2207.92
  290.482209.725   306.2 2214.15   321.1 2214.76   327.6 2216.24   392.5 2226.85
   445.6 2234.89   465.5 2238.49   475.3  2239.6   501.2 2244.02   537.4 2249.23
#Mann= 6 ,-1 , 0
       0      .1       0   66.94     .06       0  178.71      .1       0
   194.5    .045       0   209.5      .1       0  290.48     .05       0
Bank Sta=194.5,209.5
XS Rating Curve= 0 ,0
Exp/Cntr(USF)=0,0
Exp/Cntr=0.5,0.3

Type RM Length L Ch R = 1 ,5087    ,109.2,109.2,109.2
XS GIS Cut Line= 4
2436733.83033095556035.1726553422436860.28810951 555929.65692928
2437127.70201068556015.0360663992437283.96194088555951.404445338
#Sta/Elev= 30
       0 2277.12    26.7 2264.74    44.3 2254.47    63.6 2244.53   68.632240.894
    89.1 2225.98   100.5 2219.34   116.1 2211.84   121.3 2210.98   137.4 2211.37
   157.3 2210.63   167.5 2211.81   171.7 2210.91   184.3 2205.43     190 2204.37
   201.1  2203.2   217.9 2204.46   238.9 2206.94  259.472206.984  275.482207.411
   293.5 2207.37   326.9 2208.95   348.1 2212.27   365.6 2213.56   419.4 2213.57
   436.2 2219.11   445.4 2220.37  479.112230.299   570.9 2247.04   614.1 2251.86
#Mann= 7 ,-1 , 0
       0      .1       0   68.63     .06       0     190    .045       0
   217.9     .06       0  259.47      .1       0  275.48     .06       0
  479.11     .05       0
#XS Ineff= 2 , 0
          179.32 2213.06  227.57         2213.39
Permanent Ineff=
       F       F
Bank Sta=190,217.9
XS Rating Curve= 0 ,0
Exp/Cntr(USF)=0,0
Exp/Cntr=0.5,0.3

Type RM Length L Ch R = 1 ,4978    ,206.4,206.4,206.4
XS GIS Cut Line= 4
2436731.41394027556119.7463289042436857.87171884556014.230602841
2437148.64406318556108.4698390962437259.79803415 556060.94748919
#Sta/Elev= 30
       0  2287.9    37.3 2274.55    77.6 2264.26      88 2260.54   129.7 2237.89
   148.1 2224.57   160.9  2216.8  165.942214.928   191.1 2210.65   199.5 2210.23
   212.1 2207.38   228.9 2206.31   242.2 2203.55   254.2 2202.84   270.2 2203.07
     274 2203.92   283.6 2205.47   300.4 2206.98   325.6 2207.19   371.9 2209.42
  389.212209.529   447.6 2214.61   485.6 2216.59  498.312219.212   519.1 2225.57
   546.5 2228.17   549.6 2229.23   558.7 2234.21   564.8 2236.18   591.2 2239.75
#Mann= 6 ,-1 , 0
       0      .1       0  165.94     .06       0   242.2    .045       0
     274     .06       0  389.21    .055       0  498.31    .035       0
Bank Sta=242.2,274
XS Rating Curve= 0 ,0
Exp/Cntr(USF)=0,0
Exp/Cntr=0.5,0.3

Type RM Length L Ch R = 1 ,4771    ,258.4,258.4,258.4
XS GIS Cut Line= 3
 2436748.3065075556127.6505026442437034.34869952556281.364087688
2437043.53265651556536.127700577
#Sta/Elev= 30
       0 2281.17      22 2273.18    31.9 2268.54    36.8 2264.09    54.5 2242.62
    63.3 2233.43    82.6 2222.25    89.3 2219.11   101.7 2215.83   121.1 2211.47
   139.3 2208.84   151.9 2204.34  160.532202.893     184 2200.36   199.2 2199.66
   207.4 2200.42     221 2206.07     264 2207.54  285.652211.955   293.6 2218.99
   298.2  2221.7   324.7 2225.27   354.1 2239.09   394.1 2254.04   486.2 2281.59
   510.2 2286.07   523.7  2290.5   558.2 2295.14   562.3 2294.03   579.7 2283.84
#Mann= 5 ,-1 , 0
       0      .1       0  160.53     .06       0     184    .045       0
   207.4     .06       0  285.65      .1       0
Bank Sta=184,207.4
XS Rating Curve= 0 ,0
Exp/Cntr(USF)=0,0
Exp/Cntr=0.3,0.1

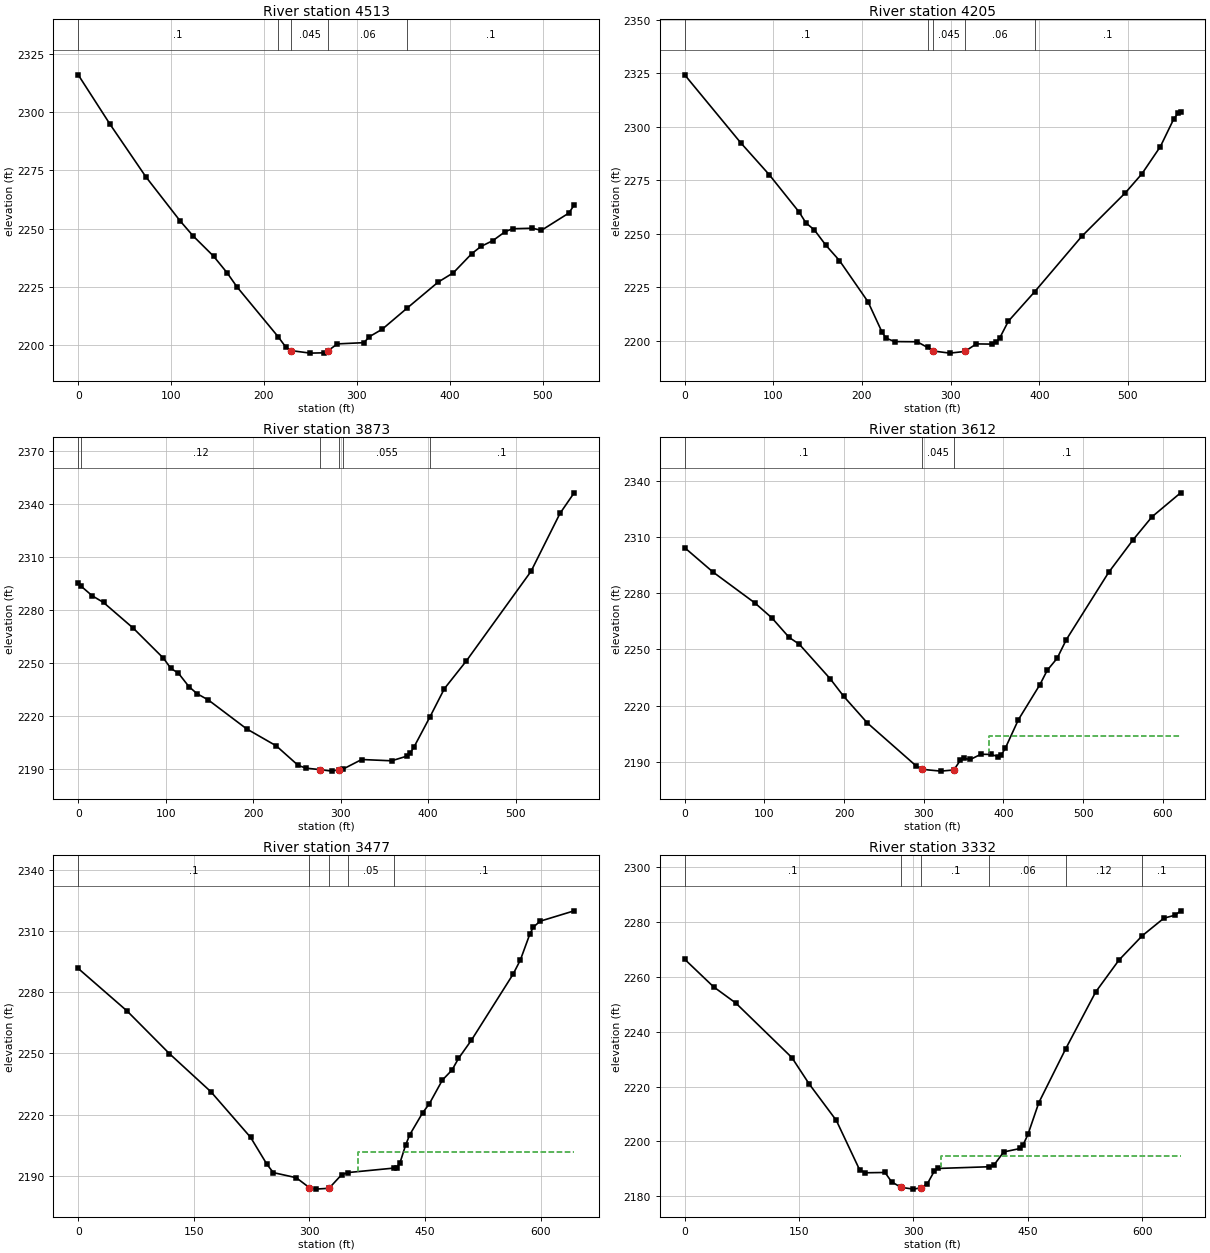
Type RM Length L Ch R = 1 ,4513    ,308.1,308.1,308.1
XS GIS Cut Line= 2
2436564.86660504556255.4963703642436971.40651371 556601.60467099
#Sta/Elev= 30
       0 2315.97    34.3 2294.73    72.9 2272.18   109.9 2253.21   123.6  2246.9
   145.7 2238.18   160.4 2230.99   170.9 2225.01  215.162203.658   223.4 2199.21
   228.7  2197.7   249.7 2196.59   264.9 2196.73   269.32197.716     279 2200.55
   307.5 2201.08   313.5 2203.65   327.3 2206.85  354.462216.026   387.5 2227.06
   403.9 2231.07   423.7 2239.27   433.5 2242.33   446.4 2244.86   459.8 2248.73
   467.7 2249.94     489 2250.17   498.6 2249.25   528.1 2256.65   533.9 2260.07
#Mann= 5 ,-1 , 0
       0      .1       0  215.16     .06       0   228.7    .045       0
   269.3     .06       0  354.46      .1       0
Bank Sta=228.7,269.3
XS Rating Curve= 0 ,0
Exp/Cntr(USF)=0,0
Exp/Cntr=0.3,0.1

Type RM Length L Ch R = 1 ,4205    ,332.1,332.1,332.1
XS GIS Cut Line= 2
2436332.81642436556430.0581316442436728.36876793556825.610475216
#Sta/Elev= 30
       0 2324.35    63.2 2292.56    95.4 2277.61   129.3 2260.03   136.7  2255.1
   146.3 2251.77   159.3  2244.6   174.6 2237.44   206.8 2218.16   222.6 2203.97
   227.2 2201.13   236.8 2199.54   262.2 2199.45  273.952196.803   280.3 2195.14
     299 2194.14     316 2194.92     329 2198.46   347.1 2198.35   351.6 2199.27
   355.6 2201.42   365.1 2209.08  394.762222.852   447.8 2248.74     497 2269.12
   515.7 2278.01   536.6  2290.8   551.8 2303.82   556.4 2306.28   559.4 2306.76
#Mann= 5 ,-1 , 0
       0      .1       0  273.95     .06       0   280.3    .045       0
     316     .06       0  394.76      .1       0
Bank Sta=280.3,316
XS Rating Curve= 0 ,0
Exp/Cntr(USF)=0,0
Exp/Cntr=0.3,0.1

Type RM Length L Ch R = 1 ,3873    ,261,261,261
XS GIS Cut Line= 2
2436178.99051297556575.6433692092436379.51357603557105.793385247
#Sta/Elev= 30
       0 2294.95    3.45 2293.25    16.1 2287.86    28.9 2284.11    63.1 2269.46
    97.4 2252.54   105.9 2246.76   114.5 2244.05   126.5 2236.46   135.8 2232.44
   148.7 2228.88   192.4 2212.54   226.3  2202.9   251.3 2191.86   260.2 2190.26
   276.62189.414   289.8 2188.57   298.3 2189.43  302.452189.671     324 2195.15
   358.2 2194.42   375.3 2197.01   379.6 2198.95   383.9 2202.36  402.11 2219.39
   418.5 2235.29   443.7 2251.06   517.5 2301.74   550.6 2334.54   566.8 2346.21
#Mann= 6 ,-1 , 0
       0      .1       0    3.45     .12       0   276.6    .045       0
   298.3     .12       0  302.45    .055       0  402.11      .1       0
Bank Sta=276.6,298.3
XS Rating Curve= 0 ,0
Exp/Cntr(USF)=0,0
Exp/Cntr=0.3,0.1

Type RM Length L Ch R = 1 ,3612    ,135,135,135
XS GIS Cut Line= 2
2435922.82430846556644.8957824532436150.67669032557224.134970078
#Sta/Elev= 30
       0 2304.36    35.5 2291.35      88 2274.85   109.4 2266.85   131.1 2256.39
   143.8 2252.77   182.5 2234.35   199.6 2224.89   229.4 2210.61   289.9 2187.93
   297.7  2185.9   321.6 2184.93   337.8 2185.56   345.8 2190.63   350.1 2191.68
   358.7  2191.2   371.7 2193.94   384.5 2193.86     393 2192.72   397.3 2193.49
   402.6 2197.37   418.8 2212.42   445.8 2231.14     455 2238.83   467.4 2245.22
     479 2255.24   532.1 2291.17   562.4 2308.39   586.5 2320.87   622.4 2333.68
#Mann= 3 , 0 , 0
       0      .1       0   297.7    .045       0   337.8      .1       0
#XS Ineff= 2 , 0
                          381.52         2203.72
Permanent Ineff=
       F       F
Bank Sta=297.7,337.8
XS Rating Curve= 0 ,0
Exp/Cntr(USF)=0,0
Exp/Cntr=0.3,0.1

Type RM Length L Ch R = 1 ,3477    ,144.8,144.8,144.8
XS GIS Cut Line= 2
2435813.52640171556690.4353175692436017.05430647557301.019031832
#Sta/Elev= 30
       0 2291.57    63.5  2270.7   118.4 2249.82   172.2 2231.17   223.7 2208.84
   244.9 2195.63   253.2 2191.56   282.9 2189.07   299.9 2184.22     308 2183.47
   325.52183.884   341.8 2190.51   350.2 2191.59   409.7 2193.78   413.4 2193.97
   417.7 2196.51   425.1 2205.28   430.3 2210.14   446.9 2220.81   455.6 2225.24
   472.6  2236.9   485.1 2241.81   493.5 2247.49   510.2 2256.39   564.3 2288.72
   573.8 2295.71     586 2308.33   590.5 2311.75   599.4 2314.71   643.6  2319.8
#Mann= 5 ,-1 , 0
       0      .1       0   299.9    .045       0   325.5      .1       0
   350.2     .05       0   409.7      .1       0
#XS Ineff= 2 , 0
                           363.4         2201.71
Permanent Ineff=
       F       F
Bank Sta=299.9,325.5
XS Rating Curve= 0 ,0
Exp/Cntr(USF)=0,0
Exp/Cntr=0.3,0.1

Type RM Length L Ch R = 1 ,3332    ,77,77,77
XS GIS Cut Line= 2
2435662.57495331556759.6850846212435909.79516804557361.254273805
#Sta/Elev= 30
       0 2266.32    37.8 2256.31    67.1 2250.37   140.6 2230.53   163.2 2220.96
   198.9 2207.65   229.5 2189.64   236.8 2188.61   262.7 2188.72   271.3 2185.34
   283.5 2183.32     300 2182.66   310.3 2183.15   318.4 2184.69   327.5 2189.27
   331.9 2190.18  399.482190.804   405.4 2191.35   418.4 2196.19     440 2197.45
     444 2198.87   450.2 2202.57   464.4 2214.11  499.78 2233.78     539 2254.41
   569.6 2266.05  600.082274.881   628.5 2281.28   643.3 2282.38   650.4 2283.95
#Mann= 6 ,-1 , 0
       0      .1       0   283.5    .045       0   310.3      .1       0
  399.48     .06       0  499.78     .12       0  600.08      .1       0
#XS Ineff= 2 , 0
                             336         2194.69
Permanent Ineff=
       F       F
Bank Sta=283.5,310.3
XS Rating Curve= 0 ,0
Exp/Cntr(USF)=0,0
Exp/Cntr=0.3,0.1

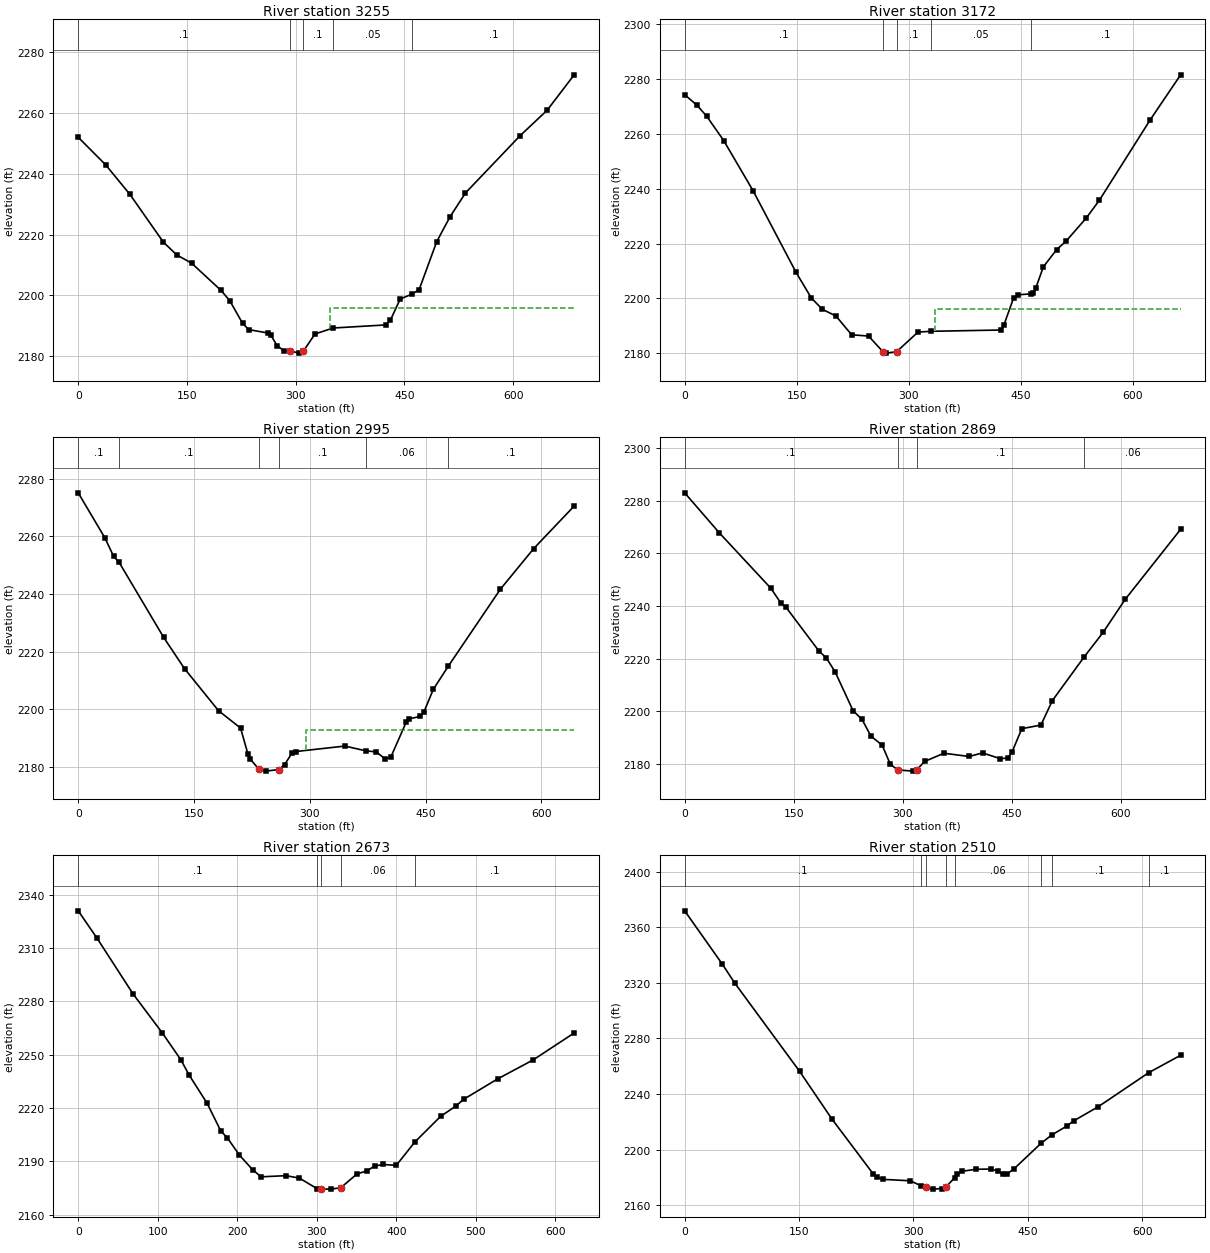
Type RM Length L Ch R = 1 ,3255    ,82.8,82.8,82.8
XS GIS Cut Line= 2
2435585.38302765556786.6958113612435855.55281272557415.090718863
#Sta/Elev= 30
       0 2252.05    37.9 2242.97    71.3 2233.26   117.5 2217.53     136 2213.33
   156.3 2210.65   196.8 2201.71     209 2198.31   226.6 2190.88   235.1 2188.78
   261.2 2187.68   265.6 2186.99   274.3 2183.49   284.5 2181.68   291.7 2181.78
   304.7 2181.04   310.72181.741   326.5 2187.33   351.4  2189.3   424.5 2190.32
   430.6  2191.9   444.1 2198.84     461 2200.53   470.2 2201.93   494.5 2217.74
   512.8 2225.89   534.1 2233.73   609.5 2252.58   646.8 2260.95     684 2272.59
#Mann= 5 ,-1 , 0
       0      .1       0   291.7    .045       0   310.7      .1       0
   351.4     .05       0     461      .1       0
#XS Ineff= 2 , 0
                          346.72         2195.92
Permanent Ineff=
       F       F
Bank Sta=291.7,310.7
XS Rating Curve= 0 ,0
Exp/Cntr(USF)=0,0
Exp/Cntr=0.3,0.1

Type RM Length L Ch R = 1 ,3172    ,177.1,177.1,177.1
XS GIS Cut Line= 2
2435508.29768604556839.805651275 2435791.0542563 557441.00651426
#Sta/Elev= 30
       0 2274.23    16.4 2270.44    29.7 2266.33    52.4 2257.48    91.6 2239.26
     149 2209.59   169.6 2200.18   184.4 2196.02   202.7 2193.57   223.7 2186.73
   246.3 2186.27   265.8 2180.52   269.8 2180.05   283.9 2180.56   312.6 2187.72
   330.2 2188.01   423.1 2188.47   427.5 2190.17   440.7 2200.21   446.2  2201.3
   464.2 2201.66   467.3 2201.89   470.2 2203.63   480.5  2211.5   498.2 2217.73
   511.5 2221.05     538 2229.29   555.7 2235.83   623.5 2265.02   664.4 2281.49
#Mann= 5 ,-1 , 0
       0      .1       0   265.8    .045       0   283.9      .1       0
   330.2     .05       0   464.2      .1       0
#XS Ineff= 2 , 0
                          334.81         2196.16
Permanent Ineff=
       F       F
Bank Sta=265.8,283.9
XS Rating Curve= 0 ,0
Exp/Cntr(USF)=0,0
Exp/Cntr=0.3,0.1

Type RM Length L Ch R = 1 ,2995    ,125.7,125.7,125.7
XS GIS Cut Line= 2
2435332.94800033556957.4612564072435679.05630096557498.598837545
#Sta/Elev= 30
       0 2275.11    34.7 2259.41    45.9 2253.05   53.032250.971   110.6 2224.98
   137.7  2214.1   181.8 2199.49   210.3 2193.49   219.8  2184.5   222.5 2182.81
   233.8 2179.28   242.8 2178.54   260.2 2179.09   267.3 2180.83   276.8 2184.71
   281.5 2185.33   345.5 2187.24  372.742185.569     386 2185.22   397.5 2182.81
     405 2183.45   425.2 2195.75   428.7 2196.69     443 2197.51   447.7 2199.01
     460 2206.94  479.312214.936   546.8 2241.65   590.1 2255.79   642.4 2270.52
#Mann= 6 ,-1 , 0
       0      .1       0   53.03      .1       0   233.8    .045       0
   260.2      .1       0  372.74     .06       0  479.31      .1       0
#XS Ineff= 2 , 0
                          294.89         2192.82
Permanent Ineff=
       F       F
Bank Sta=233.8,260.2
XS Rating Curve= 0 ,0
Exp/Cntr(USF)=0,0
Exp/Cntr=0.3,0.1

Type RM Length L Ch R = 1 ,2869    ,196,196,196
XS GIS Cut Line= 2
2435168.27169887 557010.260307882435612.55090098557528.586043685
#Sta/Elev= 30
       0 2282.97    47.9  2267.7   118.6 2246.73   132.8 2240.94   139.7 2239.42
   184.9 2222.83     195 2220.26   207.3 2214.84   231.8  2200.2   244.1 2196.89
   256.4 2190.53   271.8 2187.12   283.1 2179.84   293.3  2177.7   314.4 2177.24
  319.39  2177.7   330.2 2180.91   356.9 2184.04   391.6  2182.8   410.1 2184.17
   434.6 2181.95   444.8 2182.25   450.5 2184.41   464.1 2193.36   490.4 2194.75
   506.2 2204.06   549.8 2220.59     576 2229.95   606.5 2242.53   682.7  2269.1
#Mann= 4 ,-1 , 0
       0      .1       0   293.3    .045       0  319.39      .1       0
   549.8     .06       0
Bank Sta=293.3,319.39
XS Rating Curve= 0 ,0
Exp/Cntr(USF)=0,0
Exp/Cntr=0.3,0.1

Type RM Length L Ch R = 1 ,2673    ,163.6,163.6,163.6
XS GIS Cut Line= 2
2435057.94283211557202.4307930742435508.43300118557633.692723219
#Sta/Elev= 30
       0 2331.05    23.7 2315.62    68.9  2284.3   105.7 2262.32   129.1 2247.17
   139.6 2238.49   162.2  2222.6   179.2 2207.16   187.7 2203.09   202.7 2193.52
   220.1 2184.89   230.2 2181.28   261.3 2181.93   278.2 2180.55  300.662174.506
   305.72174.388   317.8 2174.35   330.22175.154   350.5 2182.89   363.1 2184.65
   372.7 2187.37   383.8 2188.22   399.9 2187.73  423.462200.963   455.7 2215.31
   474.6 2221.06   484.7 2224.94   527.7 2236.49     572 2247.09   623.6 2262.27
#Mann= 5 ,-1 , 0
       0      .1       0  300.66     .06       0   305.7    .045       0
   330.2     .06       0  423.46      .1       0
Bank Sta=305.7,330.2
XS Rating Curve= 0 ,0
Exp/Cntr(USF)=0,0
Exp/Cntr=0.3,0.1

Type RM Length L Ch R = 1 ,2510    ,113.1,113.1,113.1
XS GIS Cut Line= 2
2434888.08002106557374.3285190362435454.16475824557694.882526838
#Sta/Elev= 30
       0  2371.8    49.5 2333.36    65.5 2319.98   150.7 2256.41   193.2 2222.05
   247.2 2182.69   251.9 2180.45   260.3 2178.71     296 2177.68  310.292174.013
   316.5 2173.15   325.3 2171.69     337 2172.12   342.9 2173.37  354.022179.844
   357.7 2182.25   363.5 2184.48   382.1 2185.98   401.6 2186.11   410.4 2184.75
   417.2 2182.53   422.7 2182.61   431.4 2185.99  467.472204.661  481.342210.576
   501.4  2217.1   510.2 2220.78   542.5 2230.96  608.662255.433   650.5 2267.95
#Mann= 8 ,-1 , 0
       0      .1       0  310.29    .055       0   316.5    .045       0
   342.9    .055       0  354.02     .06       0  467.47      .1       0
  481.34      .1       0  608.66      .1       0
Bank Sta=316.5,342.9
XS Rating Curve= 0 ,0
Exp/Cntr(USF)=0,0
Exp/Cntr=0.5,0.3