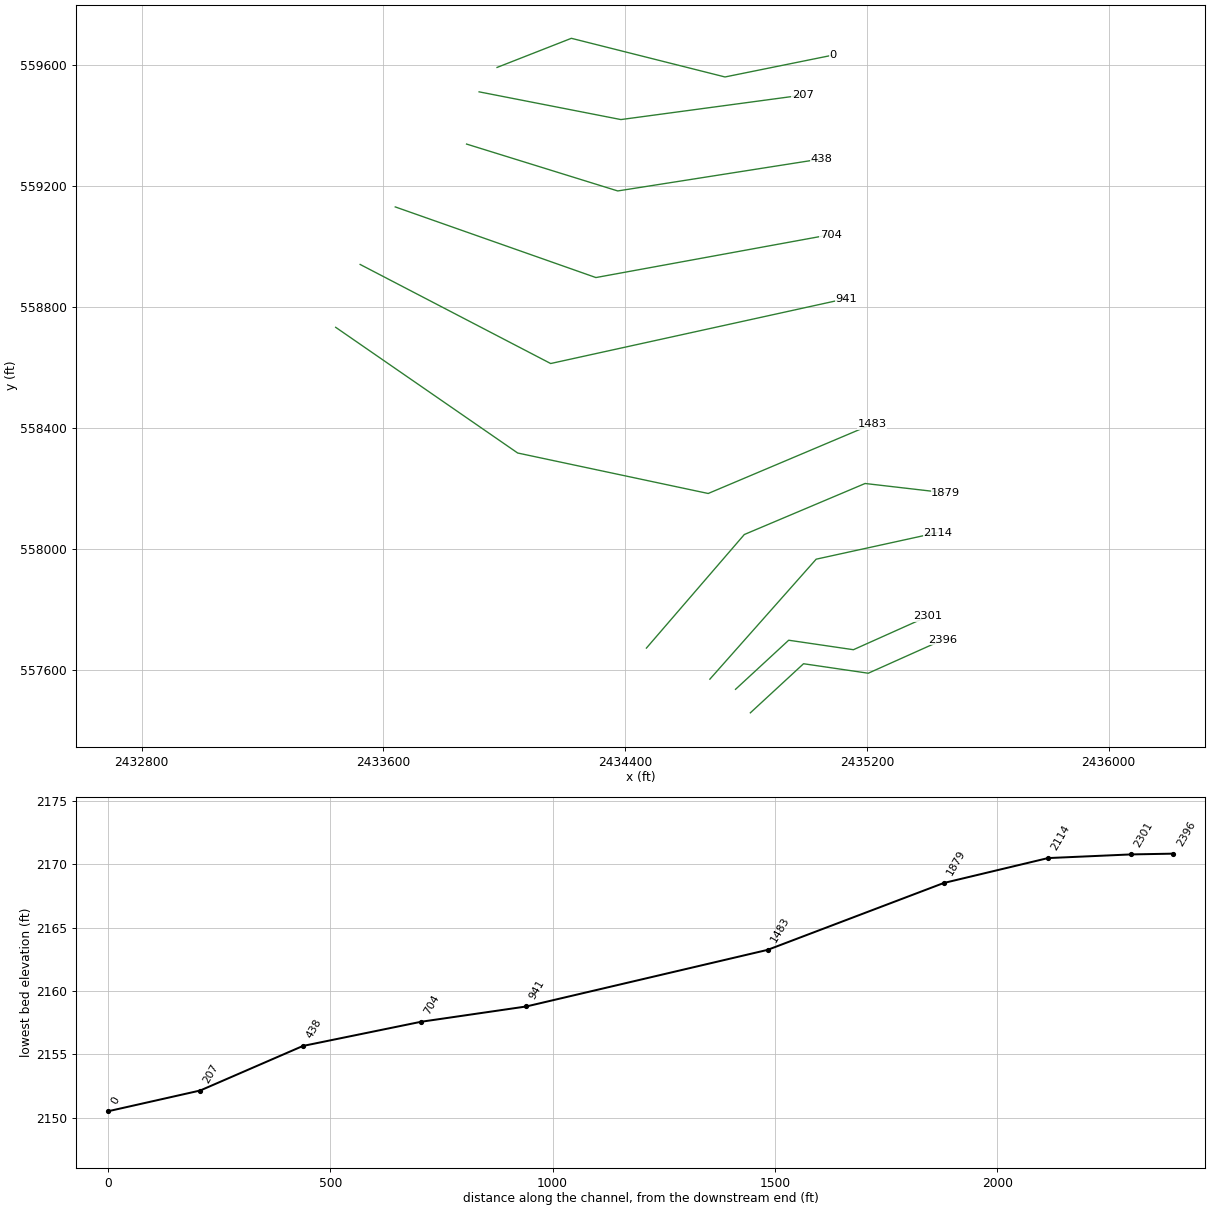
HEC-RAS study WHITHORNCK.prj: WHITHORNCK

--- WHITHORNCK.g01 (geometry) --- (continued)

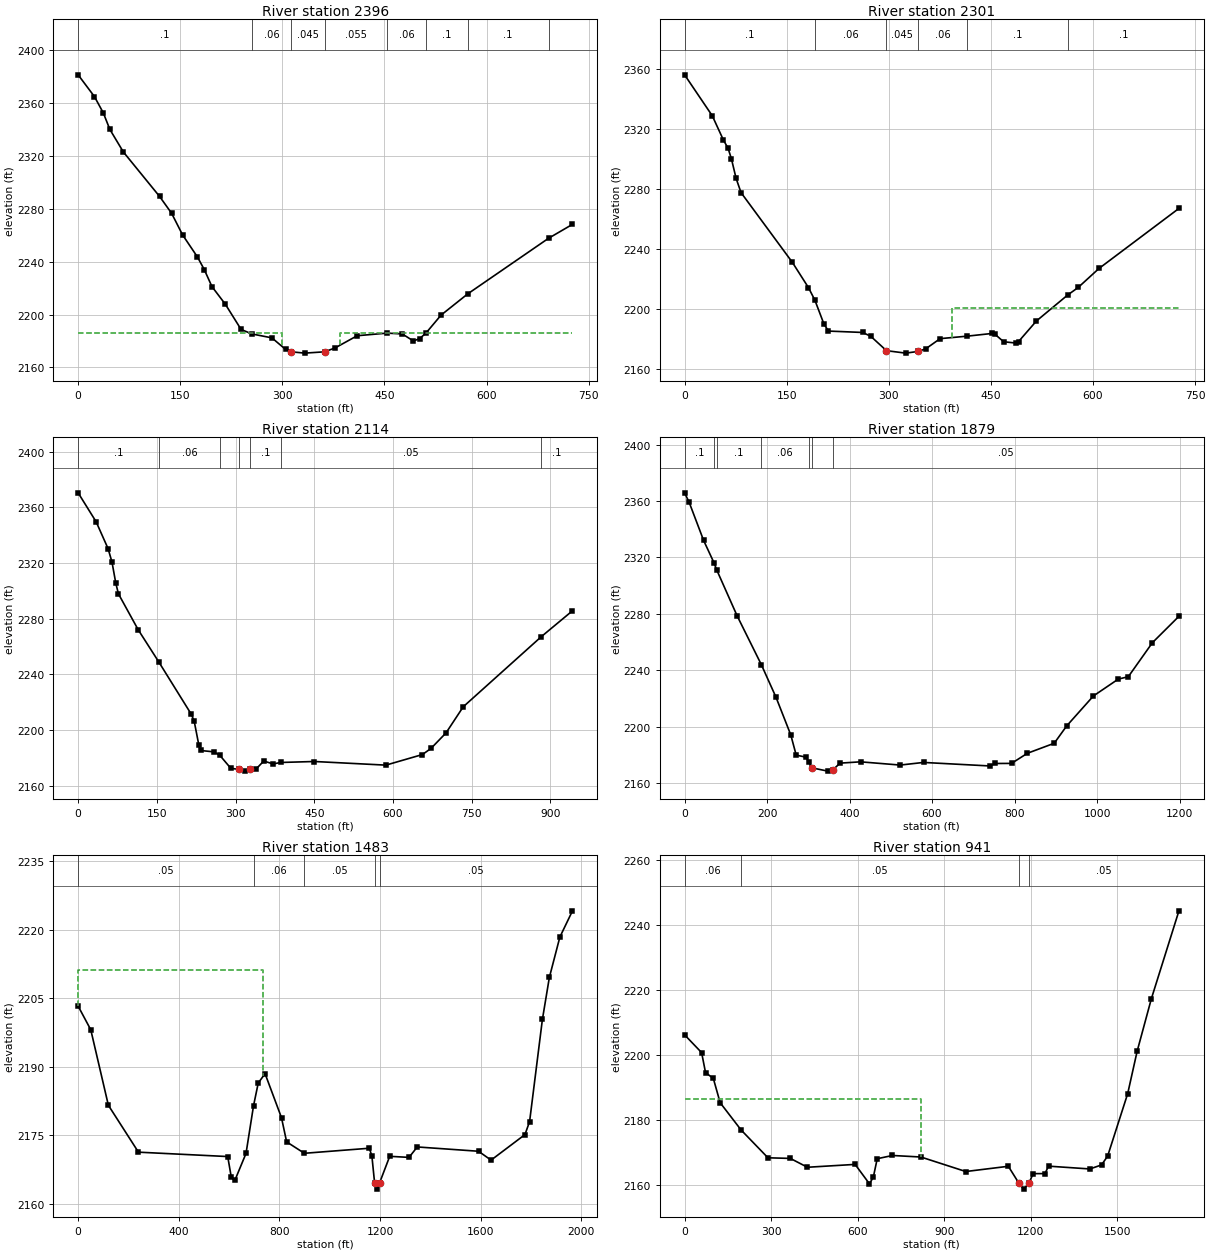
Type RM Length L Ch R = 1 ,2396    ,95,95,95
XS GIS Cut Line= 4
2434814.42080225557457.5361551042434990.38449164557619.859248416
2435204.54185004 557588.485877442435451.43663903557698.974705661
#Sta/Elev= 30
       0 2381.39      24 2364.89      37 2352.56    46.6  2340.1    66.4 2323.06
   119.6 2289.42   137.3 2276.68   153.4 2260.35   175.2 2243.67   185.3 2234.09
   196.6 2221.19   216.4 2207.74   239.4 2188.78  255.252185.365   284.7  2182.4
   304.9 2173.62     313 2171.86   332.9 2170.85     362 2171.84   377.6  2174.8
     410 2184.02  453.912185.986   476.2 2185.37   492.7 2180.01   501.8 2181.89
  510.76 2185.85   533.2  2199.6  572.382215.665  691.242257.765   726.3 2268.27
#Mann= 8 ,-1 , 0
       0      .1       0  255.25     .06       0     313    .045       0
     362    .055       0  453.91     .06       0  510.76      .1       0
  572.38      .1       0  691.24      .1       0
#XS Ineff= 2 , 0
          299.66    2186  384.04            2186
Permanent Ineff=
       F       F
Bank Sta=313,362
XS Rating Curve= 0 ,0
Exp/Cntr(USF)=0,0
Exp/Cntr=0.5,0.3

Type RM Length L Ch R = 1 ,2301    ,187.2,187.2,187.2
XS GIS Cut Line= 4
2434765.31465637557535.2875527412434941.27834576557697.610646053
2435155.43570416557666.2372750772435402.33049315557776.726103298
#Sta/Elev= 30
       0 2356.25    40.7 2328.93      57 2312.81    63.9 2307.29    68.8 2300.23
    75.7 2287.21    82.9 2277.77   158.3  2231.3   181.9 2214.51  191.422206.077
   204.6 2190.32   211.3 2185.49   261.8 2184.56   273.7 2181.93   296.6 2172.43
   324.8 2170.79   343.42171.928   354.5 2173.72   375.4 2180.44   415.5 2182.11
   451.2 2183.88   455.9 2183.42   468.7 2178.38   486.2 2177.53   490.6 2178.48
   516.9 2192.21  562.692209.472   578.2 2214.53   608.9 2227.23   726.3 2267.23
#Mann= 6 ,-1 , 0
       0      .1       0  191.42     .06       0   296.6    .045       0
   343.4     .06       0   415.5      .1       0  562.69      .1       0
#XS Ineff= 2 , 0
                          392.17         2201.02
Permanent Ineff=
       F       F
Bank Sta=296.6,343.4
XS Rating Curve= 0 ,0
Exp/Cntr(USF)=0,0
Exp/Cntr=0.5,0.3

Type RM Length L Ch R = 1 ,2114    ,234.6,234.6,234.6
XS GIS Cut Line= 3
2434680.45249796557568.8981759292435032.22644342557965.579433577
 2435434.5211151558053.522919943
#Sta/Elev= 30
       0 2370.53    34.3 2349.72      57 2330.46    64.5 2320.79    71.8 2305.51
    76.8 2297.92   114.5 2272.08  154.15 2248.71   215.7 2211.33   221.2 2206.32
   229.8 2189.63   233.2 2185.34   258.9 2184.34  270.092181.812   290.9 2172.54
     307 2171.71   317.6  2170.5   328.4 2171.77   339.1 2172.03   353.8 2177.78
   371.5 2175.66  386.032176.725   450.3 2177.42   586.4 2174.81     656 2182.41
   672.4 2186.82   701.1    2198   733.8 2216.73  882.652267.159     942 2285.75
#Mann= 7 ,-1 , 0
       0      .1       0  154.15     .06       0  270.09      .1       0
     307    .045       0   328.4      .1       0  386.03     .05       0
  882.65      .1       0
Bank Sta=307,328.4
XS Rating Curve= 0 ,0
Exp/Cntr(USF)=0,0
Exp/Cntr=0.3,0.1

Type RM Length L Ch R = 1 ,1879    ,396,396,396
XS GIS Cut Line= 4
2434470.42414004557671.6529878582434794.39315235558047.122375146
2435194.13506555558215.8627508282435461.19304376558185.006898202
#Sta/Elev= 30
       0  2365.8    11.2 2358.98    46.1 2332.06   71.152316.289   77.922311.125
   127.4 2278.58   186.12243.982   221.7 2220.85   257.4 2194.24   270.6 2179.86
   294.4 2178.45  301.052174.864   309.3 2170.82   347.2 2168.53   358.72169.233
     377  2174.2   426.5 2175.12   522.8 2172.83   579.3 2174.69   739.9  2172.2
   752.5 2173.95   792.7 2174.01   831.1 2181.18   896.2 2188.28   926.5 2200.61
   991.2 2221.81  1051.6 2233.78  1075.8 2235.44  1134.3 2259.59  1198.6 2278.28
#Mann= 7 ,-1 , 0
       0      .1       0   71.15      .1       0   77.92      .1       0
   186.1     .06       0  301.05     .05       0   309.3    .045       0
   358.7     .05       0
Bank Sta=309.3,358.7
XS Rating Curve= 0 ,0
Exp/Cntr(USF)=0,0
Exp/Cntr=0.3,0.1

Type RM Length L Ch R = 1 ,1483    ,542.6,542.6,542.6
XS GIS Cut Line= 4
2433441.94294188558732.3203501172434044.29952268558316.659083833
2434674.83652832558182.8020658772435217.30970635558411.768017644
#Sta/Elev= 30
       0 2203.26    50.3 2198.08   120.2 2181.58   239.8 2171.33   594.7 2170.37
     609 2165.82   622.9 2165.14   667.5 2171.07  697.28 2181.47     716 2186.44
   743.1  2188.5   808.5 2178.86   828.9 2173.58  899.462171.085  1157.8 2172.19
  1167.9 2170.47  1178.62164.625  1188.8 2163.25  1198.2 2164.58  1238.7 2170.42
  1315.5 2170.19  1348.2 2172.47  1591.7 2171.53  1641.7 2169.59  1776.3 2175.17
  1794.8 2178.01  1845.7 2200.34  1873.4 2209.53  1915.2 2218.36  1965.3 2224.09
#Mann= 5 ,-1 , 0
       0     .05       0  697.28     .06       0  899.46     .05       0
  1178.6    .045       0  1198.2     .05       0
#XS Ineff= 2 , 0
          736.73 2211.12
Permanent Ineff=
       F       F
Bank Sta=1178.6,1198.2
XS Rating Curve= 0 ,0
Exp/Cntr(USF)=0,0
Exp/Cntr=0.3,0.1

Type RM Length L Ch R = 1 ,941     ,236.9,236.9,236.9
XS GIS Cut Line= 3
2433522.96166328558940.1509832592434153.49866891558612.553544577
2435132.76843185558827.429283927
#Sta/Elev= 30
       0  2206.2      59 2200.73    72.5 2194.61    99.6 2192.79   123.2 2185.34
  195.75 2176.96   288.9 2168.41   366.4 2168.22   425.7  2165.5   590.9 2166.38
   640.5 2160.42     654 2162.45   667.5 2168.13   720.4 2169.12   818.8 2168.65
   974.4 2164.19  1121.9  2165.8  1158.7 2160.57  1175.1 2158.78    1193 2160.55
  1207.8 2163.54  1248.8 2163.55  1261.1 2165.84  1404.4 2164.98  1444.8 2166.22
  1465.9 2168.91  1535.4  2188.1  1568.2 2201.14  1617.3 2217.23  1713.1 2244.31
#Mann= 4 ,-1 , 0
       0     .06       0  195.75     .05       0  1158.7    .045       0
    1193     .05       0
#XS Ineff= 2 , 0
          819.41 2186.43
Permanent Ineff=
       F       F
Bank Sta=1158.7,1193
XS Rating Curve= 0 ,0
Exp/Cntr(USF)=0,0
Exp/Cntr=0.3,0.1

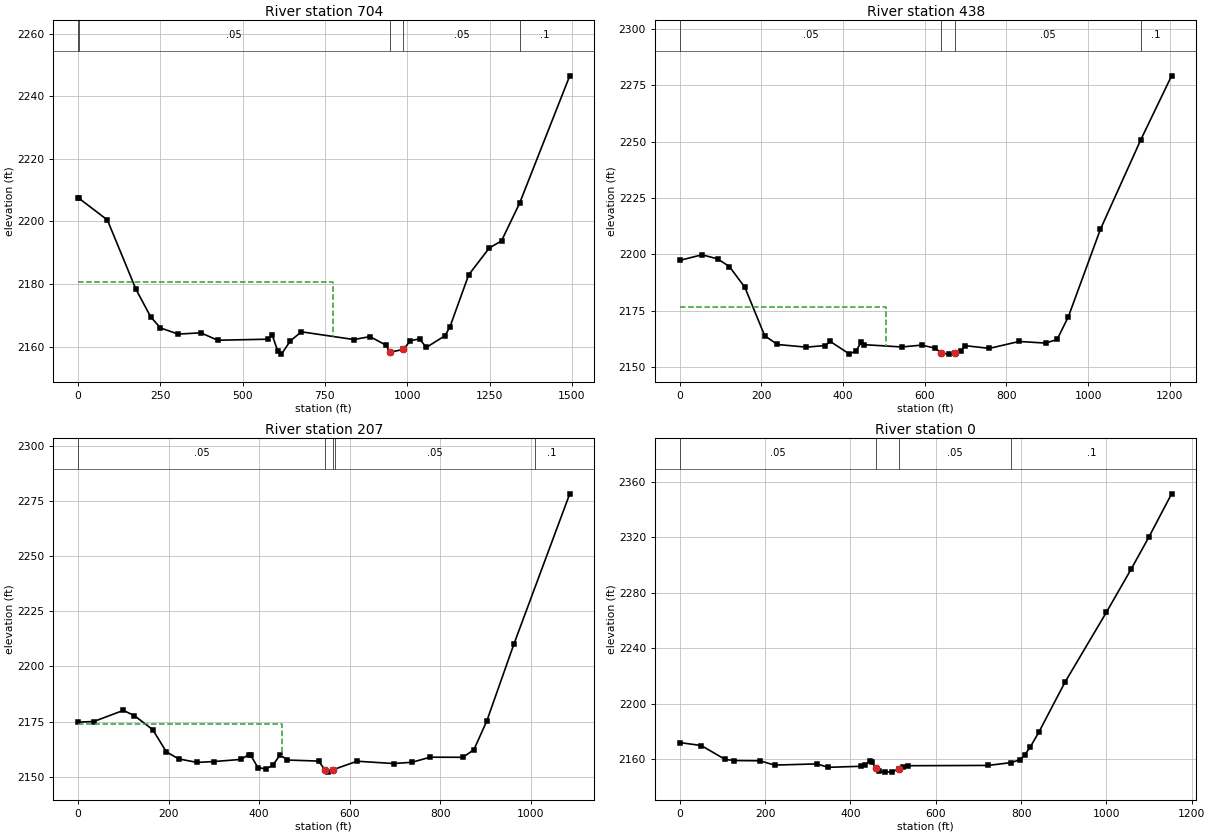
Type RM Length L Ch R = 1 ,704     ,265.6,265.6,265.6
XS GIS Cut Line= 3
2433639.20591571 559130.368850882434303.22981305558896.819052636
2435079.93013529559038.782470173
#Sta/Elev= 30
       0 2207.57    2.332207.423    89.2 2200.45   175.7 2178.37   220.6  2169.5
   250.3 2165.94   304.3 2163.97   373.1 2164.38   424.1 2162.01   577.2 2162.34
   589.5 2163.81   606.4  2158.6     618 2157.57   644.6 2161.76   678.5  2164.7
   838.1 2162.23   886.9 2163.17   935.5 2160.42   947.12158.182   988.42159.078
  1008.9  2161.8  1037.3 2162.47  1057.7 2159.69  1114.8 2163.47  1129.8 2166.33
  1186.6 2182.91  1248.8 2191.45  1286.3 2193.78  1341.3 2205.83  1493.5 2246.52
#Mann= 5 ,-1 , 0
       0     .06       0    2.33     .05       0   947.1    .045       0
   988.4     .05       0  1341.3      .1       0
#XS Ineff= 2 , 0
           775.6 2180.57
Permanent Ineff=
       F       F
Bank Sta=947.1,988.4
XS Rating Curve= 0 ,0
Exp/Cntr(USF)=0,0
Exp/Cntr=0.3,0.1

Type RM Length L Ch R = 1 ,438     ,231.1,231.1,231.1
XS GIS Cut Line= 3
2433875.21697369559338.1994840222434375.41951447559183.207147441
2435048.22715735559288.883740564
#Sta/Elev= 30
       0  2197.3    54.2 2199.77    92.6 2197.95   121.4 2194.54   159.2 2185.34
   207.7 2163.88   238.8 2159.94   309.9 2158.75     356 2159.48   368.6 2161.28
   414.6  2155.8   431.4 2156.97   443.9 2160.92   452.3 2159.85   543.8 2158.84
   592.3 2159.66   624.7 2158.35   640.9 2156.17   658.9 2155.66   673.3 2155.94
   689.5 2157.22   697.8 2159.44   758.3 2158.21   831.2 2161.28     896 2160.56
   924.3 2162.17   951.9 2172.32  1030.2 2211.04  1128.92250.715  1204.7 2279.24
#Mann= 4 ,-1 , 0
       0     .05       0   640.9    .045       0   673.3     .05       0
  1128.9      .1       0
#XS Ineff= 2 , 0
          504.87 2176.71
Permanent Ineff=
       F       F
Bank Sta=640.9,673.3
XS Rating Curve= 0 ,0
Exp/Cntr(USF)=0,0
Exp/Cntr=0.3,0.1

Type RM Length L Ch R = 1 ,207     ,220,207.3,191.4
XS GIS Cut Line= 3
2433916.63196894559510.9030462542434385.98717378559419.218205416
2434988.34375458 559500.23692681
#Sta/Elev= 30
       0 2174.79    34.8 2175.07     100  2180.1   124.6 2177.74   165.2 2171.34
   195.1 2161.33   222.2 2158.14     263 2156.54   299.7 2156.93   359.8 2157.89
   377.1 2160.06   381.2 2159.81   397.3 2154.23   414.4 2153.61   430.1 2155.16
   446.4 2159.99   462.1 2157.62   531.5 2157.14   545.92153.001   551.6 2152.14
   562.12153.157   616.2 2157.08   696.9 2156.04   737.3 2156.59   777.9 2158.91
   850.3 2158.86   874.5 2162.36   902.8 2175.31   962.4 2209.99    1086 2278.22
#Mann= 5 ,-1 , 0
       0     .05       0   545.9    .045       0   562.1     .05       0
   566.7     .05       0 1008.62      .1       0
#XS Ineff= 2 , 0
          450.86 2174.03
Permanent Ineff=
       F       F
Bank Sta=545.9,562.1
XS Rating Curve= 0 ,0
Exp/Cntr(USF)=0,0
Exp/Cntr=0.3,0.1

Type RM Length L Ch R = 1 ,0       ,,,
XS GIS Cut Line= 5
2433976.08830333559591.6046787652434222.04131848559687.914099455
     2434436.132559634.0949999992434730.50560495559560.093132839
2435087.59210983559632.377850413
#Sta/Elev= 30
       0 2171.83    50.1 2169.72     106  2159.7   127.4 2158.86   187.6 2158.71
   221.9 2155.58   321.6 2156.45   347.4 2153.96   425.7 2154.74     434 2155.61
   446.3  2158.6   450.5 2157.83   458.7  2153.3     467 2151.07   479.8  2150.5
   496.3 2150.67   512.8  2152.6   522.6  2154.3   535.8 2155.13   722.7 2155.34
   776.4 2157.38   797.8  2159.5     808 2162.75     821 2168.39   841.9 2179.52
   902.9 2215.45  1000.1 2266.01    1058 2297.11  1099.9 2320.44  1152.8 2351.48
#Mann= 4 ,-1 , 0
       0     .05       0   458.7    .045       0   512.8     .05       0
   776.4      .1       0
Bank Sta=458.7,512.8
XS Rating Curve= 0 ,0
Exp/Cntr(USF)=0,0
Exp/Cntr=0.3,0.1
LCMann Table=0

Chan Stop Cuts=-1
Use User Specified Reach Order=0
Composite Channel Slope=5